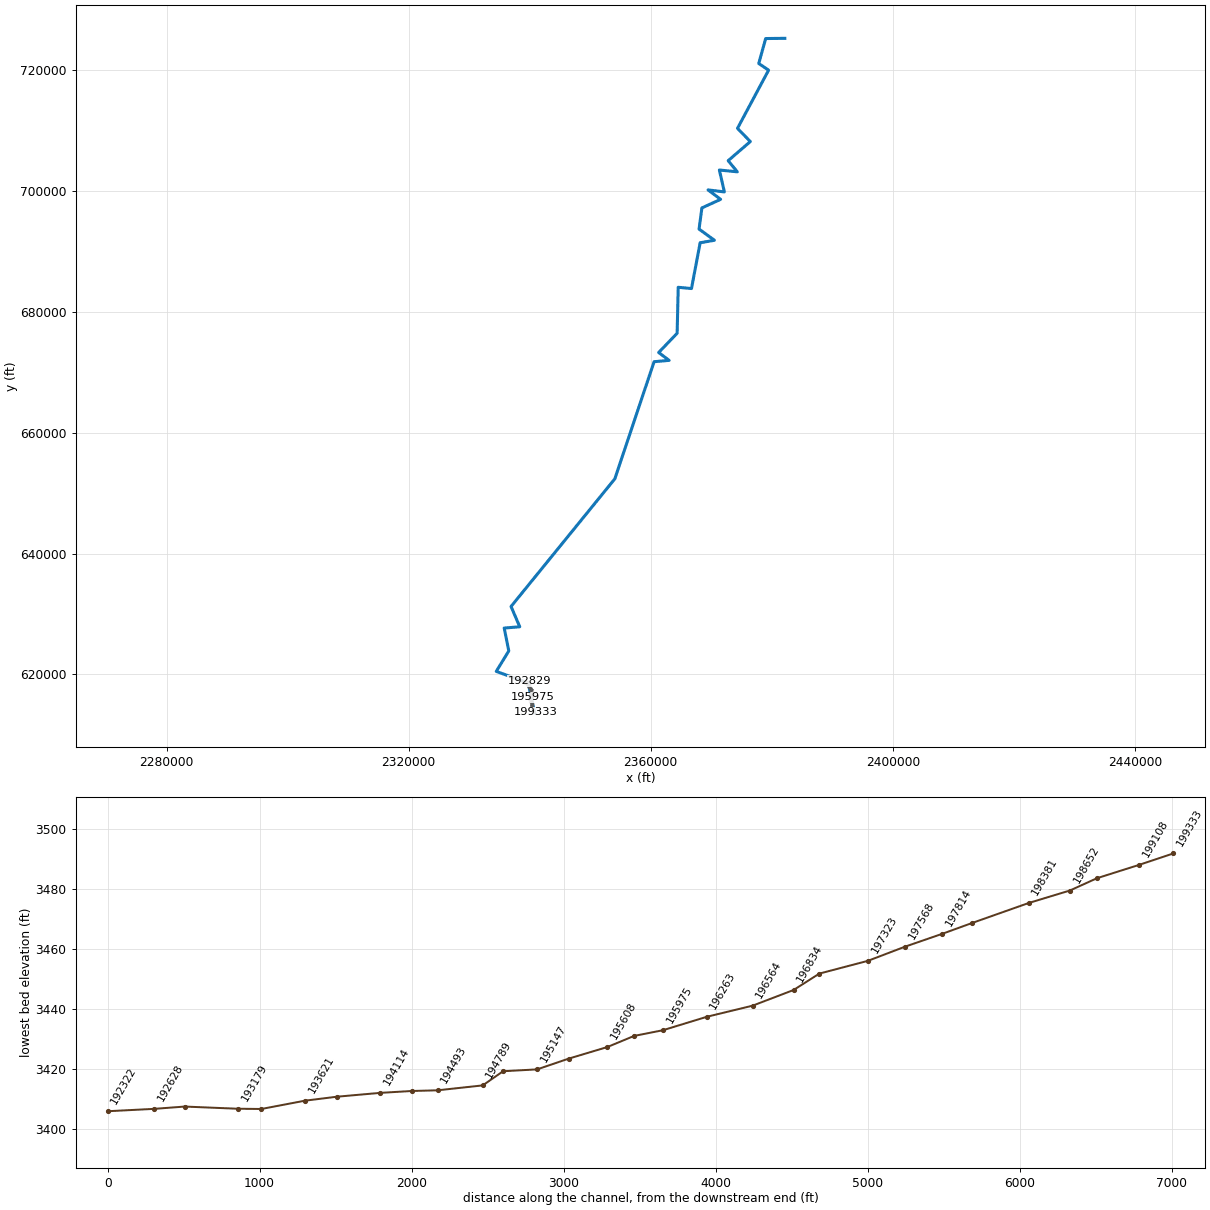
--- LAURELFK.prj (project) ---

Proj Title=LAURELFK
Current Plan=p01
Default Exp/Contr=0,0
English Units
Geom File=g01
Flow File=f01
Plan File=p01
Background Map Layer=Inundation Boundary (P100yr Value_0)
BEGIN DESCRIPTION:
----------MODEL BY WOOD PLC 2022----------
AFH study
Randolph County, WV
HEC-RAS Version: RAS 6.2
Vertical Datum: NAVD88
Projection: NAD 1983 StatePlane West Virginia S FIPS 4702 (US Feet)
Terrain: 1-meter LIDAR (FEMA Region III 3DEP collected 2016-2018)
Land Use: 2019 NLCD
Hydrologic Method:
WV SIR2010-5033 regression equations
Additional Model Notes:
Split flow @ RS 33551
END DESCRIPTION:
DSS Export Rating Curves= 0
DSS Export Rating Curve Sorted= 0
DSS Export Volume Flow Curves= 0
DXF OffsetX= 0
DXF OffsetY= 0
DXF ScaleX= 0
DXF ScaleY= 0

--- LAURELFK.p01 (plan) ---

Plan Title=Floodplain
Program Version=6.10
Short Identifier=Floodplain
Geom File=g01
Flow File=f01
Subcritical Flow
K Sum by GR= 0
Std Step Tol= 0.01
Critical Tol= 0.01
Num of Std Step Trials= 20
Max Error Tol= 0.3
Flow Tol Ratio= 0.001
Split Flow NTrial= 30
Split Flow Tol= 0.02
Split Flow Ratio= 0.02
Log Output Level= 0
Friction Slope Method= 1
Unsteady Friction Slope Method= 2
Unsteady Bridges Friction Slope Method= 1
Parabolic Critical Depth
Global Vel Dist= 0 , 0 , 0
Global Log Level= 0
CheckData=False
Encroach Param=-1 ,0,0, 0
Mapping Interval=1HOUR
Computation Time Step Use Courant=        0
Computation Time Step Use Time Series=    0
Computation Time Step Count To Double=0
Computation Time Step Max Doubling=0
Computation Time Step Max Halving=0
Computation Time Step Residence Courant=0
Run HTab= 0
Run UNet= 0
Run Sediment= 0
Run PostProcess= 0
Run WQNet= 0
Run RASMapper=-1
UNET Theta= 0
UNET Theta Warmup= 0
UNET ZTol= 0
UNET ZSATol= 0
UNET MxIter= 0
UNET Max Iter WO Improvement= 0
UNET MaxInSteps= 0
UNET DtIC= 0
UNET DtMin= 0
UNET MaxCRTS= 0
UNET WFStab= 0
UNET SFStab= 0
UNET WFX= 1
UNET SFX= 1
UNET Gravity=32.174
UNET 1D Methodology=Finite Difference
UNET DSS MLevel= 1
UNET Pardiso=0
UNET DZMax Abort= 0
UNET Use Existing IB Tables= 0
UNET Froude Reduction=False
UNET Froude Limit= 0
UNET Froude Power= 0
UNET D1 Cores= 0
UNET WindReference=Eulerian
UNET WindDragFormulation=Hsu (1988)
UNET D2 Coriolis=0
UNET D2 Cores= 0
UNET D2 Theta= 1
UNET D2 Theta Warmup= 1
UNET D2 Z Tol= 0.01
UNET D2 Volume Tol= 0.01
UNET D2 Max Iterations= 20
UNET D2 Equation= 0
UNET D2 RampUpFraction=0.1
UNET D2 TimeSlices= 1
UNET D2 Turbulence Formulation=Non-Conservative (original)
UNET D2 Eddy Viscosity=0.3
UNET D2 Transverse Eddy Viscosity=0.1
UNET D2 Smagorinsky Mixing=0
UNET D2 BCVolumeCheck=0
UNET D2 Cores=0
UNET D2 SolverType=PARDISO (Direct)
UNET D2 Minimum Iterations= 2147483647
UNET D2 Maximum Iterations= 2147483647
UNET D2 Restart Number= 10
UNET D2 Relaxation Coeff=1.3
UNET D2 SOR Precondition Iterations= 10
UNET D2 ILUT Maximum Fill= 8
UNET D2 ILUT Tolerance=1E-08
UNET D1D2 MaxIter= 0
UNET D1D2 ZTol=0.01
UNET D1D2 QTol=0.1
UNET D1D2 MinQTol=1
Write IC File= 0
Write IC File at Fixed DateTime=0
Write IC File at Sim End=0
Echo Input=False
Echo Parameters=False
Echo Output=False
Write Detailed= 0
HDF Write Warmup=0
HDF Write Time Slices=0
HDF Flush=0
HDF Compression= 1
HDF Chunk Size= 1
HDF Spatial Parts= 1
HDF Use Max Rows=0
HDF Fixed Rows= 1
Calibration Method= 0
Calibration Iterations= 20
Calibration Max Change=0.05
Calibration Tolerance=0.2
Calibration Maximum=1.5
Calibration Minimum=0.5
Calibration Optimization Method= 1
WQ AD Non Conservative
WQ ULTIMATE=-1
WQ Max Comp Step=1HOUR
WQ Output Interval=15MIN
WQ Output Selected Increments= 0
WQ Output face flow=0
WQ Output face velocity=0
WQ Output face area=0
WQ Output face dispersion=0
WQ Output cell volume=0
WQ Output cell surface area=0
WQ Output cell continuity=0
WQ Output cumulative cell continuity=0
WQ Output face conc=0
WQ Output face dconc_dx=0
WQ Output face courant=0
WQ Output face peclet=0
WQ Output face adv mass=0
WQ Output face disp mass=0
WQ Output cell mass=0
WQ Output cell source sink temp=0
WQ Output nsm pathways=0
WQ Output nsm derived pathways=0
WQ Create Restart=0
WQ Fixed Restart=0
WQ System Summary=0
WQ Write To DSS=0
Sorting and Armoring Iterations= 10
XS Update Threshold= 0.02
Bed Roughness Predictor= 0
Hydraulics Update Threshold= 0.02
Energy Slope Method= 1
Volume Change Method= 1
Sediment Retention Method= 0
Sediment TS Multiplier= 1
Warm Up Method= 0
XS Weighting Method= 0
Number of US Weighted Cross Sections= 1
Number of DS Weighted Cross Sections= 1
Upstream XS Weight=0
Main XS Weight=1
Downstream XS Weight=0
Number of DS XS's Weighted with US Boundary= 1
Upstream Boundary Weight= 1
Weight of XSs Associated with US Boundary= 0
Number of US XS's Weighted with DS Boundary= 1
Downstream Boundary Weight= 0.5
Weight of XSs Associated with DS Boundary= 0.5
Percentile Method= 0
Sediment Output Level= 3
Mass or Volume Output= 0
Output Increment Type= 1
Profile and TS Output Increment= 1
Transport Output Increment 1
XS Output Flag= 0
XS Output Increment= 10
Read HDF5 Sediment Hotstart= 0
Sediment Hotstart Type= 0
Write Gradation File= 0
Read Gradation Hotstart= 0
Write HDF5 File= 1
Write Binary Output= 1
Write DSS Sediment File= 0
DSS Sediment Output Type= 1
SV Curve= 0
Specific Gage Flag= 0
Subcell Erosion Methods= 0
Subcell Deposition Methods= 0
Advection Scheme= 1
Matrix Solver= 0
Implicit Weighting Factor= 1
Maximum Outer Loop Convergence Iterations= 5
Convergence Maximum Absolute= 0.001
Convergence RMSE= 0.0001
Grain Fractions Max Abs Error= 0.001
Max Subgrid Regions= 1
Max Subgrid Length Scale= 3.402823E+38
Initial Layer Thickness= 3.402823E+38
Min Layer Thickness= 3.402823E+38
Max Layer Thickness= 3.402823E+38
Number of Layers= 5

--- LAURELFK.f01 (steady flow) ---

Flow Title=Flow
Program Version=4.00
Number of Profiles=1
Profile Names=P100yr
River Rch & RM=LAURELFK,Main,199333
     377
River Rch & RM=LAURELFK,Main,194789
     545
River Rch & RM=LAURELFK,Main,193333
     675
River Rch & RM=LAURELFK,Main,190880
     761
River Rch & RM=LAURELFK,Main,187794
     869
River Rch & RM=LAURELFK,Main,182366
    1300
River Rch & RM=LAURELFK,Main,180033
    1880
River Rch & RM=LAURELFK,Main,171535
    2160
River Rch & RM=LAURELFK,Main,163990
    2410
River Rch & RM=LAURELFK,Main,157090
    3170
River Rch & RM=LAURELFK,Main,144337
    3550
River Rch & RM=LAURELFK,Main,139294
    3990
River Rch & RM=LAURELFK,Main,130534
    4490
River Rch & RM=LAURELFK,Main,119839
    4990
River Rch & RM=LAURELFK,Main,109571
    5710
River Rch & RM=LAURELFK,Main,92098
    6370
River Rch & RM=LAURELFK,Main,74381
    7080
River Rch & RM=LAURELFK,Main,38282
    7870
Boundary for River Rch & Prof#=LAURELFK,Main      ,1
Up Type=0
Dn Type=3
Dn Slope=0.013469

--- LAURELFK.g01 (geometry) ---

Geom Title=Geometry
Program Version=6.20

River Reach=LAURELFK        ,Main
Reach XY= 30
     2340807.914      613645.706     2339749.438      618592.436
     2334469.902      620508.645     2336541.985      623893.894
     2335783.467      627681.172     2338354.306      627889.226
     2336914.853        631249.3     2354069.964      652372.403
      2360554.59      671742.249     2363038.657      671964.614
2361312.30141018673263.605652732     2364365.506      676446.983
     2364543.365      684054.729     2366735.985      683844.317
     2368169.073       691420.74     2370529.473      691831.373
     2367988.584      693680.313     2368457.028      697184.462
     2371553.839      698600.138      2369475.05      700163.825
     2372171.144      699830.385     2371345.156      703456.655
     2374307.186      703156.049     2372799.207      704999.692
      2376461.98      708162.447     2374340.982      710346.375
     2379481.666      719973.302     2377853.591      721075.103
     2378998.828      725204.308     2382164.079      725238.075

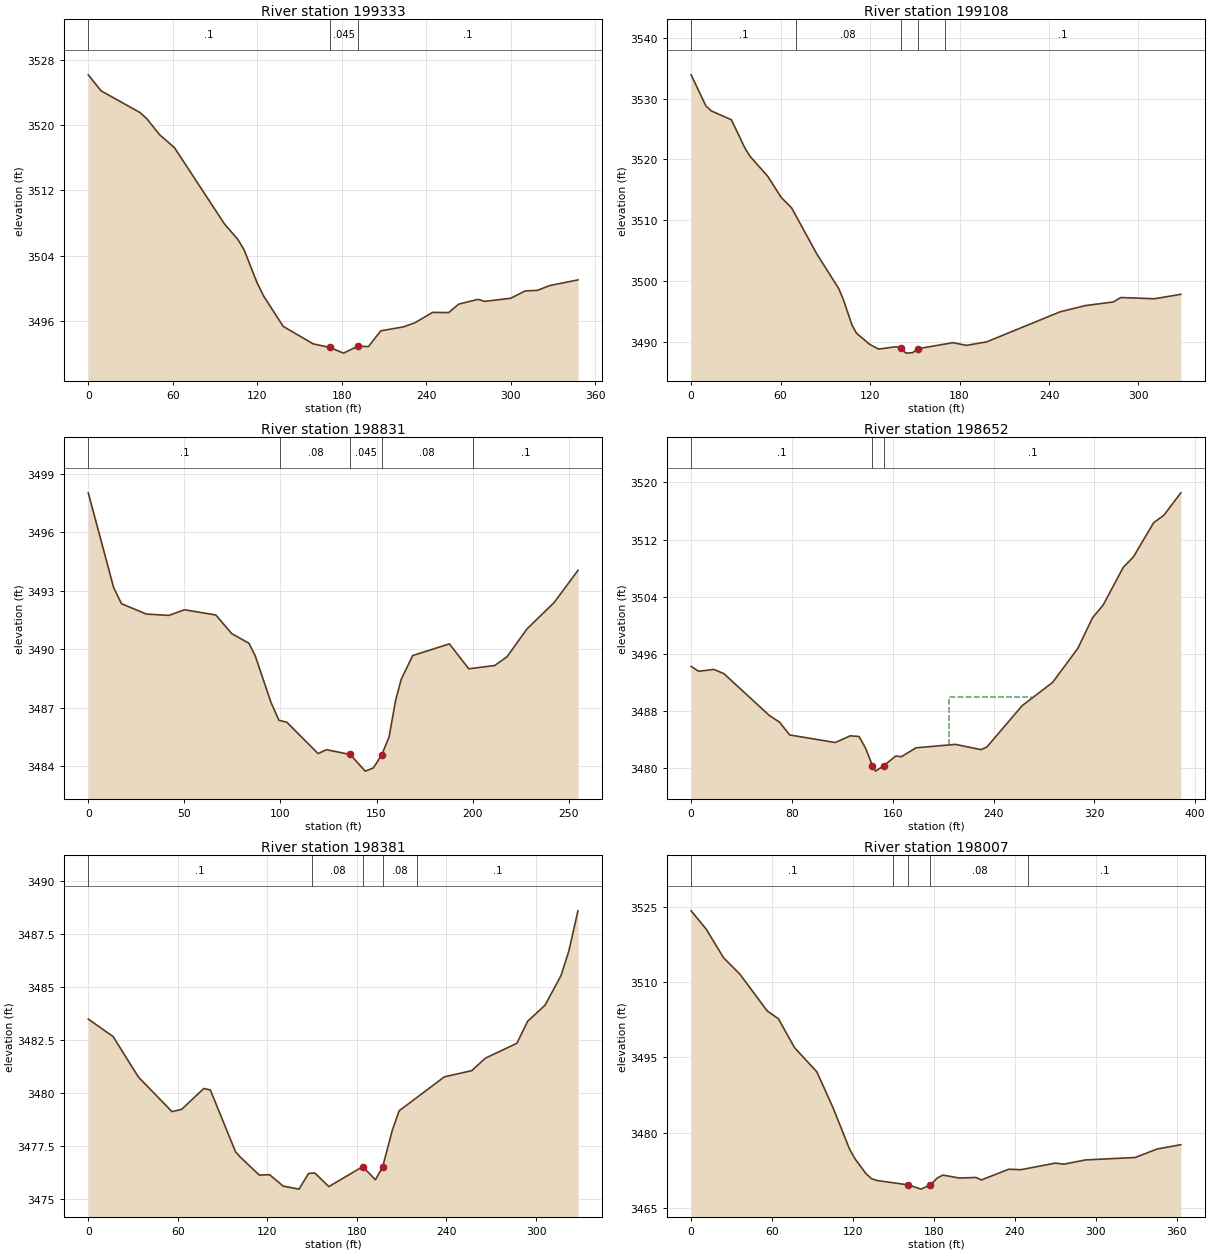
Type RM Length L Ch R = 1 ,199333  ,225.6,225.6,225.6
XS GIS Cut Line= 2
2340644.27400502613565.456811333 2340945.6148697613739.002613343
#Sta/Elev= 30
       0 3526.21     9.1 3524.24    36.8 3521.57    41.4 3520.85    50.7 3518.84
    61.2 3517.26    96.8 3507.86   106.1 3506.01   110.7 3504.69   119.8 3500.68
   124.5 3499.03   138.4  3495.3   159.7 3493.15   171.53492.704   181.3 3492.01
   191.53492.873   198.9 3492.81   207.7 3494.75   223.9 3495.24   231.9 3495.74
   244.5 3497.02   255.9 3496.99     263 3498.03   276.8 3498.62   281.5 3498.37
   299.9 3498.75   310.2 3499.65     319 3499.73   327.6 3500.31   347.7 3501.01
#Mann= 3 ,-1,0
       0      .1       0   171.5    .045       0   191.5      .1       0
Bank Sta=171.5,191.5
XS Rating Curve= 0 ,0
Exp/Cntr=0.3,0.1

Type RM Length L Ch R = 1 ,199108  ,276.6,276.6,276.6
XS GIS Cut Line= 2
2340548.18783283613763.7593825712340839.84562435613914.687190772
#Sta/Elev= 30
       0 3533.89     9.9 3528.78    13.5 3527.97      27 3526.51      36 3521.89
    39.6 3520.48    51.5 3517.19    60.4 3513.76    67.5    3512    84.1 3504.55
      99 3498.78     102 3497.03   107.9 3492.79   110.9 3491.46   119.8 3489.62
   125.7 3488.85   137.6 3489.25   140.63488.955   144.1 3488.19   148.6 3488.27
   152.4 3488.93   175.6 3489.91   184.6 3489.46   198.2 3490.04   247.4 3494.97
   264.2 3495.99     283 3496.59   288.2 3497.32   310.8 3497.12   328.4 3497.85
#Mann= 5 ,-1,0
       0      .1       0      70     .08       0   140.6    .045       0
   152.4     .08       0     170      .1       0
Bank Sta=140.6,152.4
XS Rating Curve= 0 ,0
Exp/Cntr(USF)=0,0
Exp/Cntr=0.3,0.1

Type RM Length L Ch R = 1 ,198831  ,179.1,179.1,179.1
XS GIS Cut Line= 2
2340503.22591668614018.8065286022340752.27100071614072.589171611
#Sta/Elev= 30
       0 3498.03    13.2 3493.17    17.3 3492.34    30.2 3491.81    41.9 3491.74
    50.1 3492.03    66.4 3491.76    74.6 3490.81    83.6 3490.31    86.9 3489.66
    95.1 3487.27    99.2 3486.36   103.3 3486.26   119.6 3484.65   123.9 3484.85
   136.33484.604   144.1 3483.75   148.3 3483.91   152.7 3484.58   156.5  3485.5
   159.9 3487.37   162.8 3488.45   168.8 3489.68   187.9 3490.28     198    3489
   211.5 3489.17   217.9 3489.62   228.3 3491.05   242.4  3492.4   254.8 3494.05
#Mann= 5 ,-1,0
       0      .1       0     100     .08       0   136.3    .045       0
   152.7     .08       0     200      .1       0
Bank Sta=136.3,152.7
XS Rating Curve= 0 ,0
Exp/Cntr=0.3,0.1

Type RM Length L Ch R = 1 ,198652  ,271,271,271
XS GIS Cut Line= 2
2340446.20958404 614218.582372152340833.72692943614187.988897514
#Sta/Elev= 30
       0 3494.27       6 3493.59      18 3493.85      26 3493.26    62.2 3487.39
    70.2 3486.47    78.2 3484.69   114.3 3483.63   126.4 3484.57   133.3 3484.47
   138.4 3482.86   143.93480.413   146.4 3479.63   152.9  3480.4   162.5 3481.75
   166.8 3481.64   178.5 3482.89   209.7 3483.37     230 3482.64   234.7 3482.99
   262.8 3488.79   286.9 3492.03   306.9 3496.78   318.6 3501.07     327 3502.84
     343 3508.12   351.1 3509.59   367.1 3514.36   375.3 3515.42   388.7 3518.54
#Mann= 3 ,-1,0
       0      .1       0   143.9    .045       0   152.9      .1       0
#XS Ineff= 1 ,-1
   204.7   269.8    3490
Permanent Ineff=
       F
Bank Sta=143.9,152.9
XS Rating Curve= 0 ,0
Exp/Cntr(USF)=0,0
Exp/Cntr=0.3,0.1

Type RM Length L Ch R = 1 ,198381  ,374.1,374.1,374.1
XS GIS Cut Line= 2
2340433.97219419614287.9275813232340680.75955625614504.121468746
#Sta/Elev= 30
       0 3483.48    16.6 3482.66    33.6 3480.75    56.1 3479.12    62.6 3479.23
    77.4 3480.21    81.8 3480.14    98.6 3477.24   101.7 3476.99   114.6 3476.13
   121.5 3476.15   130.6 3475.61   141.2 3475.47   147.6 3476.21   151.8 3476.23
   161.2 3475.59   183.9 3476.53   192.4 3475.91   197.2 3476.51   203.7 3478.24
   208.3 3479.16   238.6 3480.76   256.9 3481.05   266.1 3481.64   287.2 3482.34
   294.4 3483.38     306 3484.13   316.7 3485.52     322 3486.69   328.1 3488.58
#Mann= 5 ,-1,0
       0      .1       0     150     .08       0   183.9    .045       0
   197.2     .08       0     220      .1       0
Bank Sta=183.9,197.2
XS Rating Curve= 0 ,0
Exp/Cntr(USF)=0,0
Exp/Cntr=0.3,0.1

Type RM Length L Ch R = 1 ,198007  ,193,193,193
XS GIS Cut Line= 2
2340260.60917126614555.110593138  2340617.533042614622.416237336
#Sta/Elev= 30
       0 3524.14    11.2 3520.48      24 3514.82    36.2 3511.52    56.5  3504.2
    64.7 3502.67    76.7 3496.91    93.2 3492.12   105.4 3484.86   117.6 3476.67
   121.7 3474.74   129.8  3471.8   133.9 3470.83     138 3470.48   161.13469.609
   170.5 3468.77   177.5 3469.62   182.7 3471.02   186.8 3471.56     199 3470.98
   211.2 3471.09   215.3  3470.6   235.6 3472.73   244.6 3472.64   270.2 3473.95
   276.4 3473.73   292.5 3474.58   329.3 3475.06   345.6 3476.75   363.2 3477.61
#Mann= 5 ,-1,0
       0      .1       0     150     .08       0   161.1    .045       0
   177.5     .08       0     250      .1       0
Bank Sta=161.1,177.5
XS Rating Curve= 0 ,0
Exp/Cntr(USF)=0,0
Exp/Cntr=0.3,0.1

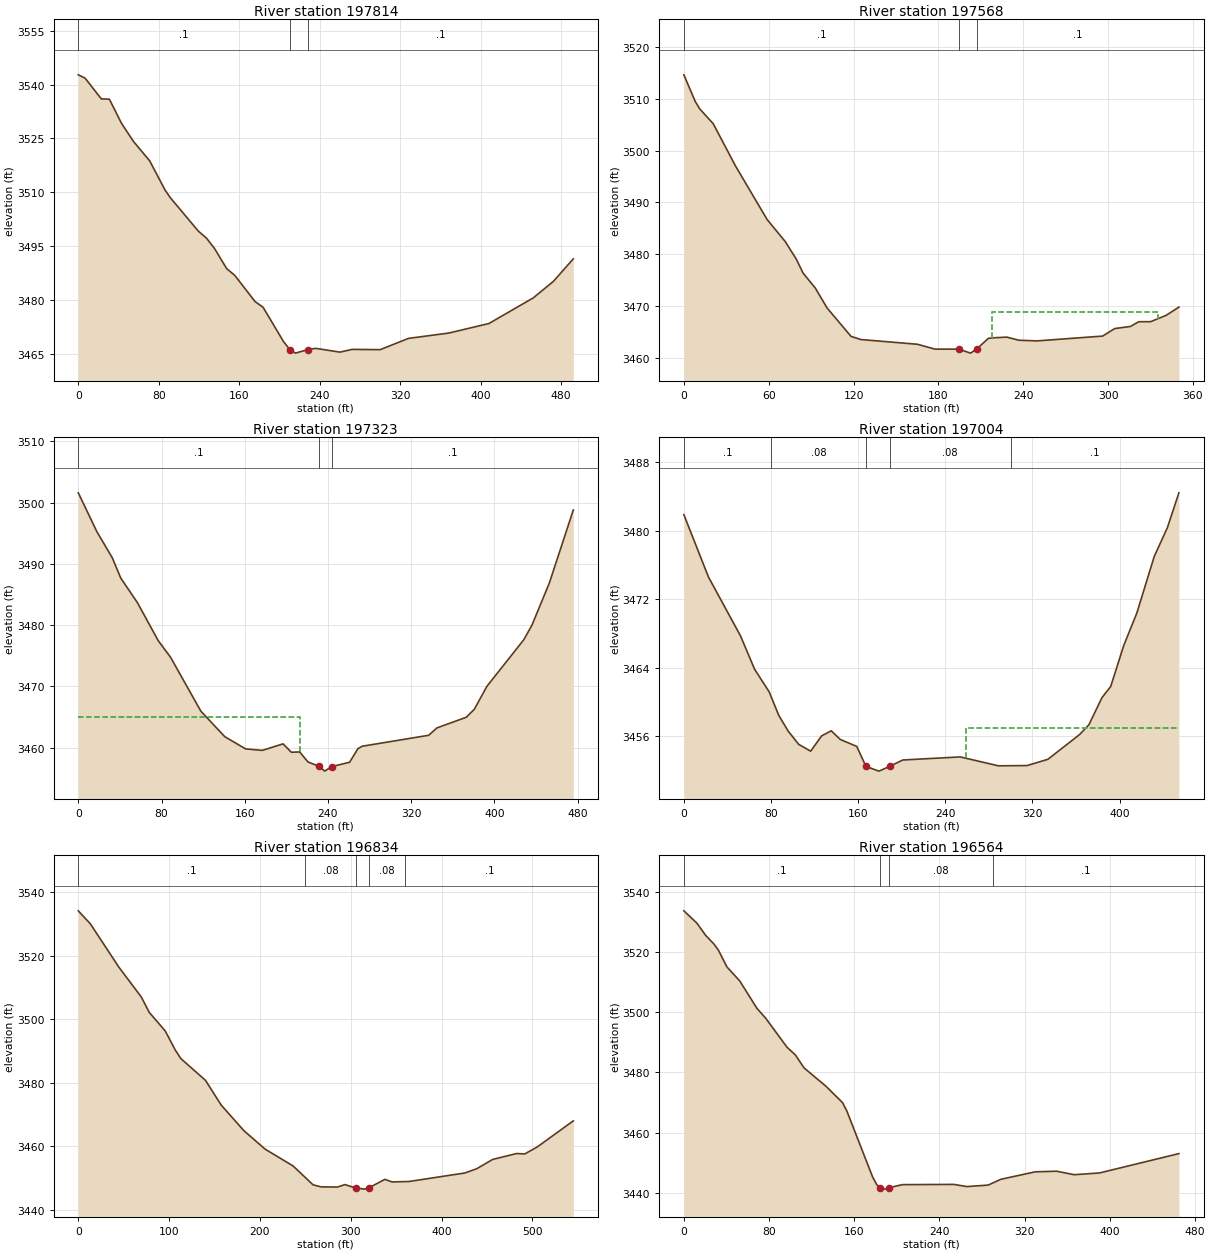
Type RM Length L Ch R = 1 ,197814  ,246,246,246
XS GIS Cut Line= 3
2340173.43053718614787.1773446842340449.02377415614758.470389854
2340663.98963794614762.804830438
#Sta/Elev= 30
       0  3542.7     6.8 3541.77    22.9    3536    30.9 3535.92      43 3529.17
      55 3524.11    71.1  3518.7    86.1 3510.71    91.2 3508.59   119.4 3499.17
   127.4 3497.25   135.5 3494.32   147.5 3488.75   155.6 3486.86   175.7 3479.58
   183.7 3477.99   203.8 3468.54   210.43466.136   215.9 3465.22     228 3466.19
     236 3466.55   260.1  3465.5   272.2 3466.26   300.2 3466.19   328.2 3469.32
   368.3 3470.81   408.2 3473.46   452.3  3480.6   472.3  3485.2   492.1 3491.48
#Mann= 3 ,-1,0
       0      .1       0   210.4    .045       0     228      .1       0
Bank Sta=210.4,228
XS Rating Curve= 0 ,0
Exp/Cntr=0.3,0.1

Type RM Length L Ch R = 1 ,197568  ,244.6,244.6,244.6
XS GIS Cut Line= 2
2340228.57690682614858.3270006332340558.98643288614973.970334754
#Sta/Elev= 30
       0 3514.61       8 3509.49    11.3 3508.01    20.8 3505.16    36.5 3497.03
    58.9 3486.68    71.6 3482.47    79.5 3479.05    84.3 3476.36      93 3473.45
   101.3 3469.62   118.2 3464.15   125.1 3463.53   165.2 3462.62   177.6 3461.68
   194.5 3461.68   202.8 3460.91   207.2 3461.74   215.4 3463.76   218.5 3463.86
   228.4    3464   236.9  3463.4   249.9 3463.27   296.2  3464.2   304.7 3465.65
   315.8 3466.05   321.7 3466.97   330.1 3466.98     341 3468.19   350.1 3469.79
#Mann= 3 ,-1,0
       0      .1       0   194.5    .045       0   207.2      .1       0
#XS Ineff= 1 ,-1
  218.12  335.57 3468.78
Permanent Ineff=
       F
Bank Sta=194.5,207.2
XS Rating Curve= 0 ,0
Exp/Cntr(USF)=0,0
Exp/Cntr=0.3,0.1

Type RM Length L Ch R = 1 ,197323  ,319.7,319.7,319.7
XS GIS Cut Line= 2
2340159.43179708615105.9155705352340635.17053718615114.710519805
#Sta/Elev= 30
       0 3501.59    17.8 3495.27    32.7 3490.98    40.8 3487.69    56.8 3483.68
    76.8 3477.48    88.8 3474.73   117.8 3465.97   140.8  3461.8   160.8 3459.81
   176.8 3459.56   196.8 3460.63   204.8 3459.26   212.8 3459.31   220.8 3457.67
   231.8 3456.95   236.8 3456.18   243.63456.916   260.8 3457.63   268.8 3459.85
   272.8 3460.24   336.8 3462.03   344.8 3463.24   372.8 3464.96   380.6 3466.26
   392.8 3470.03   428.2 3477.62     436 3479.98   452.8 3486.89   475.8 3498.79
#Mann= 3 ,-1,0
       0      .1       0   231.8    .045       0   243.6      .1       0
#XS Ineff= 2 , 0
          213.11    3465
Permanent Ineff=
       F       F
Bank Sta=231.8,243.6
XS Rating Curve= 0 ,0
Exp/Cntr=0.3,0.1

Type RM Length L Ch R = 1 ,197004  ,169.3,169.3,169.3
XS GIS Cut Line= 3
2340132.76352744615310.7584786472340470.75085536615462.552043248
2340554.70259553615461.899209746
#Sta/Elev= 30
       0 3481.88    22.6 3474.59      52 3467.72    64.9 3463.83    78.3 3461.19
    87.1 3458.44    95.8 3456.59   105.4 3455.05   116.4 3454.25   126.5 3456.04
   135.3 3456.63   143.6 3455.62   158.7 3454.81  167.18 3452.47   179.1 3451.92
     189 3452.48     201 3453.22   253.7 3453.58   288.8 3452.54   315.1 3452.57
   334.2  3453.3   363.3 3456.19   371.9 3457.34   383.9 3460.51   391.9 3461.81
   403.9 3466.61   415.9 3470.39   431.9 3477.01   443.9 3480.35   454.5 3484.43
#Mann= 5 ,-1,0
       0      .1       0      80     .08       0  167.18    .045       0
     189     .08       0     300      .1       0
#XS Ineff= 2 , 0
                           258.9         3456.99
Permanent Ineff=
       F       F
Bank Sta=167.18,189
XS Rating Curve= 0 ,0
Exp/Cntr(USF)=0,0
Exp/Cntr=0.3,0.1

Type RM Length L Ch R = 1 ,196834  ,269.9,269.9,269.9
XS GIS Cut Line= 2
 2339981.0914295615422.6562393392340476.80147808615649.067191352
#Sta/Elev= 30
       0 3534.16    13.3 3530.06    44.6 3516.44    69.4    3507    78.1 3502.17
    95.7 3496.31   106.9 3490.23   112.9  3487.6   140.1 3480.72   157.3 3472.95
   182.3 3464.88   205.7 3459.05   236.5 3453.75   258.4 3447.82   267.2 3447.16
   285.3 3447.11   293.6 3447.88   305.3  3446.8   315.2 3446.45     320 3446.88
   337.6 3449.53   345.3 3448.72     364 3448.85   425.5 3451.53   438.7 3452.88
   456.3 3455.82   482.7 3457.67   491.5 3457.54   505.3 3459.74     545 3467.97
#Mann= 5 ,-1,0
       0      .1       0     250     .08       0   305.3    .045       0
     320     .08       0     360      .1       0
Bank Sta=305.3,320
XS Rating Curve= 0 ,0
Exp/Cntr=0.3,0.1

Type RM Length L Ch R = 1 ,196564  ,300.9,300.9,300.9
XS GIS Cut Line= 2
2339919.88570645 615732.525824332340382.45904294615778.416036283
#Sta/Elev= 30
       0 3533.68    12.3 3529.57    20.4 3525.55    28.4 3522.59    32.4 3520.63
    40.5 3515.01    52.5 3510.37    68.6 3501.28    76.7 3498.06    96.8 3488.39
   104.8 3485.76   112.8 3481.51   133.5 3475.38     149 3469.95     153  3467.2
   177.2 3445.28   181.2 3442.65   184.53441.715   189.2 3441.22   192.43441.698
   205.3 3442.71   253.5 3442.79   265.6 3442.07   285.7 3442.56   297.7 3444.49
   329.9 3446.97     350 3447.17   366.5 3446.01   390.2 3446.59   464.8 3453.02
#Mann= 4 ,-1,0
       0      .1       0   184.5    .045       0   192.4     .08       0
     290      .1       0
Bank Sta=184.5,192.4
XS Rating Curve= 0 ,0
Exp/Cntr(USF)=0,0
Exp/Cntr=0.3,0.1

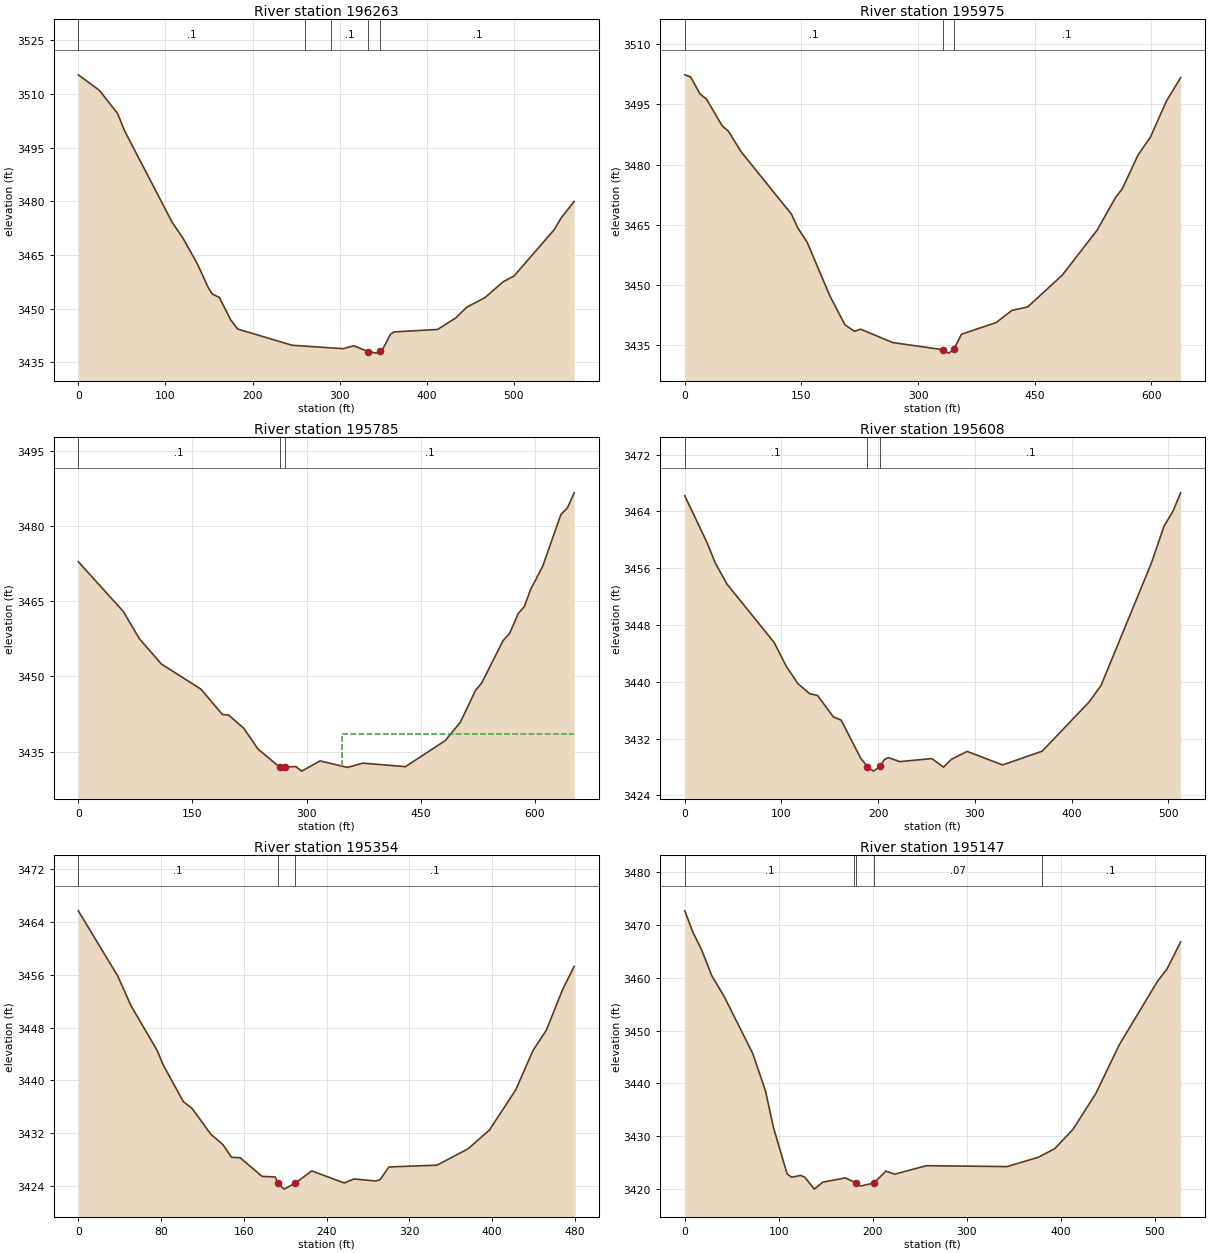
Type RM Length L Ch R = 1 ,196263  ,288.5,288.5,288.5
XS GIS Cut Line= 2
2339929.06374884616031.7300062632340474.23946684 615868.36085171
#Sta/Elev= 30
       0 3515.38    24.1 3511.05      45 3504.59    53.4 3499.56   107.6 3474.17
   120.4 3469.57   136.9 3462.38   149.1 3455.86   153.6 3454.09   161.9 3453.09
   174.8 3446.86   182.8 3444.27   245.4 3439.72   303.9 3438.77   316.4 3439.58
   332.3 3437.97   341.9 3437.52   346.7 3438.06   349.8 3438.82   358.2 3442.76
   362.4 3443.46   412.5 3444.15   433.3 3447.38   445.9 3450.38   466.8 3453.06
   487.6 3457.48   500.2 3459.12   546.1 3472.03   554.4 3475.42   569.1 3479.95
#Mann= 5 ,-1,0
       0      .1       0     260     .08       0     290      .1       0
   332.3    .045       0   346.7      .1       0
Bank Sta=332.3,346.7
XS Rating Curve= 0 ,0
Exp/Cntr(USF)=0,0
Exp/Cntr=0.3,0.1

Type RM Length L Ch R = 1 ,195975  ,189.5,189.5,189.5
XS GIS Cut Line= 2
 2339932.7349658616130.8528640822340562.34867379616231.811330378
#Sta/Elev= 30
       0 3502.33     7.5 3501.81    19.7 3497.53    27.8 3496.31      48 3489.66
    56.1  3488.3    72.4 3483.19   137.2 3467.64   145.3 3464.24   157.4 3460.64
   186.6 3447.29     206 3440.08   218.2 3438.48   226.3 3438.99   267.3 3435.67
   331.6 3433.91   339.7 3433.04     3463433.991   355.9 3437.75   400.5 3440.66
   420.7 3443.68     441 3444.54   485.6 3452.49   530.1 3463.61   554.4 3471.91
   562.5  3473.9   582.8 3482.32     599 3486.88   619.5 3495.82   637.7 3501.63
#Mann= 3 ,-1,0
       0      .1       0   331.6    .045       0     346      .1       0
Bank Sta=331.6,346
XS Rating Curve= 0 ,0
Exp/Cntr(USF)=0,0
Exp/Cntr=0.3,0.1

Type RM Length L Ch R = 1 ,195785  ,176.9,176.9,176.9
XS GIS Cut Line= 3
2339899.29171564616322.5962393392340273.48133412 616350.20452429
2340549.59266528616365.057714455
#Sta/Elev= 30
       0 3472.87    59.3 3462.92    80.4 3457.49   109.2 3452.49   161.3 3447.46
   189.4 3442.42   197.4 3442.33   217.5 3439.67   236.3 3435.52   264.53431.955
   272.2 3431.95   285.7 3432.05   293.7 3431.14   317.7 3433.18   353.8 3431.88
   373.9 3432.73     430 3432.03   482.1 3437.21   502.1 3440.88   522.1 3447.25
   530.1 3448.68   558.2 3457.13   566.9  3458.6   578.2 3462.54   586.2 3463.93
   594.2 3467.26   610.2  3471.9   634.3 3482.29   642.9  3483.6   651.7  3486.6
#Mann= 3 ,-1,0
       0      .1       0   264.5    .045       0   272.2      .1       0
#XS Ineff= 2 , 0
                          346.48         3438.54
Permanent Ineff=
       F       F
Bank Sta=264.5,272.2
XS Rating Curve= 0 ,0
Exp/Cntr=0.3,0.1

Type RM Length L Ch R = 1 ,195608  ,254,254,254
XS GIS Cut Line= 2
 2339997.3043724616530.442652534 2340501.0769214616434.583098677
#Sta/Elev= 30
       0 3466.21    23.3 3459.53    31.4 3456.78    43.6 3453.78    92.5 3445.53
   104.7 3442.25   116.9 3439.76   129.1 3438.33   137.3 3438.08   153.6 3435.07
   161.7  3434.6   182.1  3429.2   188.93428.052   195.1 3427.42   201.9 3428.08
   206.5 3429.06   210.6 3429.33   222.5 3428.76   255.4 3429.19   267.6 3427.99
   275.7 3429.08     292  3430.2   328.7 3428.29   369.6 3430.23   418.2 3437.17
   430.5 3439.49   482.5 3456.71   495.6 3461.92   504.9 3464.05   512.8 3466.63
#Mann= 3 ,-1,0
       0      .1       0   188.9    .045       0   201.9      .1       0
Bank Sta=188.9,201.9
XS Rating Curve= 0 ,0
Exp/Cntr(USF)=0,0
Exp/Cntr=0.3,0.1

Type RM Length L Ch R = 1 ,195354  ,207.3,207.3,207.3
XS GIS Cut Line= 2
2340072.03566713616727.7452710212340525.67575191616572.381056289
#Sta/Elev= 30
       0 3465.67    38.2 3455.78    50.9 3451.32    76.3 3444.53      82 3442.38
   101.6 3436.79   110.1 3435.76   128.1 3431.87   139.7 3430.32   148.1 3428.39
   156.5 3428.31   177.7 3425.49   190.4  3425.4   193.1 3424.43   198.9 3423.56
     210 3424.48   225.7 3426.32   257.2 3424.49   266.5  3425.1   287.7 3424.79
   291.9    3425   300.3 3426.91   346.9 3427.19   376.9 3429.66   397.6 3432.51
     423 3438.58   439.8 3444.57   452.7 3447.64   468.2 3453.71   479.5 3457.26
#Mann= 3 ,-1,0
       0      .1       0   193.1    .045       0     210      .1       0
Bank Sta=193.1,210
XS Rating Curve= 0 ,0
Exp/Cntr=0.3,0.1

Type RM Length L Ch R = 1 ,195147  ,223.8,223.8,223.8
XS GIS Cut Line= 2
2340157.08086446616952.8207910032340598.67319604616663.778537604
#Sta/Elev= 30
       0 3472.69     8.5 3468.69      18 3465.27    28.6 3460.44    41.9 3456.47
    72.4 3445.64    85.8 3438.64    94.5 3431.57   108.9 3422.87   113.7 3422.23
   123.3 3422.59     128  3422.2   137.8 3419.98   147.1 3421.31     171 3422.11
   181.9 3421.18   186.9 3420.57   201.3 3421.12     214 3423.39   223.6 3422.81
   257.1 3424.42   343.1 3424.25   376.6 3426.03   393.8 3427.65   413.3 3431.32
   437.6 3438.11   462.6 3447.35   503.3 3459.38   513.4 3461.69   527.8 3466.79
#Mann= 5 ,-1,0
       0      .1       0     180     .08       0   181.9    .045       0
   201.3     .07       0     380      .1       0
Bank Sta=181.9,201.3
XS Rating Curve= 0 ,0
Exp/Cntr(USF)=0,0
Exp/Cntr=0.3,0.1

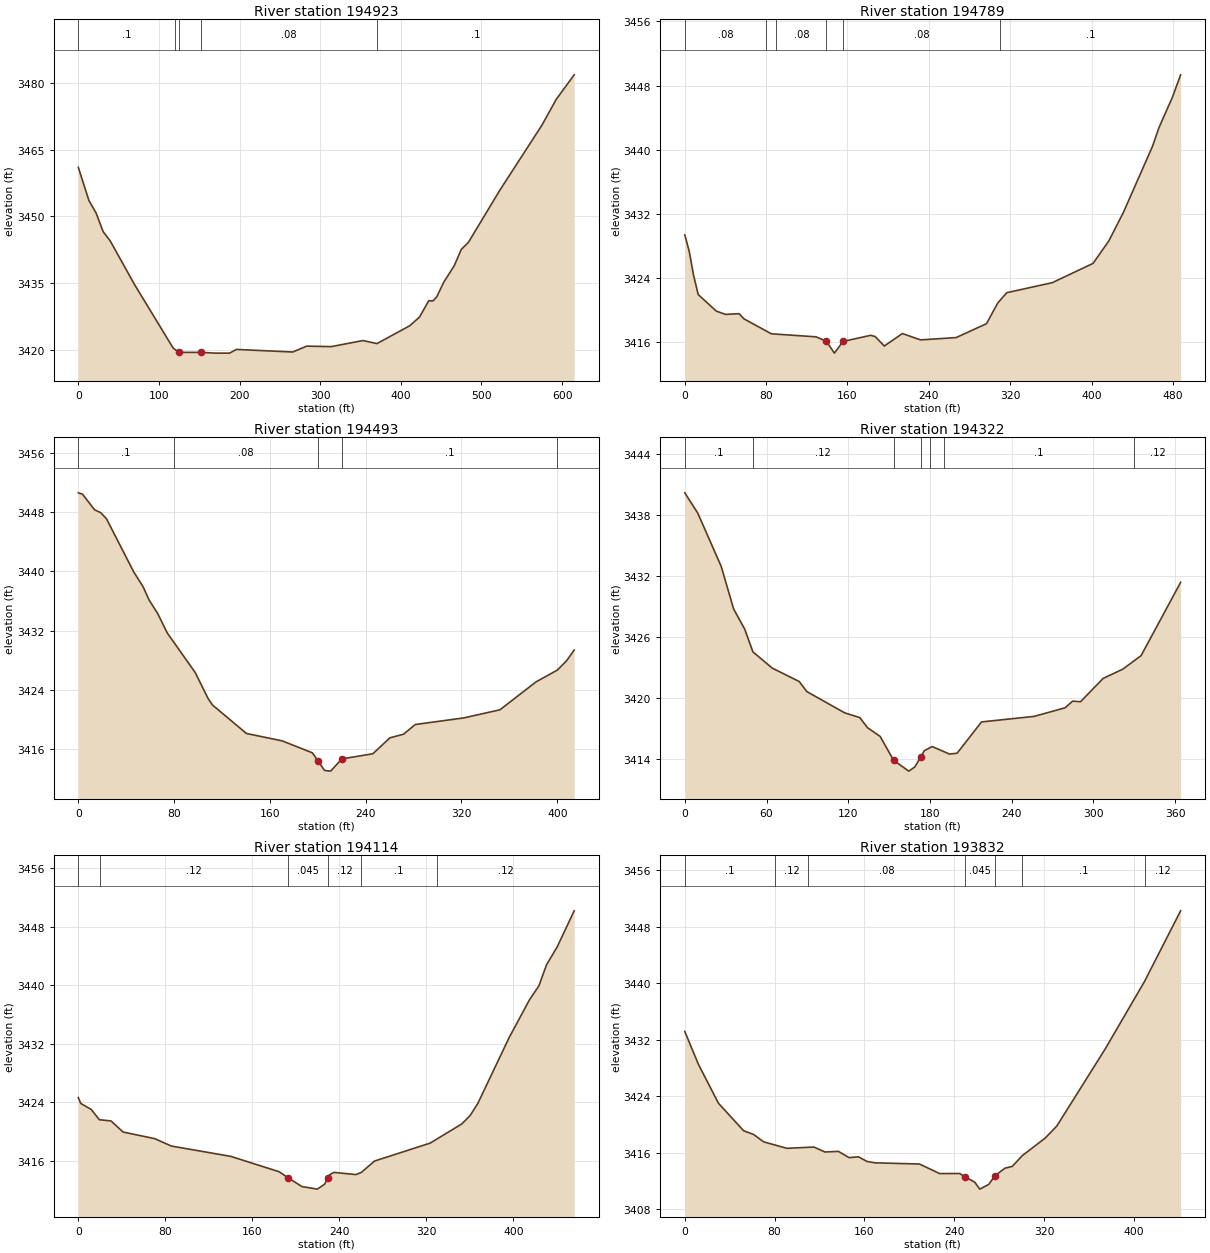
Type RM Length L Ch R = 1 ,194923  ,134.2,134.2,134.2
XS GIS Cut Line= 2
2340232.01774497617085.2984904772340796.72066596616841.753628817
#Sta/Elev= 30
       0 3461.01    13.2 3453.56      22 3450.79    30.7 3446.62    39.4 3444.57
    69.9 3434.68   117.8 3420.45     125 3419.53   152.6 3419.53   170.1 3419.36
   187.5 3419.36   196.2 3420.19   265.9 3419.61   283.3 3420.93   313.8 3420.82
     353 3422.18   370.4  3421.5   411.1  3425.5   423.3 3427.47   434.6 3431.09
   440.1 3431.08   444.6    3432   453.2 3435.24   466.3 3438.96     475 3442.62
   483.7 3444.16   522.9 3455.91   575.2 3470.52   592.6 3476.21     615 3481.76
#Mann= 5 ,-1,0
       0      .1       0     120     .08       0     125    .045       0
   152.6     .08       0     370      .1       0
Bank Sta=125,152.6
XS Rating Curve= 0 ,0
Exp/Cntr(USF)=0,0
Exp/Cntr=0.3,0.1

Type RM Length L Ch R = 1 ,194789  ,296.6,296.6,296.6
XS GIS Cut Line= 3
2340324.35548071617170.9454333092340658.39472455617005.625628226
2340729.36215538616915.222126537
#Sta/Elev= 30
       0 3429.37     4.3 3427.37     8.7  3424.3    13.2 3421.94      31 3419.88
      40 3419.47    53.4 3419.56    58.1 3418.92    85.1 3417.05   129.2 3416.67
   139.3 3416.11   147.1 3414.64  155.69  3416.1   182.8 3416.86   187.2 3416.71
   196.2 3415.53     214 3417.08   231.9 3416.29   266.9 3416.58   296.7 3418.31
   307.8  3420.9   316.7 3422.18   361.3 3423.42   401.5 3425.83     417 3428.63
   431.3 3432.18   459.8 3440.38   466.3 3442.75   479.7  3446.6   487.6 3449.34
#Mann= 6 ,-1,0
       0     .08       0      80      .1       0      90     .08       0
   139.3    .045       0  155.69     .08       0     310      .1       0
Bank Sta=139.3,155.69
XS Rating Curve= 0 ,0
Exp/Cntr(USF)=0,0
Exp/Cntr=0.3,0.1

Type RM Length L Ch R = 1 ,194493  ,170.7,170.7,170.7
XS GIS Cut Line= 2
2340237.37037929617191.0130183412340565.21923153617443.924990064
#Sta/Elev= 30
       0 3450.62     3.5 3450.44    13.6 3448.32    18.7 3447.94    23.5 3447.12
    46.3 3439.92    54.1 3437.93    59.1 3436.13    66.3  3434.3    74.3 3431.67
    97.7 3426.31   108.3 3422.84   111.9 3421.96   140.4 3418.09   170.3 3417.09
   195.5 3415.47   200.13414.393   205.6  3413.1   210.7    3413   220.13414.653
     246 3415.35   260.2  3417.5   271.6 3417.99   281.4  3419.3   321.8 3420.19
   352.1 3421.29   382.4 3425.08     400 3426.65   407.7 3427.91   414.1 3429.36
#Mann= 5 ,-1,0
       0      .1       0      80     .08       0   200.1    .045       0
   220.1      .1       0     400     .12       0
Bank Sta=200.1,220.1
XS Rating Curve= 0 ,0
Exp/Cntr(USF)=0,0
Exp/Cntr=0.3,0.1

Type RM Length L Ch R = 1 ,194322  ,208.4,208.4,208.4
XS GIS Cut Line= 2
2340176.11453073617302.5197863732340436.89585806617556.403286728
#Sta/Elev= 30
       0 3440.16     9.5 3438.17    26.7 3432.93    35.9 3428.71      44 3426.74
      50 3424.51    64.2 3422.91      84 3421.59    89.6  3420.6   117.3 3418.51
   128.5 3418.04   134.1 3417.05   143.4 3416.19   153.33413.837   164.4 3412.77
   168.8 3413.17   173.1 3414.14   175.8 3414.78   181.6 3415.19   194.3 3414.45
   199.9 3414.53   217.8 3417.61   256.5 3418.16   279.1    3419   284.8 3419.66
   290.5  3419.6   307.1 3421.89   321.6 3422.81     335 3424.14     364 3431.35
#Mann= 7 ,-1,0
       0      .1       0      50     .12       0   153.3    .045       0
   173.1     .12       0     180     .08       0     190      .1       0
     330     .12       0
Bank Sta=153.3,173.1
XS Rating Curve= 0 ,0
Exp/Cntr=0.3,0.1

Type RM Length L Ch R = 1 ,194114  ,281.9,281.9,281.9
XS GIS Cut Line= 2
2339994.37416061 617448.059437552340369.05856317617707.662202177
#Sta/Elev= 30
       0 3424.66     2.2 3423.86    11.9 3423.03    19.3 3421.63    30.1 3421.46
    41.1 3419.95    70.3 3419.04    85.5 3418.03   140.1 3416.62   184.6 3414.52
   192.8 3413.69   205.6 3412.49   219.7 3412.14   226.3  3412.8   229.2 3413.62
   230.9  3414.1   234.9 3414.43   255.2 3414.13   260.1 3414.42   272.3 3415.98
   323.4 3418.43   352.6 3421.06   360.2 3422.21   367.2 3423.84   395.9 3432.82
   414.6 3437.99   423.4 3439.94   430.4 3442.81   440.2 3445.26   455.8 3450.19
#Mann= 6 ,-1,0
       0      .1       0      20     .12       0   192.8    .045       0
   229.2     .12       0     260      .1       0     330     .12       0
Bank Sta=192.8,229.2
XS Rating Curve= 0 ,0
Exp/Cntr(USF)=0,0
Exp/Cntr=0.3,0.1

Type RM Length L Ch R = 1 ,193832  ,210.8,210.8,210.8
XS GIS Cut Line= 2
2339841.39472988 617684.319629242340236.05346483617882.724599028
#Sta/Elev= 30
       0 3433.16    12.1 3428.53      30 3423.01    52.4 3419.13    61.3  3418.6
    70.3 3417.55      91 3416.64     115 3416.82   124.9 3416.12   136.8 3416.21
   146.4 3415.32   154.7 3415.44   162.2 3414.79   169.5 3414.59   209.1 3414.42
     227 3413.07   244.9 3413.08   249.3 3412.63   258.3 3411.85   262.8 3410.87
   270.8 3411.54   276.2 3412.75   285.2 3413.83   291.7 3414.08   300.6  3415.6
     321 3418.08   331.4 3419.79   374.7 3430.74   409.5 3440.22   441.7 3450.22
#Mann= 7 ,-1,0
       0      .1       0      80     .12       0     110     .08       0
   249.3    .045       0   276.2     .08       0     300      .1       0
     410     .12       0
Bank Sta=249.3,276.2
XS Rating Curve= 0 ,0
Exp/Cntr=0.3,0.1

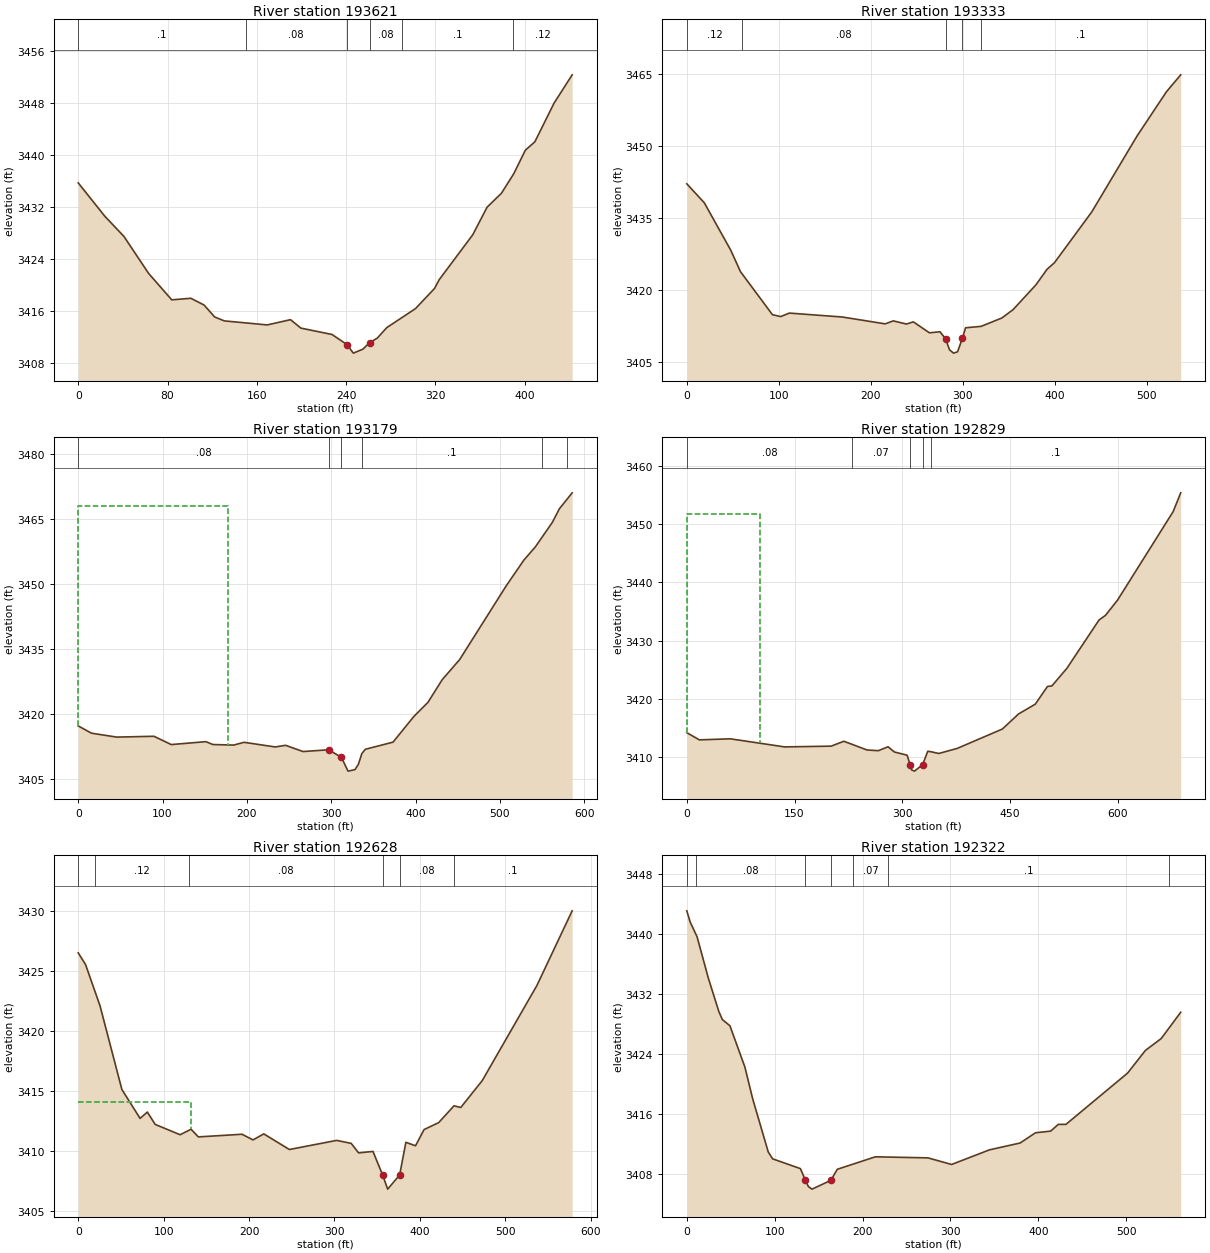
Type RM Length L Ch R = 1 ,193621  ,288.2,288.2,288.2
XS GIS Cut Line= 2
2339745.90322831617873.9392098392340159.39422971618031.841922344
#Sta/Elev= 30
       0 3435.75    23.8 3430.62      41  3427.5    63.1 3421.81    83.8 3417.75
   100.9 3417.99   112.7 3416.96   122.3 3415.11   130.9 3414.51   169.4 3413.89
   190.2  3414.7   199.5  3413.4   227.4 3412.42   240.8 3410.87   246.5 3409.55
   255.1 3410.16     2613411.156   267.9 3411.85   276.5 3413.48   302.2  3416.4
   319.3 3419.51   323.4 3420.84   353.5 3427.76   366.4 3432.02   379.2 3434.15
   390.3 3437.17   400.6 3440.77   409.2 3442.08   426.3    3448   442.6 3452.38
#Mann= 6 ,-1,0
       0      .1       0     150     .08       0   240.8    .045       0
     261     .08       0     290      .1       0     390     .12       0
Bank Sta=240.8,261
XS Rating Curve= 0 ,0
Exp/Cntr(USF)=0,0
Exp/Cntr=0.3,0.1

Type RM Length L Ch R = 1 ,193333  ,153.7,153.7,153.7
XS GIS Cut Line= 3
2339618.75409822618099.6357987032339940.08673206618241.158411869
2340124.23524716618266.671216045
#Sta/Elev= 30
       0 3442.12      19 3438.17    47.8 3428.26    58.4 3423.77    93.1  3414.8
   102.1  3414.4   111.5 3415.13   169.1 3414.31   215.7 3412.88   224.5  3413.5
   238.9 3412.84   246.3  3413.3   263.8 3411.01   275.3 3411.23   281.3 3409.76
   285.7 3407.45     290 3406.77   294.4 3407.05   299.6 3409.85   303.1 3412.06
     320 3412.36   342.5  3414.1   354.8 3415.86   379.6 3421.03   391.6 3424.26
   399.7 3425.64   440.3 3436.25   489.5 3452.09   521.5 3461.34     537 3464.87
#Mann= 5 ,-1,0
       0     .12       0      60     .08       0   281.3    .045       0
   299.6     .08       0     320      .1       0
Bank Sta=281.3,299.6
XS Rating Curve= 0 ,0
Exp/Cntr=0.3,0.1

Type RM Length L Ch R = 1 ,193179  ,349.7,349.7,349.7
XS GIS Cut Line= 4
2339651.31010779618206.4419023142339688.85655946618306.526454229
2339973.88198149618373.5708774972340150.58063733618315.583177262
#Sta/Elev= 30
       0 3417.27    15.7 3415.59    45.6 3414.69    89.8 3414.88   110.3 3412.97
   151.4 3413.64   159.6 3412.98   184.3 3412.85   196.6 3413.49   233.6 3412.42
   245.9  3412.8   266.5 3411.36296.82033411.762312.05153410.043   319.9 3406.85
   328.1 3407.19   332.2 3408.42   336.3 3410.89   340.4 3411.88   373.3 3413.53
     398 3419.45   414.7  3422.7   431.6 3427.92   452.3 3432.56   507.4 3449.51
   528.4 3455.46   542.1 3458.53   562.1 3464.14   570.5 3467.28   585.7 3470.97
#Mann= 6 ,-1,0
       0     .08       0296.8203    .045       0312.0515     .08       0
   336.9      .1       0   549.7     .12       0   579.7      .1       0
#XS Ineff= 2 , 0
        177.6639 3468.04
Permanent Ineff=
       F       F
Bank Sta=296.8203,312.0515
XS Rating Curve= 0 ,0
Exp/Cntr(USF)=0,0
Exp/Cntr=0.3,0.1

Type RM Length L Ch R = 1 ,192829  ,201.6,201.6,201.6
XS GIS Cut Line= 3
2339583.64237529618320.2418262192339763.65579462618642.863584522
2339908.01582306618926.537365581
#Sta/Elev= 30
       0 3414.19    17.5 3412.95    60.6 3413.13   136.3 3411.74     201 3411.87
   218.7 3412.71     251 3411.21   266.7 3411.09   280.2 3411.76   289.2 3410.86
   306.8 3410.32  310.82 3408.71     313 3407.79   317.1 3407.58  328.48 3408.71
   335.5 3410.99     340 3410.91   350.9 3410.61   376.5 3411.48   439.4 3414.81
   461.8 3417.39   485.2 3419.08   502.2 3422.12   508.4 3422.22   529.1 3425.22
     574 3433.54     583 3434.34   599.9 3436.98   677.2 3452.16   687.7 3455.38
#Mann= 5 ,-1,0
       0     .08       0     230     .07       0  310.82    .045       0
  328.48     .07       0     340      .1       0
#XS Ineff= 2 , 0
          102.18 3451.81
Permanent Ineff=
       F       F
Bank Sta=310.82,328.48
XS Rating Curve= 0 ,0
Exp/Cntr=0.3,0.1

Type RM Length L Ch R = 1 ,192628  ,305.9,305.9,305.9
XS GIS Cut Line= 2
2339445.03987774618305.2327065022339644.91267404618847.870728336
#Sta/Elev= 30
       0 3426.49     8.6 3425.51    25.5 3422.08    51.1 3415.11    72.4  3412.7
    80.9 3413.23    90.1  3412.2   119.3 3411.34   132.1  3411.8   140.6 3411.16
   191.8 3411.38   204.6 3410.91   217.3 3411.41   247.2 3410.11   302.6 3410.87
   319.6 3410.62   328.2 3409.83   345.1 3409.95   356.3    3408   362.3 3406.81
  376.31 3407.99   383.6 3410.71   394.9 3410.42   404.9 3411.77     422 3412.35
     440 3413.75   447.9 3413.61   473.1 3415.86     537 3423.77   578.3 3429.99
#Mann= 6 ,-1,0
       0      .1       0      20     .12       0     130     .08       0
   356.3    .045       0  376.31     .08       0     440      .1       0
#XS Ineff= 2 , 0
           131.6 3414.05
Permanent Ineff=
       F       F
Bank Sta=356.3,376.31
XS Rating Curve= 0 ,0
Exp/Cntr(USF)=0,0
Exp/Cntr=0.3,0.1

Type RM Length L Ch R = 1 ,192322  ,246.8,246.8,246.8
XS GIS Cut Line= 4
2339241.26100886618410.8100717472339306.23866946618533.941594483
2339312.31710059618562.9915220762339464.25347415618925.632269551
#Sta/Elev= 30
       0 3443.06     3.9 3441.56    11.7 3439.61    24.6 3434.08    36.5 3429.65
    40.5 3428.59    49.1 3427.76    66.1 3422.28      75 3418.04    92.7 3410.97
    97.7 3410.05   129.3 3408.75  135.07 3407.19   138.4 3406.36   142.5 3406.02
163.93873407.185   171.3 3408.66   214.6 3410.32   274.4 3410.18   301.4  3409.3
   344.5 3411.25   379.4 3412.16   396.8 3413.52   414.1 3413.74   422.8 3414.64
   431.5 3414.64   501.7 3421.47   521.9 3424.48   539.9 3426.06   562.1 3429.56
#Mann= 7 ,-1,0
       0      .1       0      10     .08       0  135.07    .045       0
163.9387     .08       0   188.9     .07       0   228.9      .1       0
   548.9     .12       0
Bank Sta=135.07,163.9387
XS Rating Curve= 0 ,0
Exp/Cntr=0.3,0.1