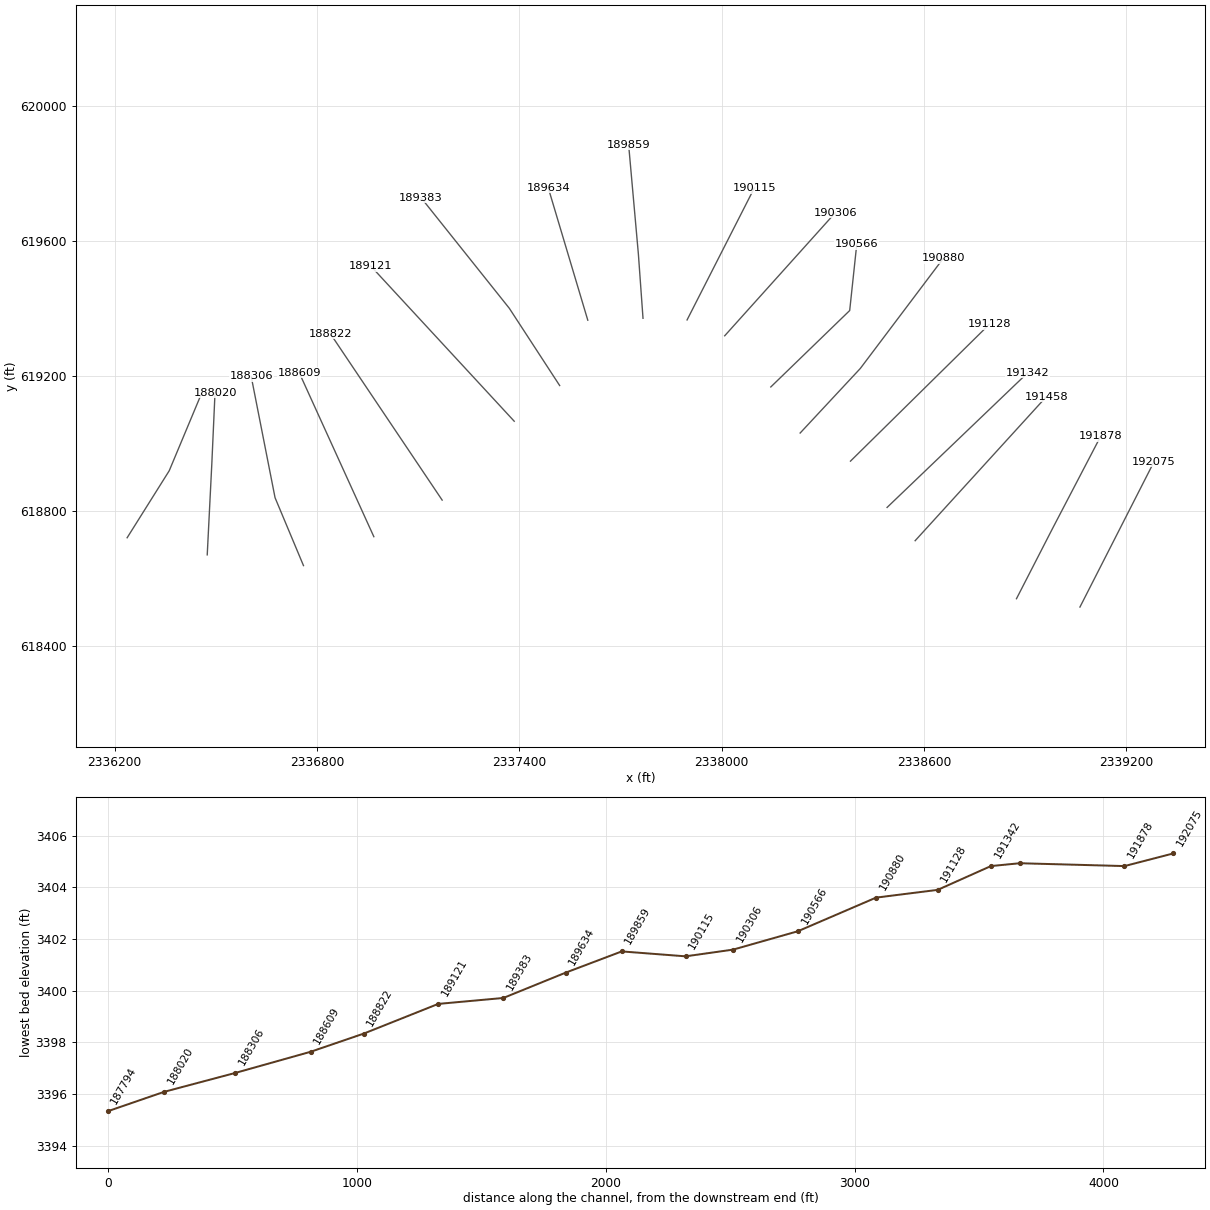
HEC-RAS study LAURELFK.prj: LAURELFK

--- LAURELFK.g01 (geometry) --- (continued)

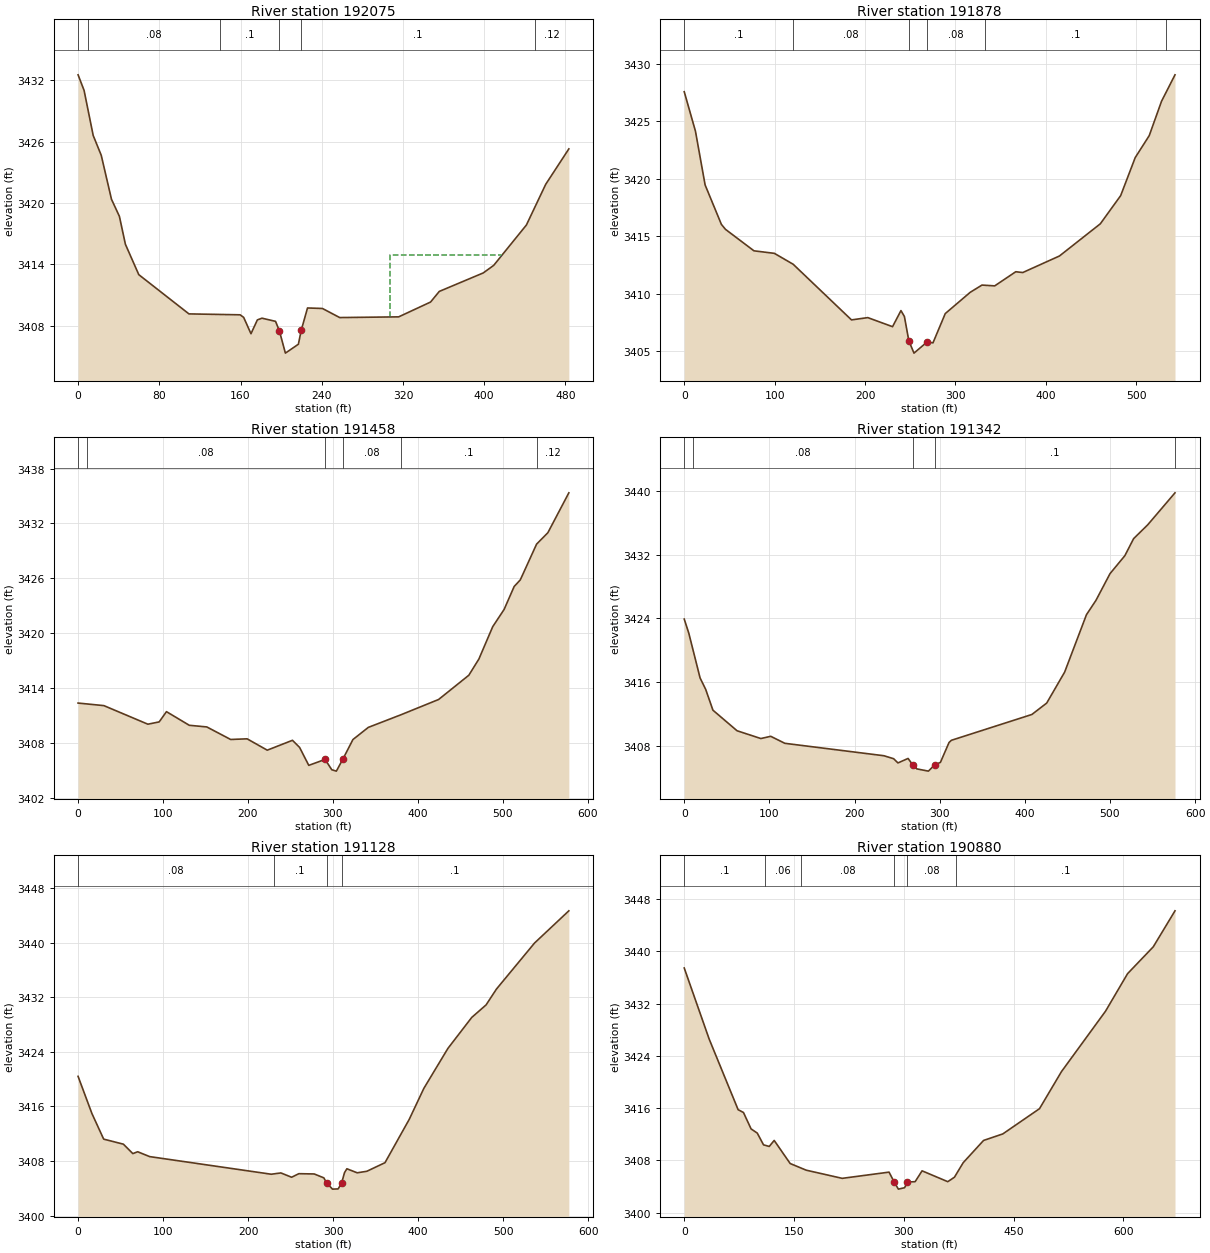
Type RM Length L Ch R = 1 ,192075  ,196.7,196.7,196.7
XS GIS Cut Line= 2
2339062.72654878618515.9092913782339282.54632949618946.484119579
#Sta/Elev= 30
       0 3432.55     5.9 3431.03    14.9 3426.61    22.8 3424.68    32.9 3420.37
    40.7  3418.7    46.6 3415.97    59.8 3412.99   109.2 3409.15   159.6 3409.06
   163.1 3408.81   170.3 3407.21   176.6 3408.56   181.1 3408.73   194.5 3408.42
   198.3 3407.49   204.2 3405.31     217 3406.18   219.8 3407.54     226 3409.73
   240.7 3409.68   257.7 3408.79   315.8 3408.86   347.2 3410.31   355.8 3411.35
   399.1 3413.16   409.4  3413.9   441.6 3417.85   460.6 3421.83   483.4  3425.3
#Mann= 6 ,-1,0
       0      .1       0      10     .08       0     140      .1       0
   198.3    .045       0   219.8      .1       0     450     .12       0
#XS Ineff= 1 ,-1
  307.05  416.11  3414.9
Permanent Ineff=
       F
Bank Sta=198.3,219.8
XS Rating Curve= 0 ,0
Exp/Cntr(USF)=0,0
Exp/Cntr=0.3,0.1

Type RM Length L Ch R = 1 ,191878  ,420.8,420.8,420.8
XS GIS Cut Line= 3
2338874.50290498618540.6298111342338980.83642867618747.426761849
2339124.56428531619022.430141709
#Sta/Elev= 30
       0 3427.56    12.4 3424.13    23.1 3419.45    41.1 3416.02    45.6 3415.59
    77.1 3413.72    99.7  3413.5   120.5 3412.55     185 3407.71     203 3407.91
   230.4 3407.12   239.7 3408.52   243.5 3408.01   248.4  3405.9   254.1 3404.82
   268.9 3405.81   275.1 3405.71   288.7 3408.26   316.3 3410.11   329.3 3410.74
   343.4 3410.67   366.7  3411.9   374.4 3411.83     415 3413.27   460.2 3416.07
   482.7 3418.52   498.8 3421.83   514.3 3423.74   527.9 3426.73   542.8 3429.03
#Mann= 6 ,-1,0
       0      .1       0     120     .08       0   248.4    .045       0
   268.9     .08       0  332.53      .1       0  532.53     .12       0
Bank Sta=248.4,268.9
XS Rating Curve= 0 ,0
Exp/Cntr=0.3,0.1

Type RM Length L Ch R = 1 ,191458  ,115.9,115.9,115.9
XS GIS Cut Line= 2
2338574.00508153618712.4299950532338963.56382042619139.434247933
#Sta/Elev= 30
       0 3412.37    30.4 3412.09    82.2 3410.06    95.5 3410.31   104.1 3411.43
     131 3409.94   151.6 3409.76   179.7 3408.39   199.1 3408.46   222.8 3407.22
   252.5  3408.3   260.9 3407.52   271.7 3405.56   290.9 3406.21   298.8 3405.08
   304.2 3404.93   311.8 3406.23   323.7 3408.38   341.8 3409.71     380 3411.08
   424.6 3412.76   460.2 3415.41   472.1 3417.19   488.3 3420.71   501.8 3422.61
   513.6 3425.11   520.8 3425.83     540 3429.74   553.3 3430.99     578 3435.35
#Mann= 6 ,-1,0
       0      .1       0      10     .08       0   290.9    .045       0
   311.8     .08       0     380      .1       0     540     .12       0
Bank Sta=290.9,311.8
XS Rating Curve= 0 ,0
Exp/Cntr(USF)=0,0
Exp/Cntr=0.3,0.1

Type RM Length L Ch R = 1 ,191342  ,213.7,213.7,213.7
XS GIS Cut Line= 2
2338490.75823673618810.944236733 2338907.2903801619209.342665879
#Sta/Elev= 30
       0  3423.9     5.4 3422.12    18.6 3416.52    25.2 3415.08    33.7 3412.47
      62 3409.89      90 3408.91   101.6 3409.19   118.2 3408.31   234.6 3406.75
   245.9 3406.38     251 3405.85   262.9 3406.41   268.5 3405.59   273.2  3405.1
   286.8 3404.82     294 3405.59   300.9 3405.92     311 3408.41   313.8 3408.69
   408.3 3411.93   425.7 3413.36   446.8 3417.25   472.4 3424.45   483.6 3426.26
   500.1 3429.61   517.5 3431.86   527.8    3434   544.4 3435.74   576.4 3439.75
#Mann= 5 ,-1,0
       0      .1       0      10     .08       0   268.5    .045       0
     294      .1       0  576.39     .12       0
Bank Sta=268.5,294
XS Rating Curve= 0 ,0
Exp/Cntr=0.3,0.1

Type RM Length L Ch R = 1 ,191128  ,247.7,247.7,247.7
XS GIS Cut Line= 2
2338382.19741303618948.0865472612338793.55727297619352.838216687
#Sta/Elev= 30
       0 3420.41    16.3 3414.96    30.1 3411.22    53.3 3410.48    64.4  3409.1
    70.1 3409.37    84.2 3408.66   227.2 3406.08   238.5 3406.27   251.1 3405.64
   259.6 3406.16   277.7 3406.12     289 3405.55   292.4 3404.78   299.2  3403.9
   305.8 3403.93   309.83404.746   313.3 3406.31   316.1 3406.88   328.2 3406.29
   339.5 3406.51   360.9 3407.77   389.4 3414.11   406.6 3418.65   434.9  3424.5
   462.9 3429.03   479.8 3430.87     492 3433.19   536.8 3439.93   577.1 3444.64
#Mann= 4 ,-1,0
       0     .08       0     230      .1       0   292.4    .045       0
   309.8      .1       0
Bank Sta=292.4,309.8
XS Rating Curve= 0 ,0
Exp/Cntr(USF)=0,0
Exp/Cntr=0.3,0.1

Type RM Length L Ch R = 1 ,190880  ,314,314,314
XS GIS Cut Line= 3
2338232.95888871619031.3434048262338411.38534155619222.576250029
2338657.71412984619548.953816136
#Sta/Elev= 30
       0 3437.44      34 3426.58    73.6 3415.76    80.9 3415.33    91.3 3412.82
    99.8 3412.17   108.3 3410.38   116.1 3410.13   122.9 3411.05   144.7 3407.52
   166.6  3406.5   215.8 3405.25   279.8  3406.2   286.8 3404.69   292.5  3403.6
   301.1 3403.82   304.9 3404.68   315.4 3404.74   324.9  3406.4     360 3404.74
   369.1 3405.42   381.1 3407.65   408.9 3411.05   435.2 3412.05   485.3 3415.91
   515.3 3421.58   575.5 3430.83   605.6 3436.57   640.7 3440.68   670.4 3446.19
#Mann= 6 ,-1,0
       0      .1       0     110     .06       0     160     .08       0
   286.8    .045       0   304.9     .08       0  371.55      .1       0
Bank Sta=286.8,304.9
XS Rating Curve= 0 ,0
Exp/Cntr=0.3,0.1

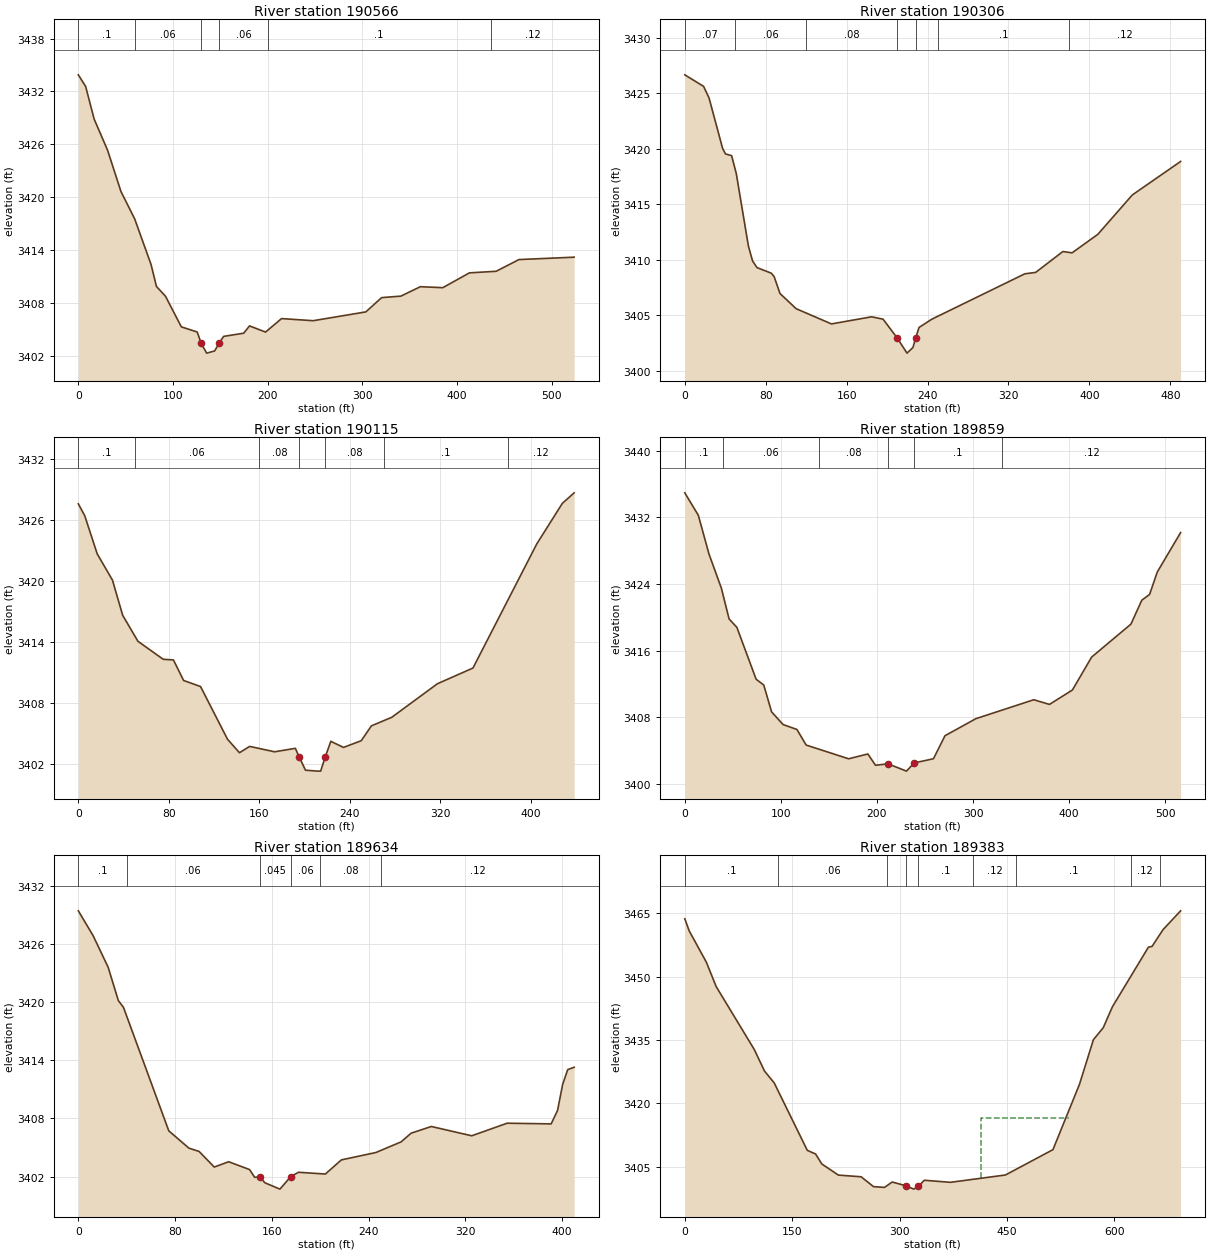
Type RM Length L Ch R = 1 ,190566  ,260,260,260
XS GIS Cut Line= 3
2338145.95460189619167.8088820922338379.86415988619394.103157323
2338400.92696046619591.095212286
#Sta/Elev= 30
       0 3433.89     7.7 3432.58    16.7 3428.87    30.9 3425.33      45 3420.65
    59.5 3417.54    76.8 3412.36    82.5 3409.87    92.1 3408.75   108.8 3405.28
   125.5  3404.7   129.8  3403.4   135.5  3402.3     144 3402.55148.6991 3403.43
   153.4  3404.2   174.6 3404.56   180.8 3405.39   197.7 3404.69   214.6 3406.22
     248 3405.98   303.6 3406.98   320.3  3408.6   340.6 3408.77   361.2 3409.84
   384.9 3409.73     413 3411.41   441.2 3411.59   465.3 3412.92   523.6 3413.19
#Mann= 6 ,-1,0
       0      .1       0      60     .06       0   129.8    .045       0
148.6991     .06       0     200      .1       0  435.46     .12       0
Bank Sta=129.8,148.6991
XS Rating Curve= 0 ,0
Exp/Cntr(USF)=0,0
Exp/Cntr=0.3,0.1

Type RM Length L Ch R = 1 ,190306  ,191.1,191.1,191.1
XS GIS Cut Line= 2
2338009.22520035619319.3626844142338337.15545323619683.708257119
#Sta/Elev= 30
       0 3426.65    18.6 3425.61      24 3424.56    37.4 3420.02    40.2 3419.53
    46.3 3419.37    50.9 3417.76    62.9 3411.23      67 3409.89    71.4 3409.29
    85.5 3408.79    88.3 3408.49    94.1 3406.96   110.1 3405.59     145 3404.22
   184.6 3404.86     196 3404.65209.8005 3402.98   219.7 3401.59   225.6  3402.1
  228.22 3402.96   231.6  3403.9   244.1 3404.64   336.1 3408.73   346.9 3408.86
   373.8 3410.74   382.9 3410.62   408.4 3412.29   442.4 3415.83   490.2 3418.85
#Mann= 7 ,-1,0
       0     .07       0      50     .06       0     120     .08       0
209.8005    .045       0  228.22     .08       0     250      .1       0
     380     .12       0
Bank Sta=209.8005,228.22
XS Rating Curve= 0 ,0
Exp/Cntr=0.3,0.1

Type RM Length L Ch R = 1 ,190115  ,256.4,256.4,256.4
XS GIS Cut Line= 2
 2337897.5977543 619366.272758162338096.88703711619756.834195109
#Sta/Elev= 30
       0  3427.6     5.7 3426.42    16.7 3422.68    30.2  3420.1    39.2 3416.65
    52.7 3414.09    75.1 3412.32    84.1 3412.26    93.1 3410.24   108.1 3409.64
   131.9 3404.47   142.5 3403.14   151.5 3403.76   173.6 3403.23   191.9 3403.57
  195.58 3402.67   200.9 3401.42   211.7 3401.33   214.3 3401.33   218.2 3402.67
   223.3 3404.26   234.5 3403.66   250.2 3404.32   259.2 3405.78   277.2 3406.62
   317.6 3409.92     349 3411.46   405.5 3423.67   428.1 3427.65   438.5 3428.68
#Mann= 7 ,-1,0
       0      .1       0      50     .06       0     160     .08       0
  195.58    .045       0   218.2     .08       0     270      .1       0
     380     .12       0
Bank Sta=195.58,218.2
XS Rating Curve= 0 ,0
Exp/Cntr(USF)=0,0
Exp/Cntr=0.3,0.1

Type RM Length L Ch R = 1 ,189859  ,225.1,225.1,225.1
XS GIS Cut Line= 3
 2337766.9301685619371.1608192482337753.24251173619561.004460105
2337724.26522922619885.408288066
#Sta/Elev= 30
       0 3434.93    14.1 3432.23    25.1 3427.61    38.1 3423.47    46.1 3419.79
    54.2 3418.78    74.2 3412.56    82.2 3411.85    90.3 3408.64   102.3 3407.11
   116.7 3406.52   126.3 3404.65   170.5    3403   190.5 3403.58   198.5 3402.22
   211.4  3402.4   230.7 3401.52   238.7  3402.5   258.8 3403.01   270.8 3405.77
     303 3407.82   363.2 3410.09   379.5 3409.53   403.4 3411.26   423.4 3415.21
   464.3 3419.17   475.6 3422.04   483.7 3422.73   491.7 3425.42     516 3430.16
#Mann= 6 ,-1,0
       0      .1       0      40     .06       0     140     .08       0
   211.4    .045       0   238.7      .1       0  330.34     .12       0
Bank Sta=211.4,238.7
XS Rating Curve= 0 ,0
Exp/Cntr=0.3,0.1

Type RM Length L Ch R = 1 ,189634  ,250.6,250.6,250.6
XS GIS Cut Line= 2
2337603.16064758619365.4779396892337485.68170498619758.298154007
#Sta/Elev= 30
       0 3429.45    12.2 3426.89    24.7 3423.61    33.1 3420.17    37.3 3419.49
    74.8 3406.72    91.5 3404.93    99.9 3404.59   112.4 3402.98   124.3 3403.53
   141.6 3402.72   145.8 3401.92     150 3401.97   154.2 3401.36   166.7  3400.7
   175.7    3402   182.1 3402.44   204.3 3402.26   217.5 3403.72     246 3404.48
   266.9 3405.58   275.2 3406.48   291.9 3407.17   325.3 3406.21   354.6 3407.51
     391 3407.44   396.3 3408.84   400.5 3411.53   404.7 3413.05     410 3413.29
#Mann= 6 ,-1,0
       0      .1       0      40     .06       0     150    .045       0
   175.7     .06       0     200     .08       0     250     .12       0
Bank Sta=150,175.7
XS Rating Curve= 0 ,0
Exp/Cntr(USF)=0,0
Exp/Cntr=0.3,0.1

Type RM Length L Ch R = 1 ,189383  ,261.7,261.7,261.7
XS GIS Cut Line= 3
2337519.76544176619171.9654300972337370.53044365619400.649450701
2337108.71597311619728.290858415
#Sta/Elev= 30
       0 3463.66     6.2  3460.8    30.1  3453.4    43.9 3447.61      97 3432.76
   111.3 3427.66   124.9 3424.84   171.1 3408.89   182.7 3408.03   191.3 3405.68
   214.5 3403.04   246.3 3402.64   263.6 3400.31   278.9 3400.13   289.7  3401.4
   309.3 3400.49   319.8 3399.72   326.4 3400.41   334.5 3401.82     371 3401.33
   447.8 3403.06   514.2 3409.06   551.2 3424.49   570.7 3435.07   584.4 3437.89
   597.2 3442.84   647.5 3456.95   652.6 3457.13     668 3461.11   692.5 3465.55
#Mann= 9 ,-1,0
       0      .1       0     130     .06       0  283.07     .08       0
   309.3    .045       0   326.4      .1       0  403.07     .12       0
  463.07      .1       0  623.07     .12       0  663.07      .1       0
#XS Ineff= 1 ,-1
  413.42  536.74 3416.56
Permanent Ineff=
       F
Bank Sta=309.3,326.4
XS Rating Curve= 0 ,0
Exp/Cntr=0.3,0.1

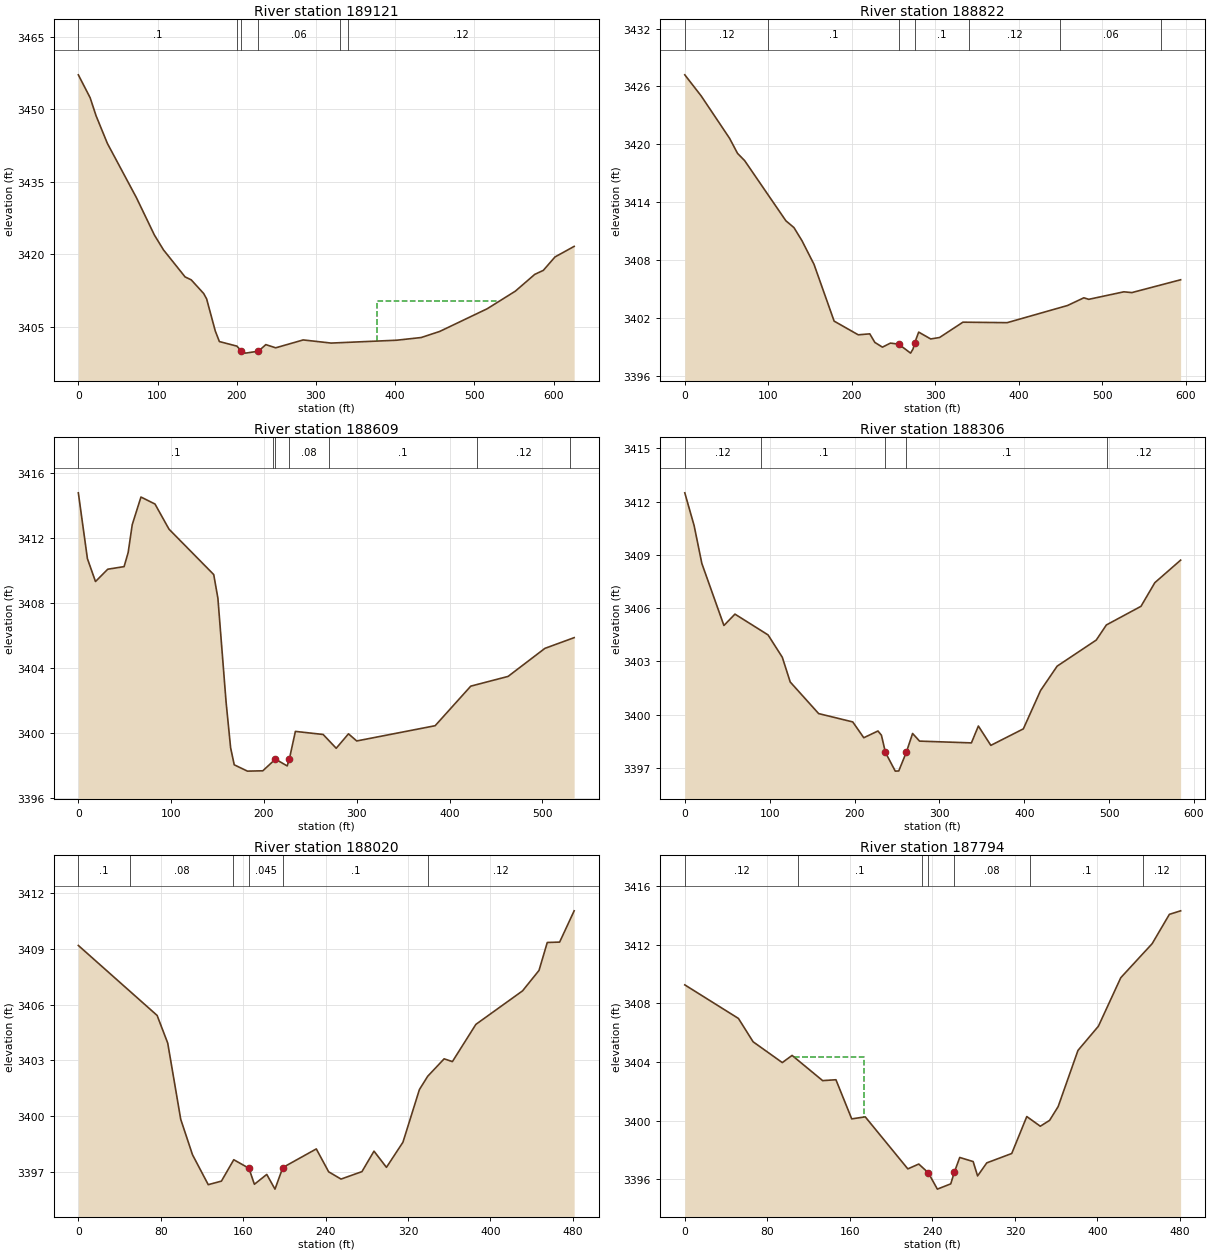
Type RM Length L Ch R = 1 ,189121  ,299.7,299.7,299.7
XS GIS Cut Line= 2
2337384.98859041 619066.279551912336959.75153037619525.713997899
#Sta/Elev= 30
       0 3457.08    14.9 3452.34    22.4 3448.61    36.7 3442.88    73.4 3431.64
      96 3423.94   107.5 3420.86   134.8 3415.26   142.5 3414.66   158.3 3411.82
     162  3410.7   172.9 3404.08   178.1 3401.88   200.2 3400.94   205.6 3399.96
   211.1 3399.49   227.4 3399.89   236.7 3401.25   249.2 3400.59   283.9 3402.22
   319.2 3401.57   401.8 3402.16   432.9 3402.72   456.3 3403.98   516.3 3408.68
   551.8 3412.32   576.2 3415.78   587.1 3416.62   601.8 3419.39     626 3421.58
#Mann= 6 ,-1,0
       0      .1       0     200     .06       0   205.6    .045       0
   227.4     .06       0     330      .1       0     340     .12       0
#XS Ineff= 1 ,-1
  377.01  527.35 3410.21
Permanent Ineff=
       F
Bank Sta=205.6,227.4
XS Rating Curve= 0 ,0
Exp/Cntr(USF)=0,0
Exp/Cntr=0.3,0.1

Type RM Length L Ch R = 1 ,188822  ,212.5,212.5,212.5
XS GIS Cut Line= 2
2337171.23534408618832.7114265372336839.74368638619325.600198932
#Sta/Elev= 30
       0 3427.21    19.8    3425    53.6 3420.63    63.2 3419.06    71.7 3418.31
   121.1 3412.07   130.7 3411.37   140.4    3410   154.8 3407.55   178.9 3401.66
   207.8 3400.24   221.6 3400.34   227.7 3399.45   236.8 3398.96   246.4 3399.38
   256.2 3399.27   270.5 3398.34   273.5 3398.78   275.3 3399.38   280.2 3400.52
   294.6 3399.81   305.2 3399.96   333.2 3401.55   386.2  3401.5   458.5 3403.28
   478.1 3404.08   483.9 3403.92     526  3404.7   535.6 3404.62     594 3405.95
#Mann= 7 ,-1,0
       0     .12       0     100      .1       0   256.2    .045       0
   275.3      .1       0     340     .12       0     450     .06       0
     570     .12       0
Bank Sta=256.2,275.3
XS Rating Curve= 0 ,0
Exp/Cntr=0.3,0.1

Type RM Length L Ch R = 1 ,188609  ,303.3,303.3,303.3
XS GIS Cut Line= 2
2336968.67258757618724.3056924362336747.13300035619210.503310036
#Sta/Elev= 30
       0  3414.8     9.8 3410.74    18.5 3409.33    31.7 3410.09    49.3 3410.25
    53.7 3411.12    58.1 3412.84    67.5 3414.54    82.6 3414.11    97.7 3412.56
   145.9 3409.76   150.4  3408.3   159.2 3401.91   164.1 3399.08     168 3398.03
   182.2 3397.64   198.8 3397.66   212.4 3398.38   225.1 3397.96   227.5 3398.41
   233.9 3400.09   263.8  3399.9   277.9 3399.05   291.1 3399.94     300  3399.5
   384.5 3400.44   422.9 3402.88   463.1 3403.48   502.8 3405.21   534.3 3405.87
#Mann= 7 ,-1,0
       0      .1       0     210     .08       0   212.4    .045       0
   227.5     .08       0     270      .1       0     430     .12       0
     530     .06       0
Bank Sta=212.4,227.5
XS Rating Curve= 0 ,0
Exp/Cntr(USF)=0,0
Exp/Cntr=0.3,0.1

Type RM Length L Ch R = 1 ,188306  ,285.5,285.5,285.5
XS GIS Cut Line= 3
2336760.01911949618638.6788841152336675.73609703618839.710608262
2336604.95679719619199.003722066
#Sta/Elev= 30
       0 3412.49      11 3410.64    20.1 3408.51    46.1 3405.02    59.1 3405.66
    98.1 3404.49   114.9 3403.23   124.2 3401.84   157.7 3400.06   197.9 3399.59
   210.9  3398.7   227.6 3399.08   231.7 3398.84   236.4 3397.87     248 3396.82
   252.1 3396.83     261 3397.88   268.4 3398.94   276.6 3398.51   337.7 3398.41
   345.9 3399.36   360.6 3398.27   398.9  3399.2   419.2 3401.36   438.7 3402.73
   484.8  3404.2   496.7 3405.05   537.5  3406.1   553.8 3407.43   584.2  3408.7
#Mann= 5 ,-1,0
       0     .12       0      90      .1       0   236.4    .045       0
     261      .1       0  497.98     .12       0
Bank Sta=236.4,261
XS Rating Curve= 0 ,0
Exp/Cntr=0.3,0.1

Type RM Length L Ch R = 1 ,188020  ,226.4,226.4,226.4
XS GIS Cut Line= 3
2336474.56573887618670.4970096722336488.16238262618939.856825954
2336497.69440569619151.242870092
#Sta/Elev= 30
       0 3409.18    76.5 3405.42    86.8 3403.93    99.4 3399.84   110.8 3397.94
   126.1 3396.33   138.9 3396.52   150.9 3397.67   165.6 3397.21   170.9 3396.35
   182.9 3396.88   190.9 3396.09   198.5 3397.25     231 3398.25     243 3397.02
     255 3396.63   275.3 3397.03     287 3398.13   299.1 3397.26   315.1 3398.61
   331.1 3401.44   339.1 3402.15   355.1 3403.09   363.1 3402.94   385.9 3404.94
   431.2 3406.74   447.2 3407.84   455.2 3409.34   467.2 3409.36   481.3 3411.04
#Mann= 6 ,-1,0
       0      .1       0      50     .08       0     150      .1       0
   165.6    .045       0   198.5      .1       0   339.7     .12       0
Bank Sta=165.6,198.5
XS Rating Curve= 0 ,0
Exp/Cntr(USF)=0,0
Exp/Cntr=0.3,0.1

Type RM Length L Ch R = 1 ,187794  ,227.1,227.1,227.1
XS GIS Cut Line= 3
2336237.04743047 618721.153432092336361.85275142618919.595282739
2336456.90868412619146.658202918
#Sta/Elev= 30
       0 3409.27      52 3406.98    66.2 3405.39    94.5 3403.97     104 3404.46
   133.6 3402.74   146.5  3402.8   161.8 3400.13   174.9 3400.27   216.2 3396.72
   226.8 3397.05   236.1 3396.45   244.8 3395.34   257.8  3395.7   261.2 3396.48
   266.5  3397.5   279.5 3397.22   283.8 3396.24   292.7 3397.13   316.9 3397.77
   331.5 3400.29   344.6 3399.63   353.6 3400.03   361.9 3400.97   381.1  3404.8
   400.9 3406.45   422.6 3409.76     453 3412.08   469.7 3414.08   480.6 3414.32
#Mann= 7 ,-1,0
       0     .12       0     110      .1       0     230     .08       0
   236.1    .045       0   261.2     .08       0  334.43      .1       0
  444.43     .12       0
#XS Ineff= 1 ,-1
   105.7  173.66 3404.32
Permanent Ineff=
       F
Bank Sta=236.1,261.2
XS Rating Curve= 0 ,0
Exp/Cntr=0.3,0.1