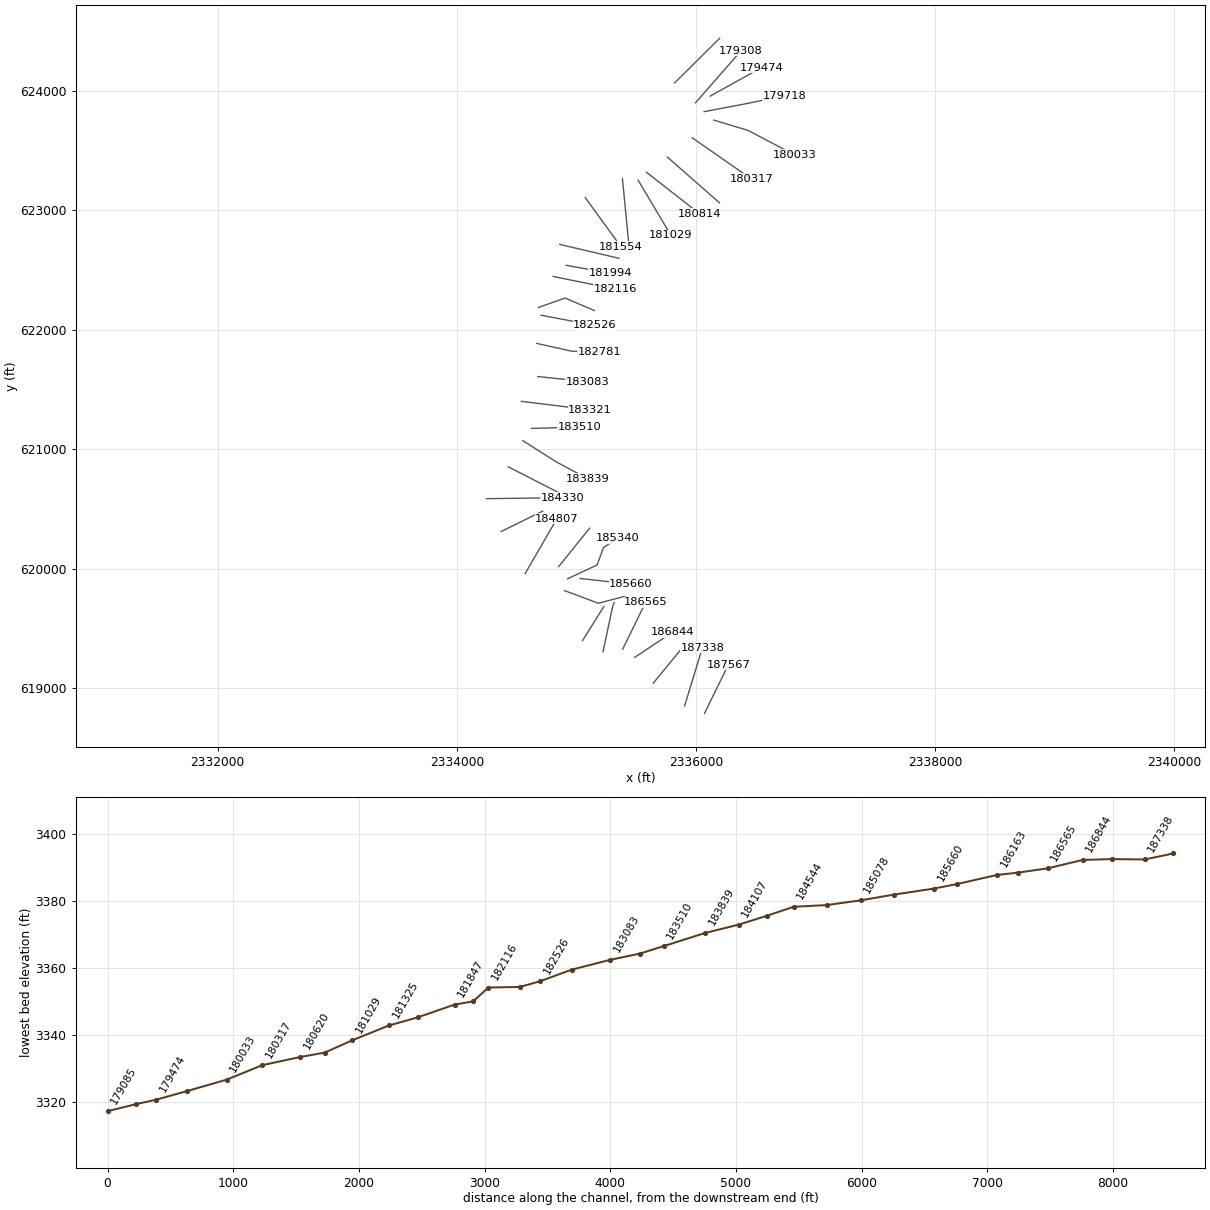
HEC-RAS study LAURELFK.prj: LAURELFK

--- LAURELFK.g01 (geometry) --- (continued)

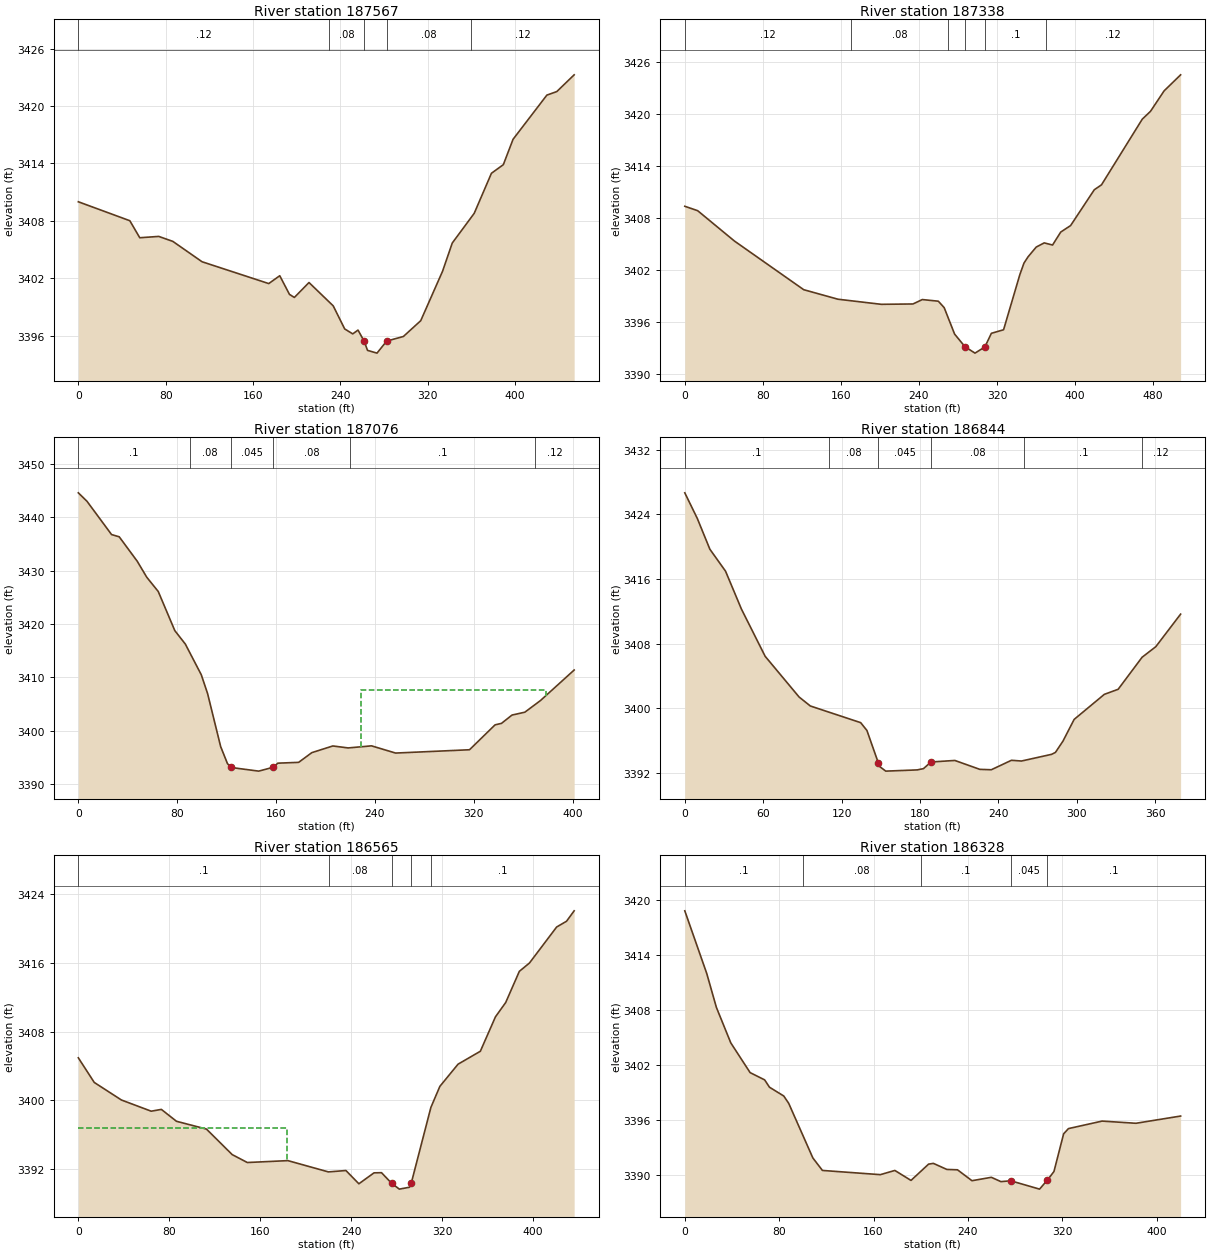
Type RM Length L Ch R = 1 ,187567  ,228.4,228.4,228.4
XS GIS Cut Line= 2
2336071.42245147618791.3683099082336271.32021474619199.424074594
#Sta/Elev= 30
       0 3409.99    47.2 3408.01    56.3 3406.23    73.7 3406.37    86.6 3405.85
   113.4 3403.72   174.5 3401.44   184.6 3402.26   193.5 3400.31     198 3399.99
   211.4 3401.55   233.6 3399.11   244.1  3396.7   251.5 3396.18   256.3 3396.58
     262 3395.41     265 3394.46   273.7 3394.17   282.6 3395.43   297.9 3395.91
   313.8 3397.56   333.8 3402.73   342.7 3405.68   362.8 3408.78   378.6 3412.97
   389.5 3413.87   398.4 3416.52   429.4 3421.14   438.5 3421.51   454.4 3423.26
#Mann= 5 ,-1,0
       0     .12       0     230     .08       0     262    .045       0
   282.6     .08       0     360     .12       0
Bank Sta=262,282.6
XS Rating Curve= 0 ,0
Exp/Cntr(USF)=0,0
Exp/Cntr=0.3,0.1

Type RM Length L Ch R = 1 ,187338  ,262.9,262.9,262.9
XS GIS Cut Line= 2
2335904.79885735618852.5848582912336053.09790427619338.767093606
#Sta/Elev= 30
       0 3409.33    13.2 3408.82    50.8 3405.32   121.9 3399.69     157 3398.59
   201.4    3398   233.9 3398.04   243.5 3398.55   259.9 3398.36   265.9 3397.62
   276.6 3394.56   287.33393.093   297.5 3392.36   307.6 3393.07   314.3 3394.65
   326.8 3395.06   343.5 3401.44   347.7 3402.76   351.9 3403.49   360.3 3404.62
   368.5  3405.1     377 3404.85   385.4 3406.35   395.5  3407.1   419.8 3411.24
   427.2 3411.81     469  3419.4   477.4  3420.3   491.4 3422.67   508.3 3424.52
#Mann= 6 ,-1,0
       0     .12       0     170     .08       0     270      .1       0
   287.3    .045       0   307.6      .1       0     370     .12       0
Bank Sta=287.3,307.6
XS Rating Curve= 0 ,0
Exp/Cntr=0.3,0.1

Type RM Length L Ch R = 1 ,187076  ,231.6,231.6,231.6
XS GIS Cut Line= 2
2335643.20640283619044.2372694732335897.45653313 619354.69006016
#Sta/Elev= 30
       0 3444.55       7 3442.97    26.9 3436.74    33.1 3436.32    47.7 3431.74
    55.4 3428.75    64.7 3426.08    78.1 3418.76    86.6 3416.25    99.5 3410.51
   104.6    3407   115.2 3397.06   120.7 3393.88   123.6 3393.15     146 3392.47
   157.7 3393.19   161.5 3393.96   178.3 3394.11     189 3395.93     206 3397.18
   218.4 3396.81   237.3  3397.2   256.8 3395.85   316.6 3396.47   337.3 3401.13
   342.5 3401.41     351 3402.96   361.4  3403.5     374 3405.67   401.3 3411.39
#Mann= 6 ,-1,0
       0      .1       0      90     .08       0   123.6    .045       0
   157.7     .08       0     220      .1       0     370     .12       0
#XS Ineff= 1 ,-1
  229.03  378.36 3407.69
Permanent Ineff=
       F
Bank Sta=123.6,157.7
XS Rating Curve= 0 ,0
Exp/Cntr(USF)=0,0
Exp/Cntr=0.3,0.1

Type RM Length L Ch R = 1 ,186844  ,278.5,278.5,278.5
XS GIS Cut Line= 2
2335488.15897498619259.8768851992335803.99319694619470.323683252
#Sta/Elev= 30
       0 3426.66     9.6 3423.48    19.2 3419.68    31.2 3416.96    43.3 3412.29
    61.5 3406.43    87.5 3401.39    96.1 3400.28   134.6 3398.22   139.4 3397.25
   148.1 3393.25     149 3392.81   153.8 3392.22   177.9 3392.37   182.7 3392.53
   188.4 3393.35   206.7 3393.54   225.8 3392.44   234.6 3392.39     250 3393.56
   257.7 3393.47   280.8  3394.3   283.7 3394.54   289.4 3395.92     298 3398.62
   321.1 3401.72   331.7 3402.35     350 3406.31   360.5 3407.62   379.5 3411.65
#Mann= 6 ,-1,0
       0      .1       0     110     .08       0   148.1    .045       0
   188.4     .08       0     260      .1       0     350     .12       0
Bank Sta=148.1,188.4
XS Rating Curve= 0 ,0
Exp/Cntr=0.3,0.1

Type RM Length L Ch R = 1 ,186565  ,237.9,237.9,237.9
XS GIS Cut Line= 2
2335386.95015641619327.6466523222335578.66926413619719.243127655
#Sta/Elev= 30
       0 3404.95      14 3402.09    37.9 3400.05    64.1 3398.75      73 3398.96
    86.3 3397.58   112.7 3396.67   135.3 3393.71   148.6 3392.79   184.3 3393.01
   219.9  3391.7   235.3 3391.86   246.7 3390.32     260 3391.59   266.6 3391.61
   275.63390.361   282.3  3389.7   291.2 3389.92   292.83390.417     310 3399.18
   317.9 3401.63   333.9 3404.21   353.5 3405.71   366.8 3409.71   375.8 3411.37
   387.8 3414.99   396.7 3415.96   420.6 3420.14   429.3 3420.81     436 3422.02
#Mann= 5 ,-1,0
       0      .1       0     220     .08       0   275.6    .045       0
   292.8     .08       0     310      .1       0
#XS Ineff= 2 , 0
          183.44 3396.81
Permanent Ineff=
       F       F
Bank Sta=275.6,292.8
XS Rating Curve= 0 ,0
Exp/Cntr(USF)=0,0
Exp/Cntr=0.3,0.1

Type RM Length L Ch R = 1 ,186328  ,164.4,164.4,164.4
XS GIS Cut Line= 3
2335222.86781646619306.9856359022335303.66925935 619687.27524934
2335316.40788175619716.227155032
#Sta/Elev= 30
       0 3418.81    18.6 3411.97    26.8 3408.26      39 3404.39    55.4 3401.14
    67.7 3400.35    71.8 3399.55    83.9 3398.59    88.1 3397.79   108.6 3391.82
   116.7 3390.46   165.8    3390   178.1 3390.46   191.8 3389.37   206.7 3391.15
   210.8 3391.23   222.2 3390.57   231.2 3390.53   243.5 3389.34   259.9 3389.71
     268 3389.24   276.4 3389.33   300.8 3388.42   307.5 3389.42     313 3390.34
   321.2 3394.46   325.3 3395.03   353.9 3395.85   382.5 3395.61   420.4  3396.4
#Mann= 5 ,-1,0
       0      .1       0     100     .08       0     200      .1       0
   276.4    .045       0   307.5      .1       0
Bank Sta=276.4,307.5
XS Rating Curve= 0 ,0
Exp/Cntr=0.3,0.1

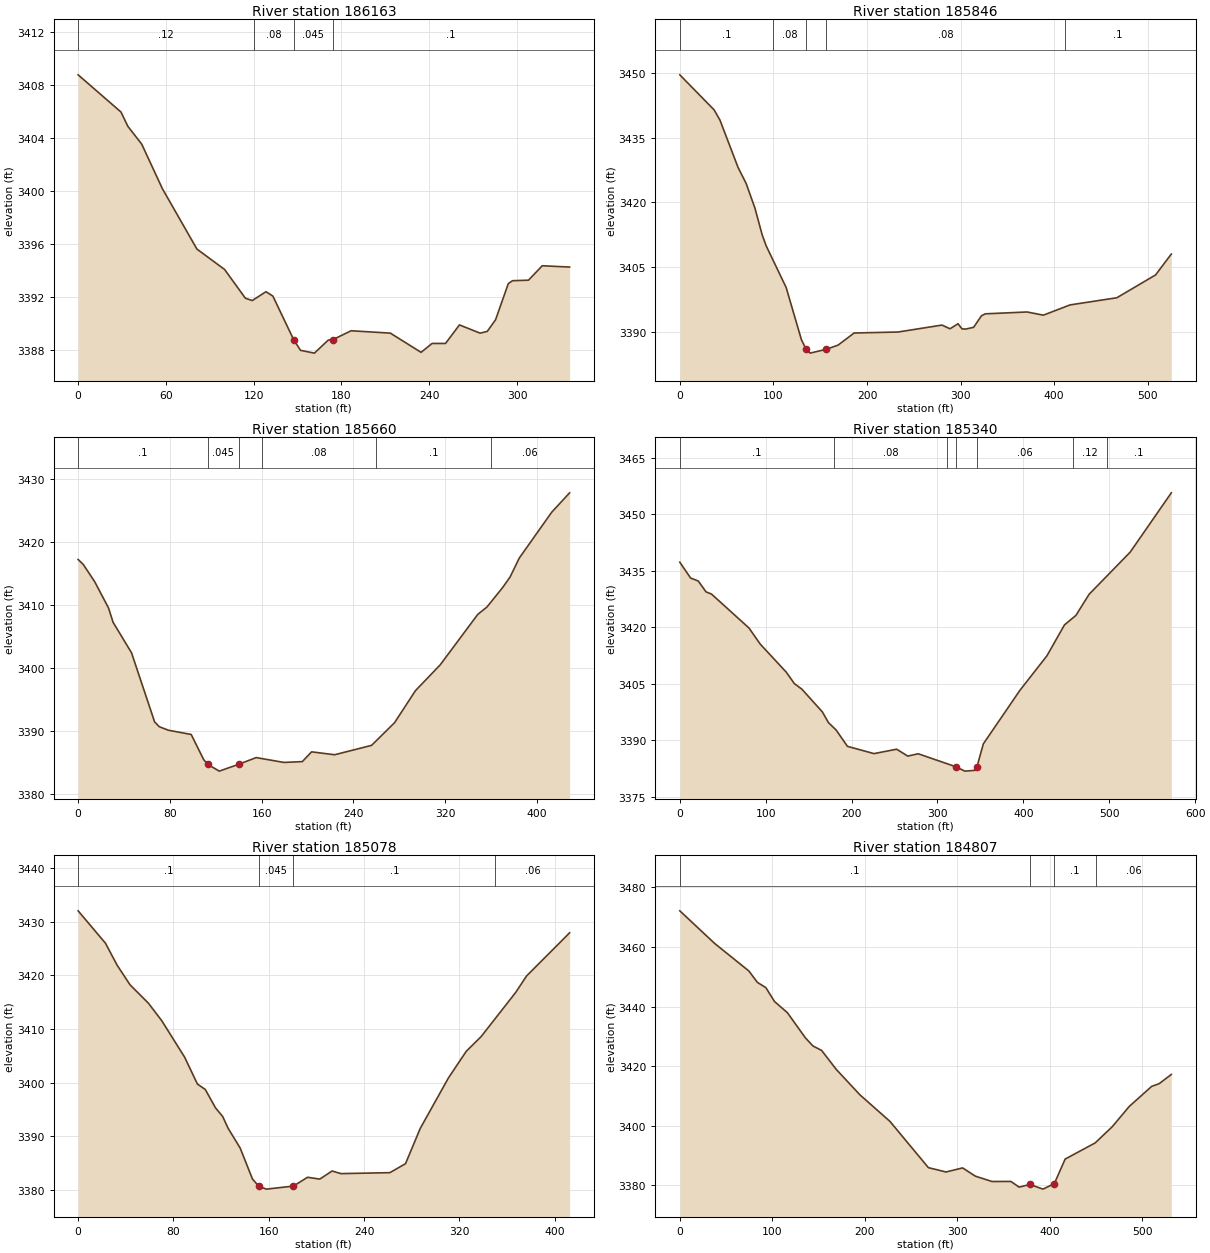
Type RM Length L Ch R = 1 ,186163  ,316.8,316.8,316.8
XS GIS Cut Line= 2
2335051.75135645619400.3536732972335230.05879055619684.962510262
#Sta/Elev= 30
       0 3408.76    29.3 3405.95      34 3404.87    43.5 3403.52    57.6 3400.16
    81.2  3395.6   100.1 3394.06   114.3 3391.89     119 3391.71   128.4 3392.38
   133.1 3392.05   147.3 3388.76     152 3387.95   161.5 3387.74   170.9 3388.72
   174.1 3388.76   186.6 3389.43   213.4 3389.25   234.4  3387.8   241.9 3388.47
   251.1 3388.47   260.6 3389.87   274.7 3389.25   279.6 3389.38   285.3 3390.26
     294 3392.99   296.9 3393.21   307.8 3393.25   317.2 3394.34   335.9 3394.24
#Mann= 4 ,-1,0
       0     .12       0     120     .08       0   147.3    .045       0
   174.1      .1       0
Bank Sta=147.3,174.1
XS Rating Curve= 0 ,0
Exp/Cntr(USF)=0,0
Exp/Cntr=0.3,0.1

Type RM Length L Ch R = 1 ,185846  ,186,186,186
XS GIS Cut Line= 3
2334901.80618193619817.975688256 2335184.1854189619712.268920222
2335400.42499263619769.047897845
#Sta/Elev= 30
       0 3449.62    36.7 3441.47    42.9 3439.11    62.3 3428.09    70.9 3424.39
    80.2 3418.73      88 3412.48    92.2 3409.96   113.6 3400.27   129.9 3388.16
   134.9 3385.94   139.2 3385.03   156.3 3385.91   169.1 3386.89   186.2  3389.7
   233.2 3389.93   280.1 3391.54   288.7 3390.68   297.2 3391.85   301.5 3390.65
   305.6 3390.62   313.9 3391.02   322.2 3393.68   326.3 3394.15     371 3394.58
   388.4 3393.84   416.9 3396.22   466.9 3397.88   508.3 3403.18   525.1 3408.03
#Mann= 5 ,-1,0
       0      .1       0     100     .08       0   134.9    .045       0
   156.3     .08       0  411.52      .1       0
Bank Sta=134.9,156.3
XS Rating Curve= 0 ,0
Exp/Cntr=0.3,0.1

Type RM Length L Ch R = 1 ,185660  ,320.3,320.3,320.3
XS GIS Cut Line= 2
 2335029.8629161619919.8198837222335455.83893705619872.127911911
#Sta/Elev= 30
       0 3417.26     4.5 3416.47    14.4 3413.75    26.5 3409.57    30.5 3407.29
    46.6 3402.44    66.7 3391.48    70.8 3390.71    78.8 3390.15    98.6 3389.48
   109.5 3385.49     1133384.742   123.1 3383.66   140.1 3384.75   155.3 3385.81
   179.4 3385.04   195.5 3385.17   203.6 3386.72   223.7 3386.26   255.9 3387.75
     276 3391.36   294.2 3396.44   315.8 3400.54   348.5 3408.54   356.5 3409.71
   370.1 3412.78   376.7 3414.48   384.7 3417.48   412.9 3424.74   428.6 3427.84
#Mann= 6 ,-1,0
       0      .1       0     113    .045       0   140.1      .1       0
     160     .08       0     260      .1       0     360     .06       0
Bank Sta=113,140.1
XS Rating Curve= 0 ,0
Exp/Cntr(USF)=0,0
Exp/Cntr=0.3,0.1

Type RM Length L Ch R = 1 ,185340  ,262.2,262.2,262.2
XS GIS Cut Line= 4
2334927.20859578619917.6015990272335172.95471947620031.968337106
2335227.09691619620178.7109803582335348.26666005620258.065445577
#Sta/Elev= 30
       0 3437.32    12.5 3433.13    21.5 3432.32    30.5 3429.45    36.9 3428.86
    80.5 3419.86    93.7 3415.56   123.9 3408.14   133.4 3405.08   142.2  3403.6
     166 3397.57   173.1 3394.72     182 3392.77   195.2 3388.43   226.1  3386.5
   252.5 3387.67   265.4 3385.84   277.6 3386.46   321.2 3383.03     332 3381.85
   344.8 3382.08   346.1 3383.07   353.4 3389.08     396  3403.3   427.5 3412.48
   447.9 3420.68   461.2 3423.19   476.6 3428.81   524.4 3439.99   572.3 3455.74
#Mann= 7 ,-1,0
       0      .1       0     180     .08       0  311.06      .1       0
   321.2    .045       0   346.1     .06       0  457.47     .12       0
  497.47      .1       0
Bank Sta=321.2,346.1
XS Rating Curve= 0 ,0
Exp/Cntr=0.3,0.1

Type RM Length L Ch R = 1 ,185078  ,271.2,271.2,271.2
XS GIS Cut Line= 2
2334852.09152236  620019.23614522335110.80218127620340.394204532
#Sta/Elev= 30
       0 3432.03      23 3425.98    32.7 3421.91    43.6 3418.23      59 3414.81
    70.3 3411.51    89.4 3404.74   100.1 3399.74   106.7 3398.73   115.2 3395.33
   121.3 3393.69   125.8 3391.52     136  3387.8   146.3 3382.04   151.5 3380.71
   157.9 3380.15   180.7 3380.72   192.5 3382.36   202.8 3382.02   213.1 3383.53
   220.5 3383.04   261.6 3383.22   274.7 3384.89   287.1 3391.48   310.7 3400.87
   325.7 3405.85   338.1 3408.57   367.2 3416.83   376.3 3419.89   412.4 3427.93
#Mann= 4 ,-1,0
       0      .1       0   151.5    .045       0   180.7      .1       0
     350     .06       0
Bank Sta=151.5,180.7
XS Rating Curve= 0 ,0
Exp/Cntr(USF)=0,0
Exp/Cntr=0.3,0.1

Type RM Length L Ch R = 1 ,184807  ,262.3,262.3,262.3
XS GIS Cut Line= 2
2334571.39304911619960.5712995142334837.76911621620420.538898541
#Sta/Elev= 30
       0 3472.11    37.7 3461.16    74.7 3451.92    83.9  3448.1    93.1 3446.33
   102.4 3441.68   116.3 3437.95   135.7 3429.54     144 3426.76   153.3 3425.29
   169.2  3418.9   194.8 3410.37   227.2 3401.48   268.8 3385.95   287.9 3384.49
   305.8 3385.86   319.6 3383.09   337.6  3381.3   358.1 3381.31   366.9 3379.41
   378.6  3380.3   392.7 3378.74     405 3380.59   416.7 3388.82   449.1 3394.23
   467.6 3399.67     486 3406.48   510.3 3413.22   518.4 3414.13   531.5 3417.21
#Mann= 4 ,-1,0
       0      .1       0   378.6    .045       0     405      .1       0
     450     .06       0
Bank Sta=378.6,405
XS Rating Curve= 0 ,0
Exp/Cntr=0.3,0.1

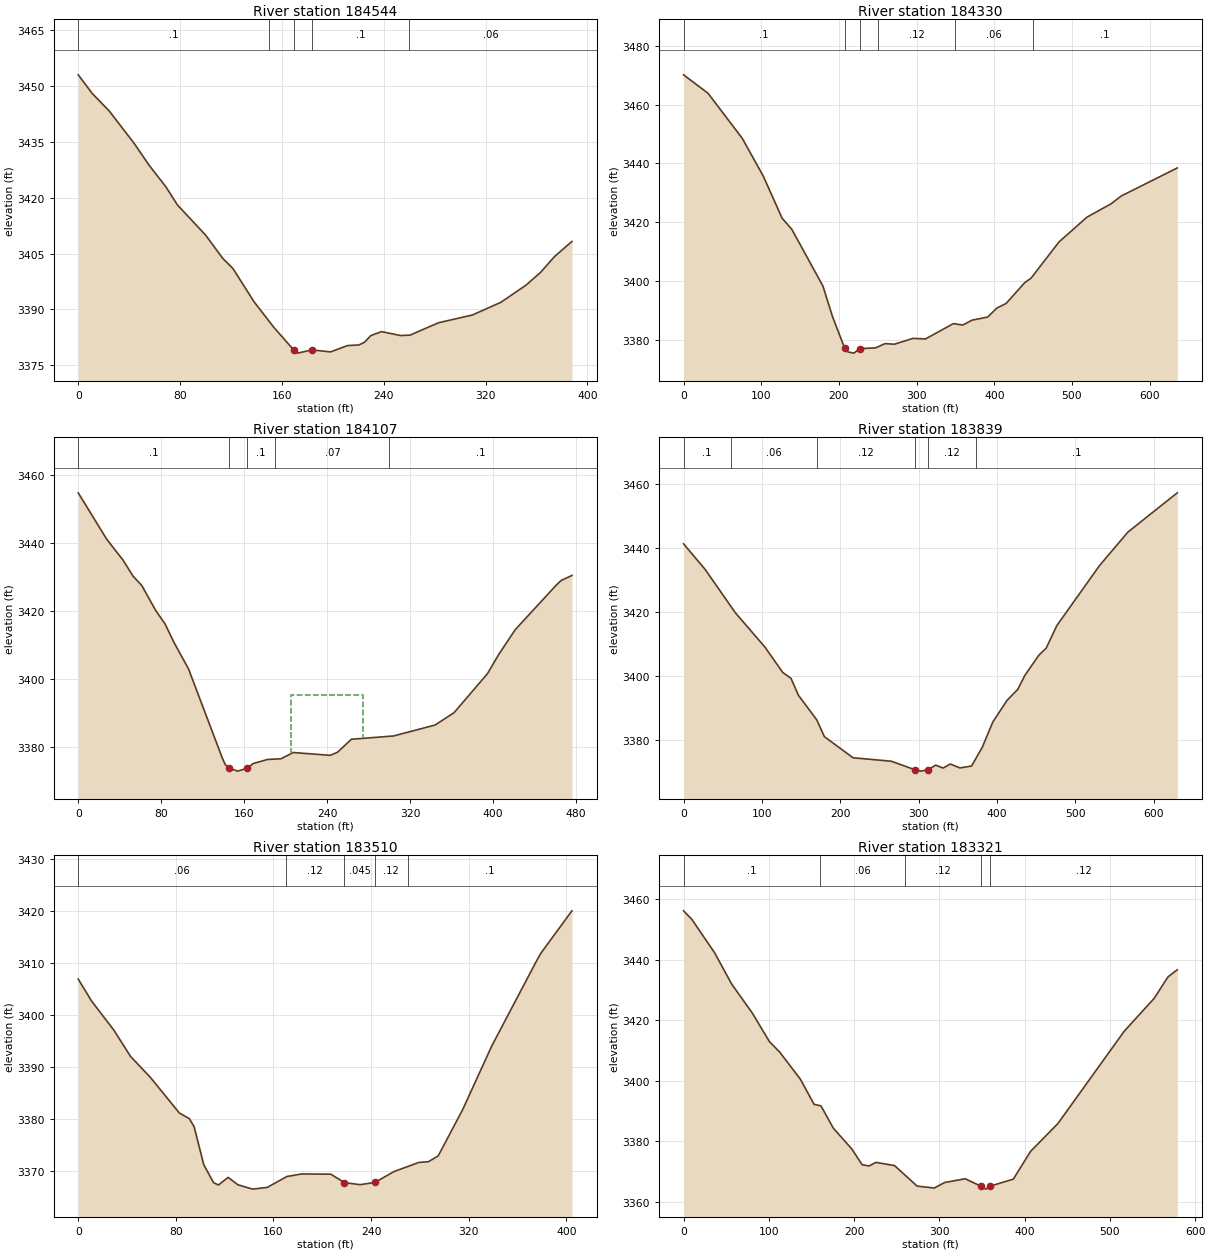
Type RM Length L Ch R = 1 ,184544  ,214.6,214.6,214.6
XS GIS Cut Line= 2
2334370.30684805620312.2370831742334718.36189485620483.253749768
#Sta/Elev= 30
       0 3453.03      11 3448.03    24.4 3443.29    43.9 3434.62    55.9 3428.63
    68.9 3422.92    77.8 3418.11   100.1 3409.93   113.5 3403.71   121.6 3400.93
   138.2 3391.99   153.6 3385.18   169.5 3378.99   172.4 3378.23   183.5  3379.1
   198.2 3378.56   211.5 3380.26   220.5 3380.43   224.9 3381.16   229.8 3382.95
   238.3 3384.01   253.1 3382.96   260.6 3383.06   282.9 3386.38   309.6 3388.48
   331.9 3391.87   351.7 3396.49   363.1 3399.91     374 3404.14   387.8 3408.25
#Mann= 5 ,-1,0
       0      .1       0     150     .12       0   169.5    .045       0
   183.5      .1       0     260     .06       0
Bank Sta=169.5,183.5
XS Rating Curve= 0 ,0
Exp/Cntr(USF)=0,0
Exp/Cntr=0.3,0.1

Type RM Length L Ch R = 1 ,184330  ,222.3,222.3,222.3
XS GIS Cut Line= 2
2334248.79918371620587.0447571682334884.30838264620595.228827961
#Sta/Elev= 30
       0  3470.1    31.4 3463.87    75.4 3448.59   102.6  3435.7   126.9 3421.38
   139.4 3417.59   179.4 3398.34   191.7    3388   207.4 3377.21   211.4 3375.94
   219.4 3375.52   226.6 3377.04   247.4 3377.32   259.4 3378.76   271.4 3378.54
   295.4 3380.54   311.4 3380.33   347.4 3385.55   359.4 3385.06   371.4 3386.72
   391.4 3387.76   403.4 3390.83   415.4 3392.44   439.4 3399.52   447.4    3401
   483.4 3413.32   519.4 3421.74   550.5 3426.28   563.4 3428.91   635.6 3438.45
#Mann= 6 ,-1,0
       0      .1       0   207.4    .045       0   226.6      .1       0
     250     .12       0     350     .06       0     450      .1       0
Bank Sta=207.4,226.6
XS Rating Curve= 0 ,0
Exp/Cntr=0.3,0.1

Type RM Length L Ch R = 1 ,184107  ,268.5,268.5,268.5
XS GIS Cut Line= 2
2334429.62877627620853.6572196542334853.43698032620636.875529605
#Sta/Elev= 30
       0 3454.69    27.4 3441.08    43.3 3434.88    52.8 3430.23    61.3 3427.45
    74.7 3420.12    83.7 3416.17    92.7 3410.51   106.3 3402.97     139 3376.68
   141.6  3374.9   144.9 3373.87   153.8  3372.9   162.8 3373.75   168.7 3375.13
   182.6 3376.33   195.5 3376.53   207.3 3378.37     243 3377.54     250 3378.45
   263.4 3382.27   303.9 3383.23   344.1 3386.45   362.3 3390.06   394.6 3401.56
   405.1 3407.03   421.4  3414.5   461.1 3427.63   465.6 3428.93     476 3430.41
#Mann= 5 ,-1,0
       0      .1       0   144.9    .045       0   162.8      .1       0
     190     .07       0     300      .1       0
#XS Ineff= 1 ,-1
   204.7  274.33 3395.26
Permanent Ineff=
       F
Bank Sta=144.9,162.8
XS Rating Curve= 0 ,0
Exp/Cntr(USF)=0,0
Exp/Cntr=0.3,0.1

Type RM Length L Ch R = 1 ,183839  ,328.7,328.7,328.7
XS GIS Cut Line= 3
2334552.32437275621072.0023844172334833.51681451620893.683699822
2335095.75605557620753.516242832
#Sta/Elev= 30
       0 3441.39    27.7 3433.36    66.1 3419.87     104 3409.12   126.6 3401.22
   137.2 3399.37   146.7 3394.07     170 3386.44   179.8 3381.17   216.4 3374.57
   265.1  3373.5   295.13370.861     303  3370.4   312.4 3370.85   321.9 3372.27
   331.4 3371.36   340.5 3372.62     353  3371.4   367.7    3372   381.3 3377.81
   394.9 3385.78   413.1 3392.54   426.7 3395.95   435.8 3400.32   453.5 3406.57
     463 3408.83   476.6 3415.87     531 3434.58   567.3 3445.06   630.3 3457.32
#Mann= 6 ,-1,0
       0      .1       0      60     .06       0     170     .12       0
   295.1    .045       0   312.4     .12       0  372.97      .1       0
Bank Sta=295.1,312.4
XS Rating Curve= 0 ,0
Exp/Cntr=0.3,0.1

Type RM Length L Ch R = 1 ,183510  ,189.1,189.1,189.1
XS GIS Cut Line= 2
2334625.26904759621174.7691868582335029.69030749621185.177086929
#Sta/Elev= 30
       0 3406.92    10.9 3402.71    29.3 3397.06    42.9 3392.02    58.9 3388.06
    82.9 3381.13      91 3380.06      95 3378.48   102.9 3371.18   110.9 3367.72
   114.9 3367.28   122.9 3368.74   130.9 3367.31     143 3366.48     155 3366.82
     171 3368.91     183  3369.4     207 3369.36   218.2 3367.73     231 3367.34
   243.1 3367.77   258.7 3369.85     279 3371.61     287 3371.76     295 3372.88
     315 3381.76     339 3394.09     375 3410.15     379 3411.85   404.6 3420.06
#Mann= 5 ,-1,0
       0     .06       0     170     .12       0   218.2    .045       0
   243.1     .12       0     270      .1       0
Bank Sta=218.2,243.1
XS Rating Curve= 0 ,0
Exp/Cntr(USF)=0,0
Exp/Cntr=0.3,0.1

Type RM Length L Ch R = 1 ,183321  ,238.3,238.3,238.3
XS GIS Cut Line= 2
2334540.18971505621400.8823809242335115.01509301621330.630571683
#Sta/Elev= 30
       0 3456.09     9.5 3453.37    36.3 3442.31    56.4 3431.95    80.6 3422.38
   100.7 3412.96   112.8 3409.47     137 3400.55   153.1 3392.24   161.2 3391.73
   175.7 3384.37   197.4  3377.5   209.5  3372.3   217.6 3371.91   225.7 3373.09
   247.5 3372.03     274 3365.25   294.2 3364.63   306.2 3366.44   330.4 3367.68
   348.73365.225   354.6 3364.26   359.33365.219   386.8 3367.55     407 3376.71
   439.2 3385.93   516.8 3416.34   552.1 3427.24   568.2 3434.29   579.1 3436.64
#Mann= 5 ,-1,0
       0      .1       0     160     .06       0     260     .12       0
   348.7    .045       0   359.3     .12       0
Bank Sta=348.7,359.3
XS Rating Curve= 0 ,0
Exp/Cntr=0.3,0.1

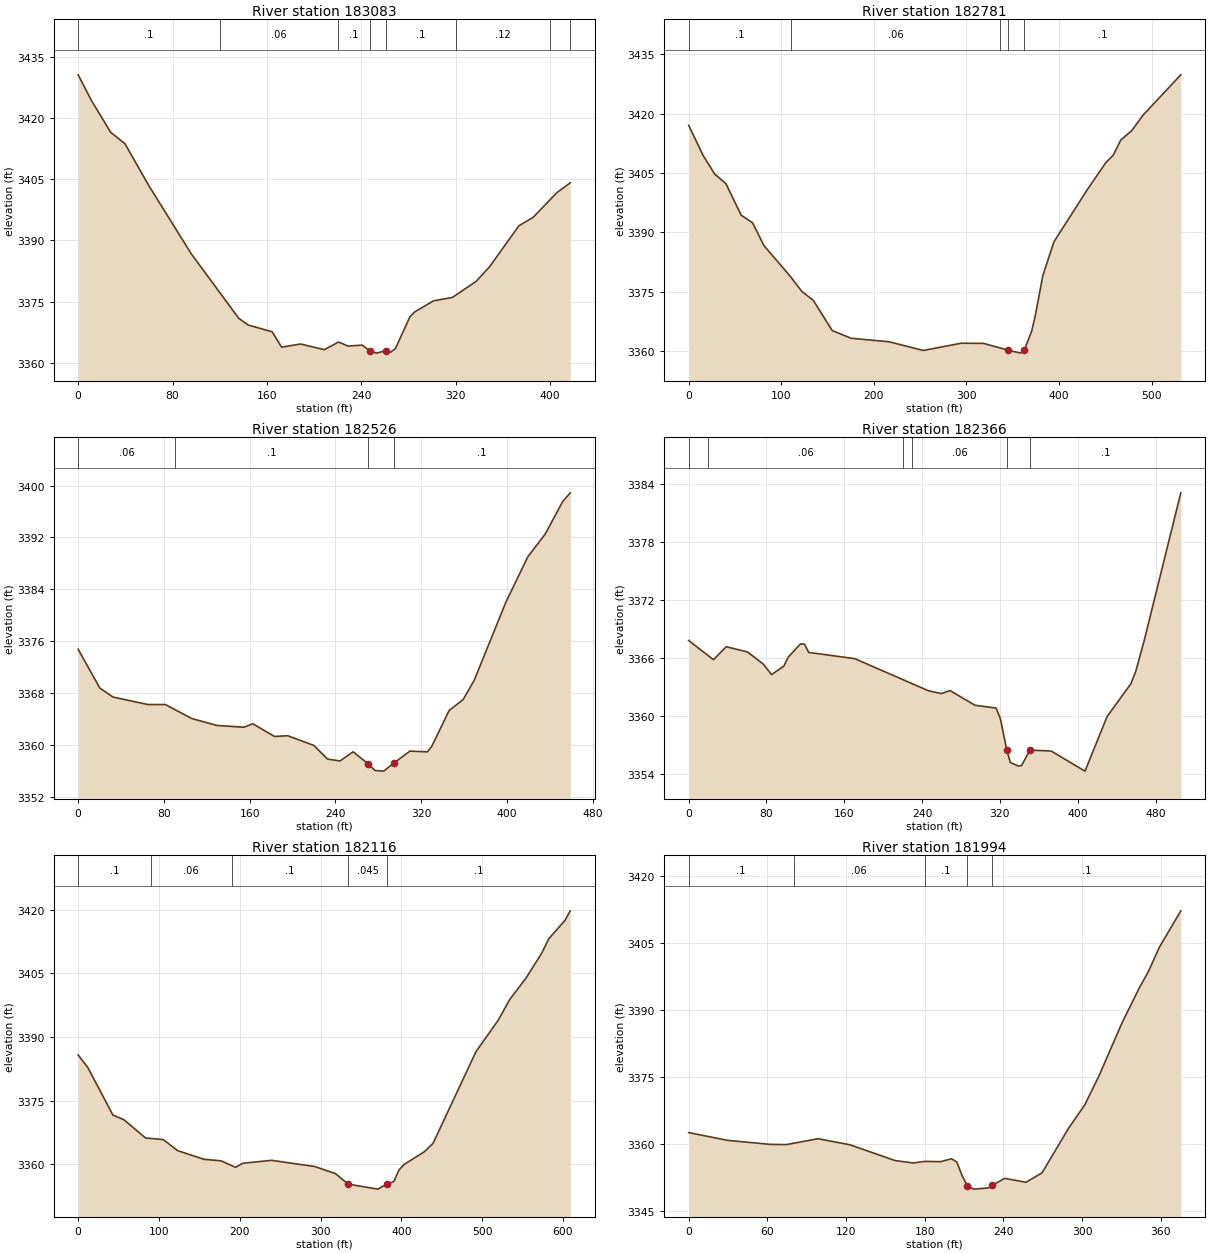
Type RM Length L Ch R = 1 ,183083  ,301.3,301.3,301.3
XS GIS Cut Line= 2
2334676.68119101621608.1187412152335091.51035099621565.297666637
#Sta/Elev= 30
       0 3430.58    11.6 3424.12    27.6 3416.48    39.7  3413.7    59.8 3403.47
      96 3386.65   136.2 3370.87   144.1 3369.26   164.4  3367.6   172.4 3363.84
   188.5  3364.6   208.6 3363.22   220.7 3365.09   228.7  3364.1   240.8 3364.33
   247.2 3362.93   252.8 3362.37   260.7 3362.98   264.9  3362.6   268.9  3363.5
     281  3371.2     285 3372.44   301.1 3375.18   317.2 3376.03   337.3 3379.97
   348.5 3383.48   373.5 3393.59   385.5 3395.64   405.6 3401.69     417 3404.12
#Mann= 8 ,-1,0
       0      .1       0     120     .06       0     220      .1       0
   247.2    .045       0   260.7      .1       0     320     .12       0
     400      .1       0  417.03     .12       0
Bank Sta=247.2,260.7
XS Rating Curve= 0 ,0
Exp/Cntr(USF)=0,0
Exp/Cntr=0.3,0.1

Type RM Length L Ch R = 1 ,182781  ,255.3,255.3,255.3
XS GIS Cut Line= 3
2334668.88824393621885.6067605642334958.27718068621820.644039611
2335193.05644268621814.221986415
#Sta/Elev= 30
       0 3417.09    15.7 3409.45      28 3404.81    40.3 3402.32    56.7 3394.37
      69 3392.45    81.3 3386.69     110 3378.84   122.3 3375.08   134.6 3372.85
   155.1 3365.18   175.5 3363.25   216.5 3362.36   253.4 3360.17   294.4    3362
   318.5 3361.95   344.7 3360.26   358.5 3359.49   362.5 3360.25   370.5 3365.11
   374.5 3369.15   382.5  3379.1   394.5 3387.65   430.5 3400.82   450.5 3407.65
   458.5 3409.53   466.6 3413.36   478.6 3415.77   490.6 3419.64   531.5 3429.86
#Mann= 5 ,-1,0
       0      .1       0     110     .06       0  336.59      .1       0
   344.7    .045       0   362.5      .1       0
Bank Sta=344.7,362.5
XS Rating Curve= 0 ,0
Exp/Cntr=0.3,0.1

Type RM Length L Ch R = 1 ,182526  ,159.8,159.8,159.8
XS GIS Cut Line= 2
2334704.20523367622121.4582096582335155.17571163622035.343244017
#Sta/Elev= 30
       0 3374.77    20.3 3368.78    32.5 3367.41    65.1 3366.25    81.4 3366.25
   105.8 3364.11   129.4 3363.03   154.7 3362.76   162.9 3363.29   183.2 3361.33
   195.4 3361.45   219.9 3359.95   232.7 3357.84   244.3 3357.56   256.5 3358.97
   270.3 3357.14   276.9 3356.09     285 3355.99   294.3  3357.2   309.5 3359.08
   325.8 3358.96   329.8 3359.78   346.1 3365.34   359.2 3367.03   369.5    3370
   399.1 3382.06   419.4    3389   435.7 3392.52     452 3397.54   459.1 3398.88
#Mann= 4 ,-1,0
       0     .06       0      90      .1       0   270.3    .045       0
   294.3      .1       0
Bank Sta=270.3,294.3
XS Rating Curve= 0 ,0
Exp/Cntr(USF)=0,0
Exp/Cntr=0.3,0.1

Type RM Length L Ch R = 1 ,182366  ,250.2,250.2,250.2
XS GIS Cut Line= 3
2334679.80220764622185.0711618352334906.13955102622264.828130455
2335150.79944124622160.281833751
#Sta/Elev= 30
       0 3367.81    25.5 3365.82    38.6 3367.16    60.5 3366.62    76.7 3365.37
    85.2 3364.28    97.9 3365.16   102.2 3366.06   114.9 3367.45   119.1 3367.43
   123.4 3366.57   170.7 3365.93   246.5 3362.61   259.7 3362.32   268.7 3362.63
   294.4 3361.11   316.1 3360.82   320.5 3359.73  327.05  3356.5   330.7  3355.2
   338.8 3354.83   342.2 3354.87   350.9 3356.47   372.7 3356.38   407.5  3354.3
   430.2 3359.94   454.6 3363.32   459.7 3364.62   468.4 3367.82     506 3383.07
#Mann= 6 ,-1,0
       0      .1       0      20     .06       0     220      .1       0
     230     .06       0  327.05    .045       0   350.9      .1       0
Bank Sta=327.05,350.9
XS Rating Curve= 0 ,0
Exp/Cntr(USF)=0,0
Exp/Cntr=0.3,0.1

Type RM Length L Ch R = 1 ,182116  ,122.1,122.1,122.1
XS GIS Cut Line= 2
2334806.59596499622445.2412397532335323.78415655622340.213653106
#Sta/Elev= 30
       0 3385.76    11.8 3382.86      43 3371.61    56.6  3370.5    83.4  3366.2
   105.5  3365.8   123.4 3363.18   155.9 3361.16     177  3360.8   194.8 3359.27
   203.8 3360.23   239.5 3360.92   293.1 3359.45   318.5 3357.78  334.28  3355.3
   370.9 3354.13   382.1 3355.32   390.8 3355.93     397 3358.62   403.5 3359.96
   428.5 3362.95   439.3 3364.94   492.3 3386.52   519.9 3393.96   534.1 3398.82
   554.9 3404.07   573.6 3409.73   582.5 3413.16   602.6 3417.52   609.1 3419.75
#Mann= 5 ,-1,0
       0      .1       0      90     .06       0     190      .1       0
  334.28    .045       0   382.1      .1       0
Bank Sta=334.28,382.1
XS Rating Curve= 0 ,0
Exp/Cntr=0.3,0.1

Type RM Length L Ch R = 1 ,181994  ,147.1,147.1,147.1
XS GIS Cut Line= 2
2334914.96028116622538.4359380222335284.34816009622472.716622138
#Sta/Elev= 30
       0 3362.65    29.7 3360.91    62.2 3360.01    74.4 3359.96    98.7 3361.28
   123.1 3359.91   157.3 3356.39   171.1 3355.85     180  3356.2   192.2 3356.14
   200.3 3356.79   204.4 3356.08   208.4 3353.06   212.5 3350.74   212.5 3350.72
   212.5 3350.71   217.4 3349.99   228.8 3350.27   231.43350.837   240.9  3352.4
   257.2 3351.53   269.4 3353.64   289.7 3363.65   301.9 3368.82   312.6 3375.21
   330.3 3387.17   343.6 3395.07   350.5 3398.72   358.8 3404.12   375.2 3412.31
#Mann= 5 ,-1,0
       0      .1       0      80     .06       0     180      .1       0
   212.5    .045       0   231.4      .1       0
Bank Sta=212.5,231.4
XS Rating Curve= 0 ,0
Exp/Cntr(USF)=0,0
Exp/Cntr=0.3,0.1

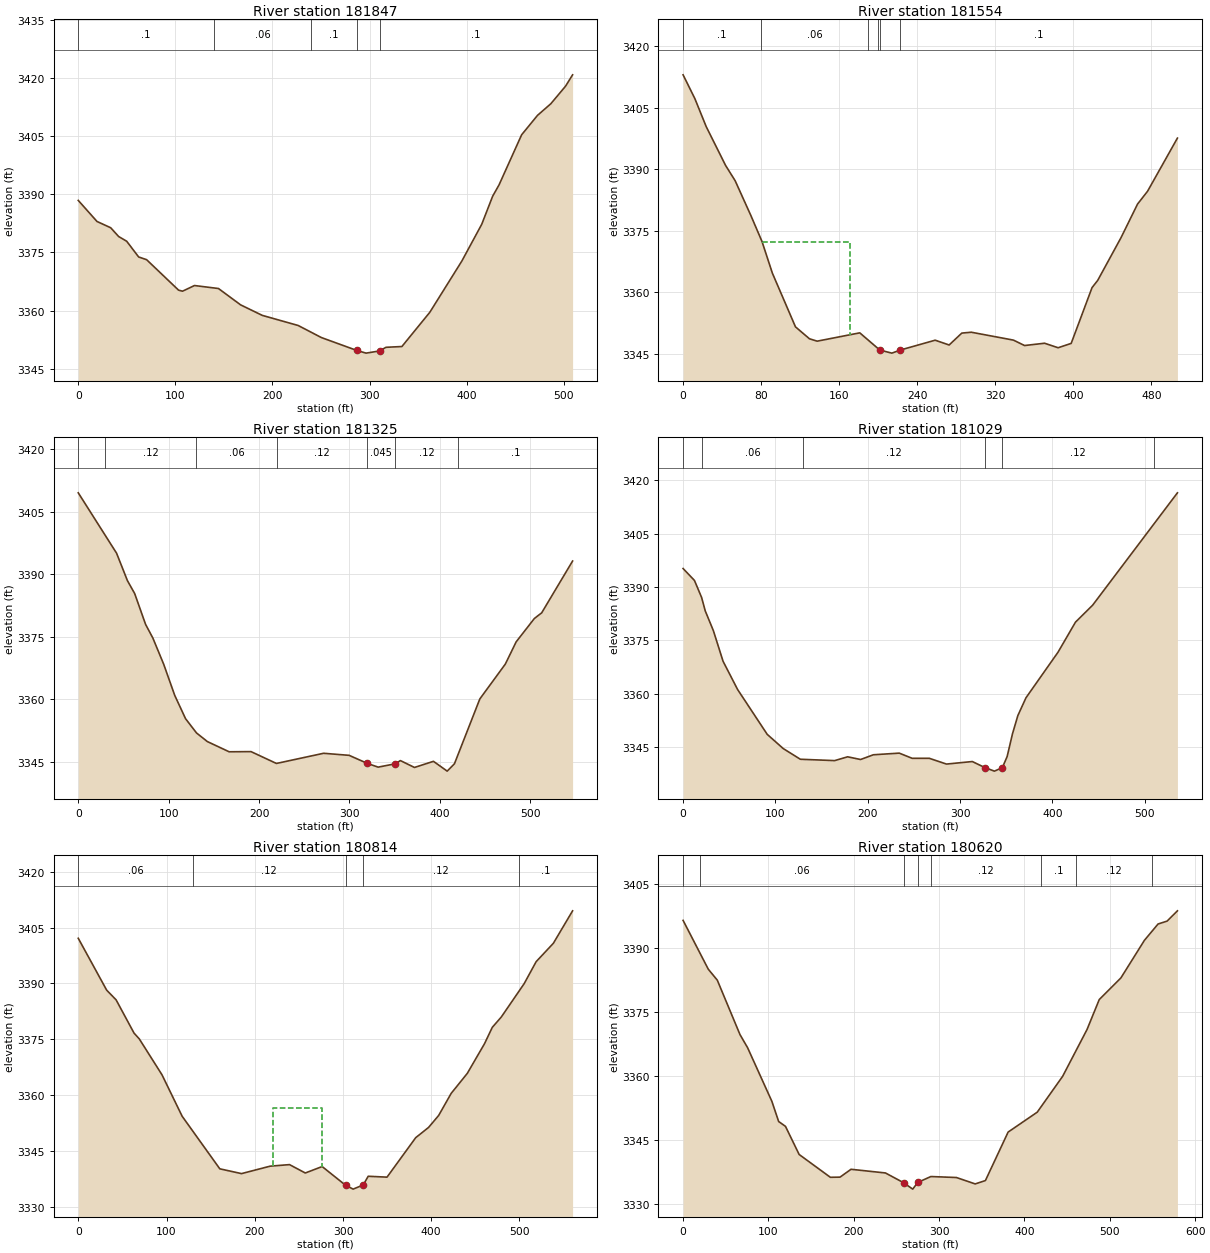
Type RM Length L Ch R = 1 ,181847  ,293.1,293.1,293.1
XS GIS Cut Line= 2
2334859.63374184622713.5914701152335355.28016575622597.369512505
#Sta/Elev= 30
       0 3388.39    19.3 3382.96    33.4 3381.34    41.6 3379.08    49.9 3377.86
    62.2 3373.81    70.4 3373.11   103.3 3365.26   107.4 3364.99   119.7 3366.45
   144.4 3365.68   167.2 3361.47   189.5 3358.76   226.5 3356.15   250.4 3353.04
     287 3349.71   296.4 3349.03   310.3 3349.59   316.9 3350.53   333.3 3350.73
   362.1 3359.57     395 3372.74   415.5 3382.22   426.8 3389.48   433.4 3392.41
   456.6 3405.29     473 3410.31   486.7  3413.3   501.8 3417.81   509.1 3420.75
#Mann= 5 ,-1,0
       0      .1       0     140     .06       0     240      .1       0
     287    .045       0   310.3      .1       0
Bank Sta=287,310.3
XS Rating Curve= 0 ,0
Exp/Cntr=0.3,0.1

Type RM Length L Ch R = 1 ,181554  ,229.2,229.2,229.2
XS GIS Cut Line= 2
2335074.40966747623104.3540914382335372.18615392622694.401531323
#Sta/Elev= 30
       0    3413    12.1 3407.19    23.7 3400.38    43.6 3390.92    53.4 3387.19
    69.4 3378.78    80.9  3372.4    91.5 3364.71   115.2 3351.62   129.5 3348.72
   137.4 3348.13   181.1 3350.16   201.7 3345.96     214 3345.22   222.83345.982
   258.4 3348.37   272.7  3347.2   285.7  3350.1   295.4 3350.31   338.6 3348.39
     350 3347.07   370.5 3347.63   384.4 3346.53   397.8 3347.59   419.2 3361.18
     425 3362.94   448.9 3373.35   465.8 3381.51   476.1 3384.65   506.7 3397.59
#Mann= 6 ,-1,0
       0      .1       0      80     .06       0     190     .12       0
     200      .1       0   201.7    .045       0   222.8      .1       0
#XS Ineff= 1 ,-1
   81.54  171.14 3372.17
Permanent Ineff=
       F
Bank Sta=201.7,222.8
XS Rating Curve= 0 ,0
Exp/Cntr(USF)=0,0
Exp/Cntr=0.3,0.1

Type RM Length L Ch R = 1 ,181325  ,295.1,295.1,295.1
XS GIS Cut Line= 2
2335385.17681669623263.3332847652335438.17273322622719.148402594
#Sta/Elev= 30
       0 3409.55    42.4 3395.06    54.4 3388.48    62.4 3385.39    74.5 3377.98
    82.5 3374.73    94.6 3368.38   106.7 3360.97   118.7 3355.36   130.8 3351.95
   142.8 3349.88   166.9 3347.43   191.1 3347.47   219.2 3344.63   271.4 3347.07
   299.6 3346.58   319.8 3344.64   331.7 3343.75   350.8 3344.55   356.3 3345.32
   371.9 3343.67   392.9 3345.14   408.1 3342.79   416.1 3344.55   444.2 3360.11
   472.4 3368.47   484.4 3373.81   504.5  3379.4   512.6 3380.76   546.8 3393.19
#Mann= 7 ,-1,0
       0      .1       0      30     .12       0     130     .06       0
     220     .12       0   319.8    .045       0   350.8     .12       0
     420      .1       0
Bank Sta=319.8,350.8
XS Rating Curve= 0 ,0
Exp/Cntr=0.3,0.1

Type RM Length L Ch R = 1 ,181029  ,215.7,215.7,215.7
XS GIS Cut Line= 2
2335516.45467834623250.3575361612335790.01315702622790.281912929
#Sta/Elev= 30
       0 3395.18    12.3 3391.84      20  3387.1      24 3383.29    32.8 3377.74
    43.3 3369.15      59 3361.25    91.1 3348.65   108.4 3344.67     127 3341.66
   164.1 3341.28   178.2 3342.35   192.2 3341.59   206.1 3342.92   234.1 3343.38
     248 3341.93   266.6 3341.93   285.2 3340.31   313.2 3341.02   327.1 3339.29
   337.1 3338.33   345.7 3339.29   350.9 3342.41   356.7 3348.81   362.5 3353.91
   371.3 3358.91     406  3371.7   424.9 3380.13   443.5  3384.9   535.3 3416.42
#Mann= 6 ,-1,0
       0     .12       0      20     .06       0     130     .12       0
   327.1    .045       0   345.7     .12       0     510      .1       0
Bank Sta=327.1,345.7
XS Rating Curve= 0 ,0
Exp/Cntr(USF)=0,0
Exp/Cntr=0.3,0.1

Type RM Length L Ch R = 1 ,180814  ,194.2,194.2,194.2
XS GIS Cut Line= 2
2335586.34377304623316.5473641412336027.86532411622971.764670882
#Sta/Elev= 30
       0 3402.15    32.2  3388.2    42.9 3385.59    63.2 3376.66    69.2 3375.08
    94.9 3365.44   117.7 3354.31   160.4 3340.16     185 3338.87   217.4 3340.87
   239.4 3341.29   257.3 3339.04   276.4 3340.77   302.9 3335.75   311.5  3334.7
   322.9 3335.82   328.6 3338.16   349.9 3337.92   382.4 3348.53     397 3351.29
   408.4  3354.5   422.6 3360.44   440.9 3365.83   460.4 3373.81   469.2  3378.2
   479.4 3380.98   505.3 3389.94   518.9 3395.86   538.4  3400.8   560.2 3409.53
#Mann= 5 ,-1,0
       0     .06       0     130     .12       0   302.9    .045       0
   322.9     .12       0     500      .1       0
#XS Ineff= 1 ,-1
  220.47  276.153356.568
Permanent Ineff=
       F
Bank Sta=302.9,322.9
XS Rating Curve= 0 ,0
Exp/Cntr=0.3,0.1

Type RM Length L Ch R = 1 ,180620  ,302.3,302.3,302.3
XS GIS Cut Line= 2
2335762.03558533623443.0919188662336197.24225596623060.731772531
#Sta/Elev= 30
       0 3396.36    29.5 3384.93    40.1 3382.35    66.7 3369.59    75.6 3366.52
     104 3353.98     112 3349.22     120 3348.09     136  3341.5   172.6 3336.15
   183.9 3336.19   196.8 3338.03   237.1 3337.17   258.4 3334.89   269.1 3333.38
     275 3334.95   290.4 3336.33   320.3  3336.1   342.3  3334.6   354.3 3335.39
   380.9 3346.75     415 3351.41   444.8 3359.82   473.4  3370.8   487.7 3377.81
   513.1 3382.89   540.6 3391.68   556.6 3395.51   567.2 3396.19   579.3  3398.6
#Mann= 8 ,-1,0
       0      .1       0      20     .06       0   258.4    .045       0
     275     .06       0     290     .12       0     420      .1       0
     460     .12       0     550      .1       0
Bank Sta=258.4,275
XS Rating Curve= 0 ,0
Exp/Cntr(USF)=0,0
Exp/Cntr=0.3,0.1

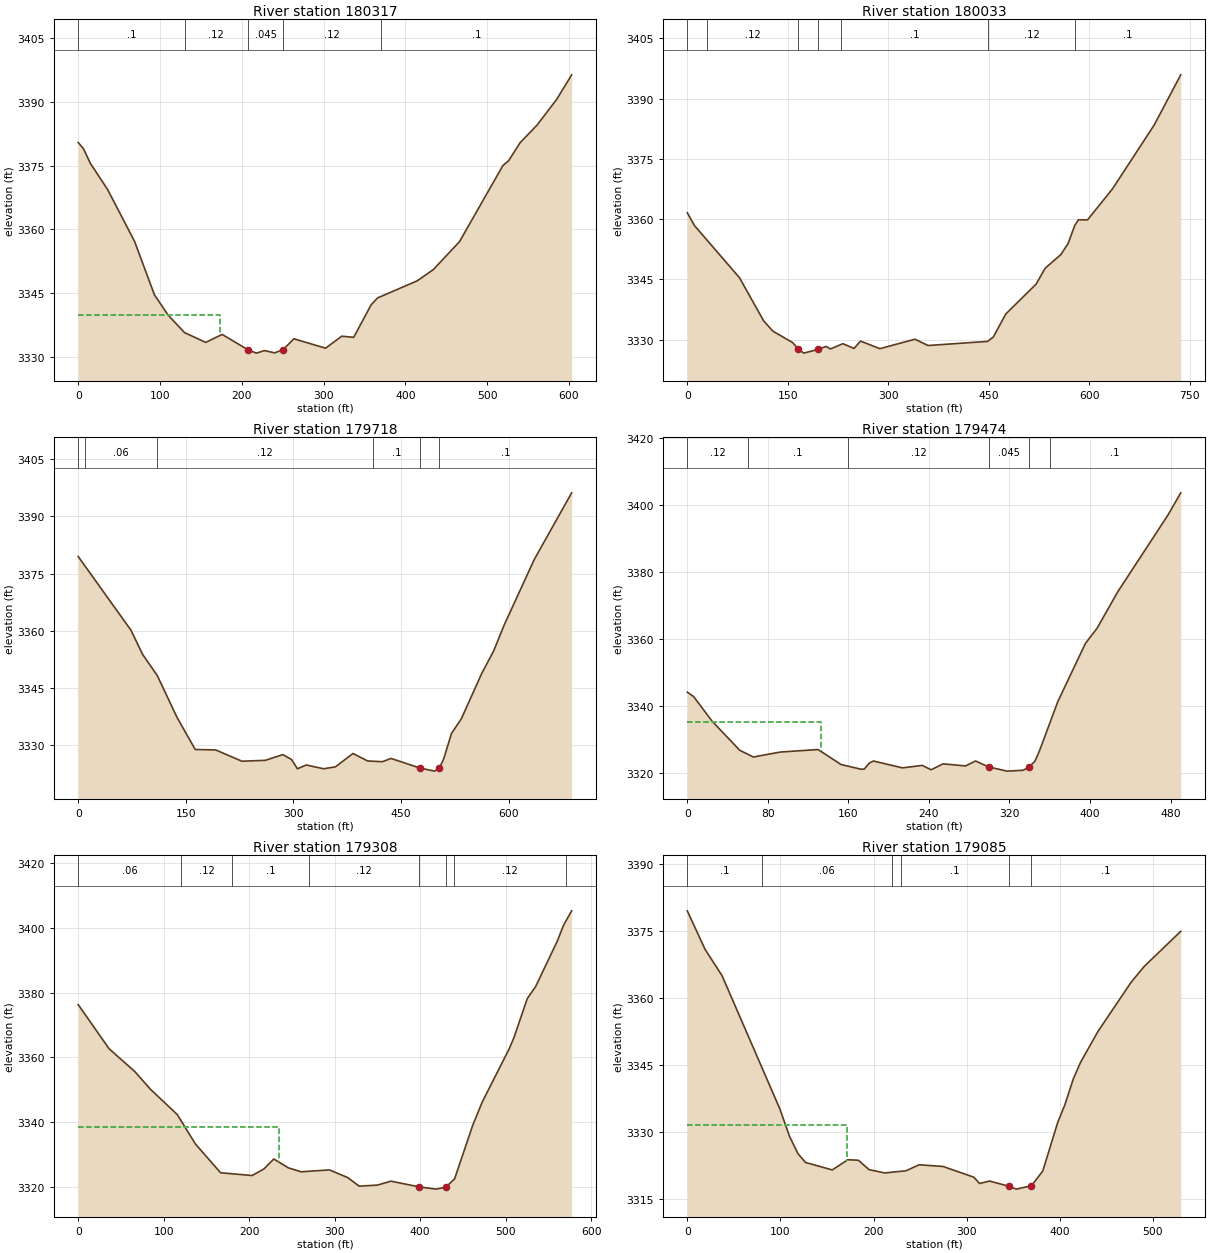
Type RM Length L Ch R = 1 ,180317  ,283.8,283.8,283.8
XS GIS Cut Line= 2
2335967.62536915623605.569551077 2336463.0410524623261.214259347
#Sta/Elev= 30
       0 3380.43     6.4 3378.99      15 3375.49    35.7 3369.47    68.9 3357.21
    93.2 3344.65   109.9 3339.89     130 3335.77   155.9 3333.47     176 3335.35
   207.6 3331.73   217.9 3330.95   227.7 3331.55   240.3 3331.01   250.7  3331.8
   263.7 3334.32   302.4 3332.11   322.2 3334.93   336.8 3334.66   358.1 3342.29
     366 3343.92   414.5 3347.94   434.2 3350.58   466.2 3357.15   519.3 3375.04
   526.3 3376.18   540.3  3380.4   560.9 3384.51   585.2 3390.63   603.3 3396.34
#Mann= 5 ,-1,0
       0      .1       0     130     .12       0   207.6    .045       0
   250.7     .12       0     370      .1       0
#XS Ineff= 2 , 0
          173.32 3339.94
Permanent Ineff=
       F       F
Bank Sta=207.6,250.7
XS Rating Curve= 0 ,0
Exp/Cntr=0.3,0.1

Type RM Length L Ch R = 1 ,180033  ,315.3,315.3,315.3
XS GIS Cut Line= 3
2336149.71913286623752.9372592952336436.40289208623666.586729409
2336823.25326597623462.799478878
#Sta/Elev= 30
       0 3361.59    10.9 3358.36    77.8 3345.44   114.1 3334.64   127.9 3332.08
   157.1 3329.27   165.6 3327.67   173.8 3326.62   195.3 3327.55   207.2 3328.28
   213.7 3327.66   232.3 3328.97     249 3327.79   258.6 3329.62   287.5 3327.73
   339.8 3330.08   359.5 3328.52   448.4 3329.54   456.9 3330.64   475.5 3336.37
   520.7  3343.8   534.3 3347.77   557.9  3351.2   568.5 3353.92   578.6 3358.49
     584 3359.84   597.5 3359.81   634.9 3367.56   697.1 3383.46   736.7 3395.95
#Mann= 7 ,-1,0
       0     .06       0      30     .12       0   165.6    .045       0
   195.3     .12       0     230      .1       0  449.41     .12       0
  579.41      .1       0
Bank Sta=165.6,195.3
XS Rating Curve= 0 ,0
Exp/Cntr(USF)=0,0
Exp/Cntr=0.3,0.1

Type RM Length L Ch R = 1 ,179718  ,244.6,244.6,244.6
XS GIS Cut Line= 3
2336067.93966888623823.5921443382336403.33479821623887.045276915
2336742.86498039623955.834348622
#Sta/Elev= 30
       0  3379.5    73.6 3360.15    89.8 3353.81   110.2 3348.28   137.6 3337.35
   163.1 3328.88   191.6 3328.77   228.2 3325.81   260.8 3326.04   285.2 3327.54
   297.4 3326.26   305.6 3323.82   317.8 3324.82   342.2 3323.83   358.5 3324.33
     383 3327.83   403.4 3325.88   423.8 3325.68   436.1 3326.53   476.2 3324.03
   496.6 3323.21   503.4 3324.01   509.5 3326.46   520.3 3333.09     534 3336.93
   562.6 3348.89   578.9 3354.66   593.8 3361.55   635.7 3378.73   687.8  3396.2
#Mann= 6 ,-1,0
       0      .1       0      10     .06       0     110     .12       0
  411.34      .1       0   476.2    .045       0   503.4      .1       0
Bank Sta=476.2,503.4
XS Rating Curve= 0 ,0
Exp/Cntr=0.3,0.1

Type RM Length L Ch R = 1 ,179474  ,165.1,165.1,165.1
XS GIS Cut Line= 2
 2336118.6329421 623953.270488632336546.93157033624191.597951115
#Sta/Elev= 30
       0 3344.22     6.3  3342.9    24.6 3335.56    52.1 3326.87    65.6 3324.85
    92.2 3326.33   129.9 3327.09   152.8  3322.6   172.6 3321.21   175.7 3321.24
   180.8 3323.04   184.9 3323.66   213.7 3321.61   233.4 3322.35   242.2 3321.05
     254 3322.81   276.4 3322.19   286.3 3323.67   299.3  3321.9   317.6 3320.64
   333.4 3320.89   339.3 3321.77   345.3 3323.63   349.7 3326.62     368 3341.39
   395.4 3358.76   406.9 3363.25   427.5 3374.16   477.5 3397.14   490.1 3403.73
#Mann= 6 ,-1,0
       0     .12       0      60      .1       0     160     .12       0
   299.3    .045       0   339.3     .12       0     360      .1       0
#XS Ineff= 2 , 0
          132.55 3335.26
Permanent Ineff=
       F       F
Bank Sta=299.3,339.3
XS Rating Curve= 0 ,0
Exp/Cntr(USF)=0,0
Exp/Cntr=0.3,0.1

Type RM Length L Ch R = 1 ,179308  ,223.2,223.2,223.2
XS GIS Cut Line= 2
2335996.54414732 623897.923983632336376.58806548624332.239715234
#Sta/Elev= 30
       0  3376.3    36.2 3362.64    66.3 3355.59    84.5 3350.15   115.9 3342.31
   137.2 3333.19   166.5 3324.34   203.3 3323.48   216.9 3325.46   228.8 3328.59
   245.8 3325.85   260.6 3324.64   293.8 3325.22   315.3 3322.84   328.6  3320.2
   349.8 3320.52   365.8 3321.74   398.9 3319.97   418.6 3319.28   430.1 3319.91
   440.2 3322.47   461.4 3339.01   472.6 3346.25     504 3362.63   509.7 3366.16
   525.2 3378.17     535  3381.9   560.5 3396.05   567.7  3400.9   577.1 3405.29
#Mann= 8 ,-1,0
       0     .06       0     120     .12       0     180      .1       0
     270     .12       0   398.9    .045       0   430.1      .1       0
     440     .12       0     570      .1       0
#XS Ineff= 2 , 0
          234.56 3338.35
Permanent Ineff=
       F       F
Bank Sta=398.9,430.1
XS Rating Curve= 0 ,0
Exp/Cntr=0.3,0.1

Type RM Length L Ch R = 1 ,179085  ,282.2,282.2,282.2
XS GIS Cut Line= 2
2335821.58711929624063.7991668842336198.07542959624436.833455991
#Sta/Elev= 30
       0 3379.47      19 3370.89    37.4 3364.93    99.4 3335.16   109.9 3328.95
   118.8 3325.16     127 3323.15   155.7 3321.49   172.5 3323.77   183.8 3323.65
   195.2 3321.56     212 3320.81     235  3321.3   248.9 3322.64   274.7 3322.26
   307.7 3319.87   313.9 3318.45   324.6    3319     345 3317.86   353.5 3317.19
   369.7 3317.96   381.8 3321.24   397.8 3332.07   405.5 3336.04   414.7 3341.92
   422.5 3345.61   441.2 3352.51   476.6 3363.46   490.7 3367.01     530 3374.89
#Mann= 6 ,-1,0
       0      .1       0      80     .06       0     220     .12       0
     230      .1       0     345    .045       0   369.7      .1       0
#XS Ineff= 2 , 0
          171.14 3331.65
Permanent Ineff=
       F       F
Bank Sta=345,369.7
XS Rating Curve= 0 ,0
Exp/Cntr(USF)=0,0
Exp/Cntr=0.3,0.1