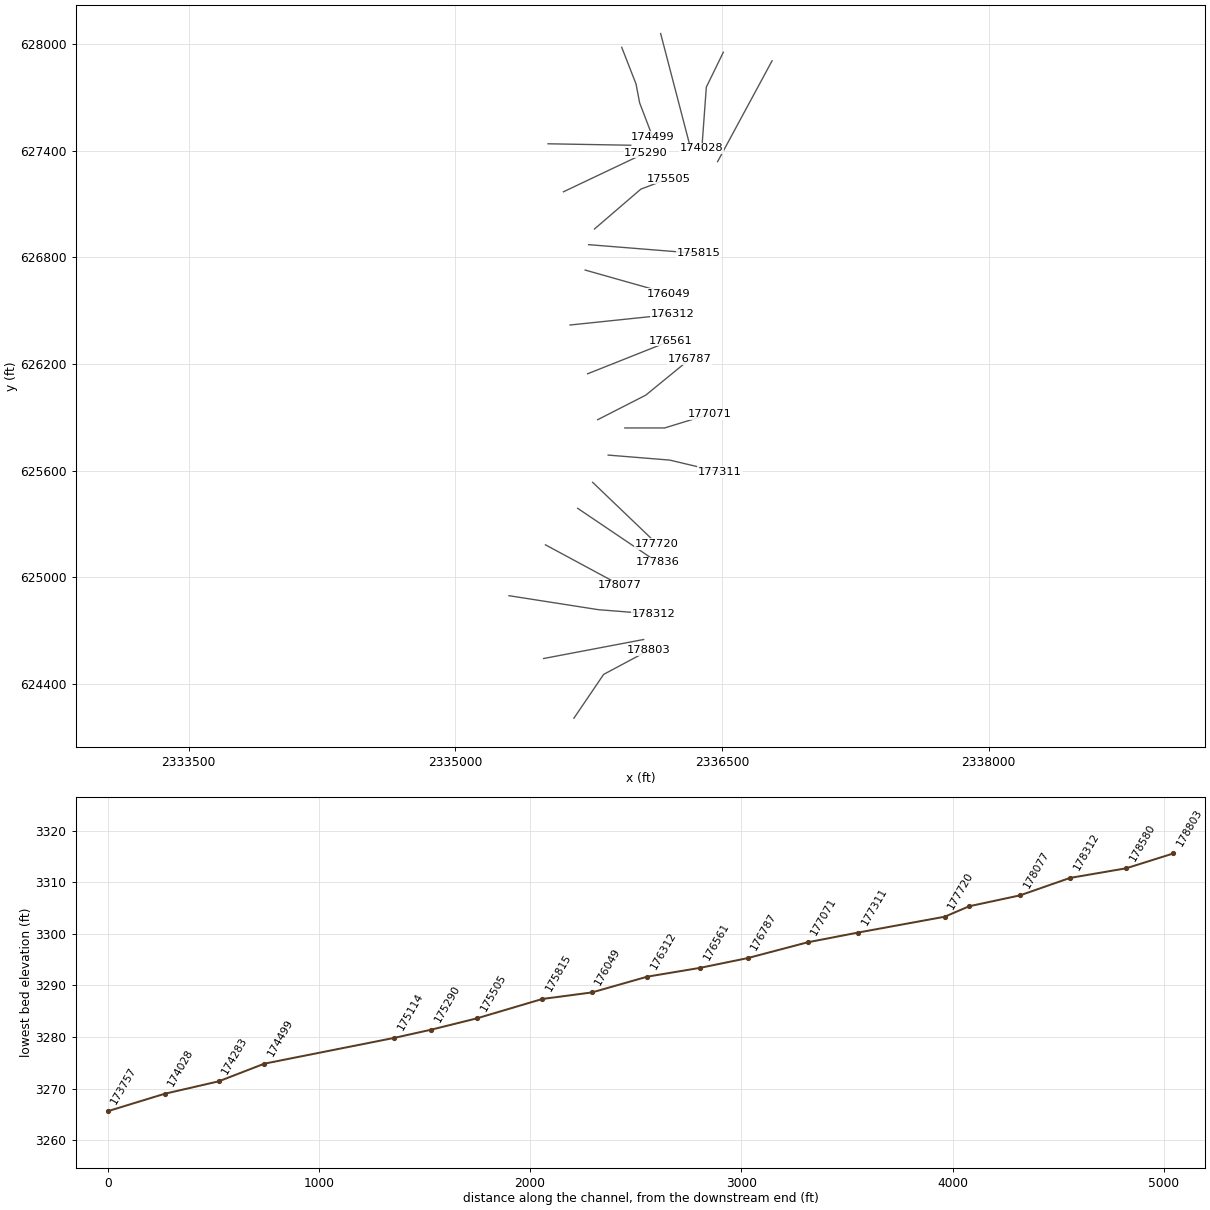
HEC-RAS study LAURELFK.prj: LAURELFK

--- LAURELFK.g01 (geometry) --- (continued)

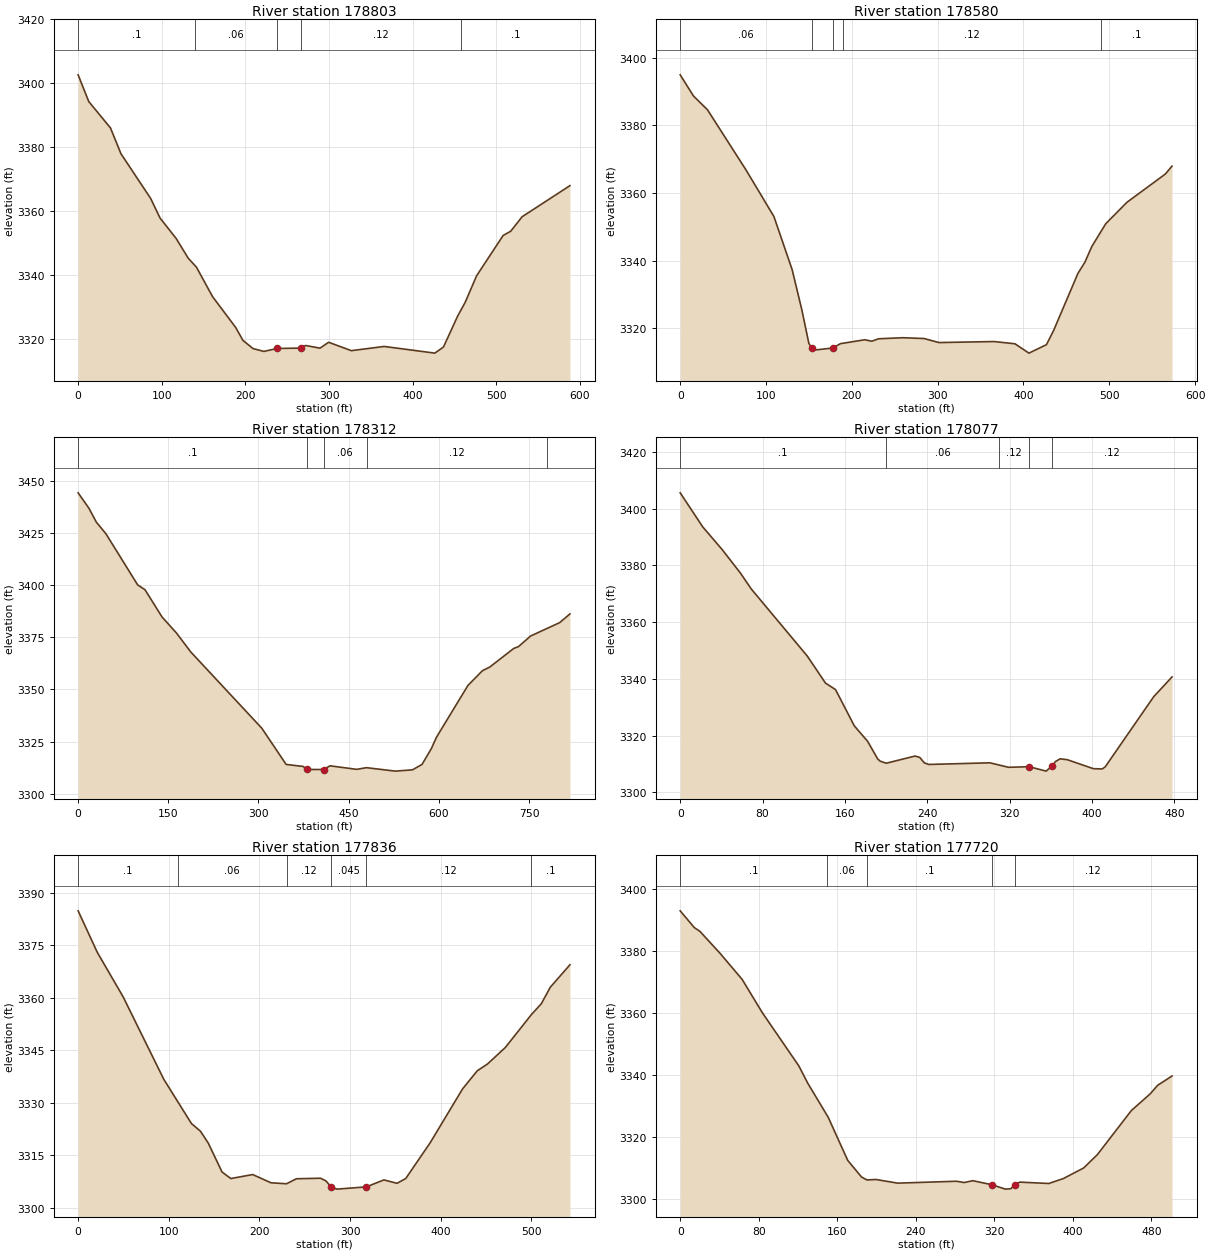
Type RM Length L Ch R = 1 ,178803  ,223.2,223.2,223.2
XS GIS Cut Line= 3
2335667.43190726624208.2245903112335834.80890726 624454.74874032
2336090.61850243624591.331983073
#Sta/Elev= 30
       0 3402.62    12.7 3394.27    38.7    3386    51.2 3377.94    86.8 3363.92
    97.9 3357.84   117.2 3351.44   131.7 3345.24   141.4 3342.49   160.7 3333.26
   188.4 3323.59     197 3319.58   209.1    3317   222.1 3316.12   238.1 3317.04
   266.2 3317.15   271.9 3317.97   289.2 3317.14   299.5 3318.97   326.7 3316.35
   365.8 3317.67   426.5 3315.58   436.8  3317.5   453.7 3327.15   462.8  3331.5
   476.4 3339.77   508.1 3352.37   517.2 3353.71   530.8 3358.23     588 3367.96
#Mann= 5 ,-1,0
       0      .1       0     140     .06       0   238.1    .045       0
   266.2     .12       0  457.98      .1       0
Bank Sta=238.1,266.2
XS Rating Curve= 0 ,0
Exp/Cntr=0.3,0.1

Type RM Length L Ch R = 1 ,178580  ,267.3,267.3,267.3
XS GIS Cut Line= 2
2335496.90912692 624543.908113052336059.91458177624650.982770108
#Sta/Elev= 30
       0 3394.91    15.5 3388.65    31.8 3384.59    76.6 3366.85   109.2 3353.06
   130.5 3337.33   141.8 3325.44   149.9 3315.61   153.3 3314.18     158 3313.65
   178.1 3314.22   186.6 3315.49   215.1 3316.65   223.2 3316.22   231.3 3316.94
   259.8 3317.25   284.3 3317.01   301.5 3315.82   365.7 3316.12   390.1 3315.46
   406.4  3312.7   426.8  3315.2     435 3319.31   463.4 3336.22   471.6 3339.57
   479.7 3344.23     496 3350.96   520.6 3357.26   565.2 3365.58   573.1 3367.94
#Mann= 5 ,-1,0
       0     .06       0   153.3    .045       0   178.1     .06       0
     190     .12       0     490      .1       0
Bank Sta=153.3,178.1
XS Rating Curve= 0 ,0
Exp/Cntr(USF)=0,0
Exp/Cntr=0.3,0.1

Type RM Length L Ch R = 1 ,178312  ,235.6,235.6,235.6
XS GIS Cut Line= 3
2335302.33977742624897.3303895192335805.42416532 624818.63212984
2336113.40407582624794.318333874
#Sta/Elev= 30
       0 3444.38    18.1 3436.91    30.2 3430.35    46.4 3424.66      99  3400.2
   111.2 3397.89   139.5 3384.83   163.8 3377.02   187.3 3368.03   305.5 3331.42
     346 3314.04   374.3 3313.06   381.2 3311.62   408.53311.585   418.9 3313.37
   463.4 3311.67   479.6 3312.48   527.7 3310.82   556.1 3311.43   572.1 3314.05
   587.5 3321.61   596.2 3327.15   648.4 3351.94   672.5 3359.02   684.5 3360.73
   724.6 3369.69   732.6  3370.6   752.7 3375.67   800.9 3382.07   818.1 3386.27
#Mann= 5 ,-1,0
       0      .1       0   381.2    .045       0   408.5     .06       0
     480     .12       0   779.2      .1       0
Bank Sta=381.2,408.5
XS Rating Curve= 0 ,0
Exp/Cntr=0.3,0.1

Type RM Length L Ch R = 1 ,178077  ,240.5,240.5,240.5
XS GIS Cut Line= 2
2335507.33886113625183.5486892492335927.84176353624956.930358616
#Sta/Elev= 30
       0  3405.6    21.9 3393.59    40.8 3385.57    58.5  3377.3    69.1 3371.66
   123.4 3348.05   141.1 3338.51   150.9 3336.19   169.1 3323.43   182.1 3317.94
   191.8 3311.77   194.3 3310.95   200.2 3310.24   228.1 3312.77   232.7 3312.28
   237.2 3310.34   241.5  3309.8   300.8 3310.38     319  3308.8     339 3309.01
   355.4 3307.45   360.9 3309.14   364.5 3310.82     369 3311.79     376 3311.48
   401.3 3308.32   409.9 3308.22   412.8 3308.95     460 3333.74   477.7 3340.67
#Mann= 5 ,-1,0
       0      .1       0     200     .06       0     310     .12       0
     339    .045       0   360.9     .12       0
Bank Sta=339,360.9
XS Rating Curve= 0 ,0
Exp/Cntr(USF)=0,0
Exp/Cntr=0.3,0.1

Type RM Length L Ch R = 1 ,177836  ,116.1,116.1,116.1
XS GIS Cut Line= 2
2335688.54107257625388.9117790392336138.37539114625085.272258058
#Sta/Elev= 30
       0 3384.77      21 3372.99    49.6 3360.25    94.6 3336.65     125 3324.07
     135 3321.87   143.6 3318.48   158.8 3310.23   168.5 3308.36   192.6  3309.5
   212.8 3307.15     230 3306.87   240.9  3308.3   267.5 3308.45   273.3 3307.72
     279 3306.03   285.5 3305.34   318.1 3305.98   337.4 3307.97   351.9    3307
   361.5 3308.37   388.5 3318.59   424.2 3333.94   440.4 3339.11   451.9 3341.09
   471.4 3345.77     500  3355.1   511.1 3358.26     521 3362.96   542.7 3369.38
#Mann= 6 ,-1,0
       0      .1       0     110     .06       0     230     .12       0
     279    .045       0   318.1     .12       0     500      .1       0
Bank Sta=279,318.1
XS Rating Curve= 0 ,0
Exp/Cntr=0.3,0.1

Type RM Length L Ch R = 1 ,177720  ,408.8,408.8,408.8
XS GIS Cut Line= 2
2335772.84217538625535.091324241 2336134.8255944 625188.51261794
#Sta/Elev= 30
       0 3392.99    14.3 3387.62    20.1 3386.37    40.5 3379.34    63.1 3370.91
    83.7 3360.16   120.9 3343.01     130 3337.42   150.8 3326.47   170.7 3312.58
   184.8  3307.2   190.4 3306.26   199.4 3306.42   221.6 3305.24   281.5 3305.85
   289.4 3305.43   298.1 3306.03   317.7 3304.72   331.3 3303.31   336.9 3303.45
  340.73 3304.72     346 3305.57   375.6 3305.13   390.3  3306.7   411.1 3310.13
     425 3314.41   459.7 3328.64     479 3334.05   486.4 3336.75   501.1 3339.77
#Mann= 5 ,-1,0
       0      .1       0     150     .06       0     190      .1       0
   317.7    .045       0  340.73     .12       0
Bank Sta=317.7,340.73
XS Rating Curve= 0 ,0
Exp/Cntr(USF)=0,0
Exp/Cntr=0.3,0.1

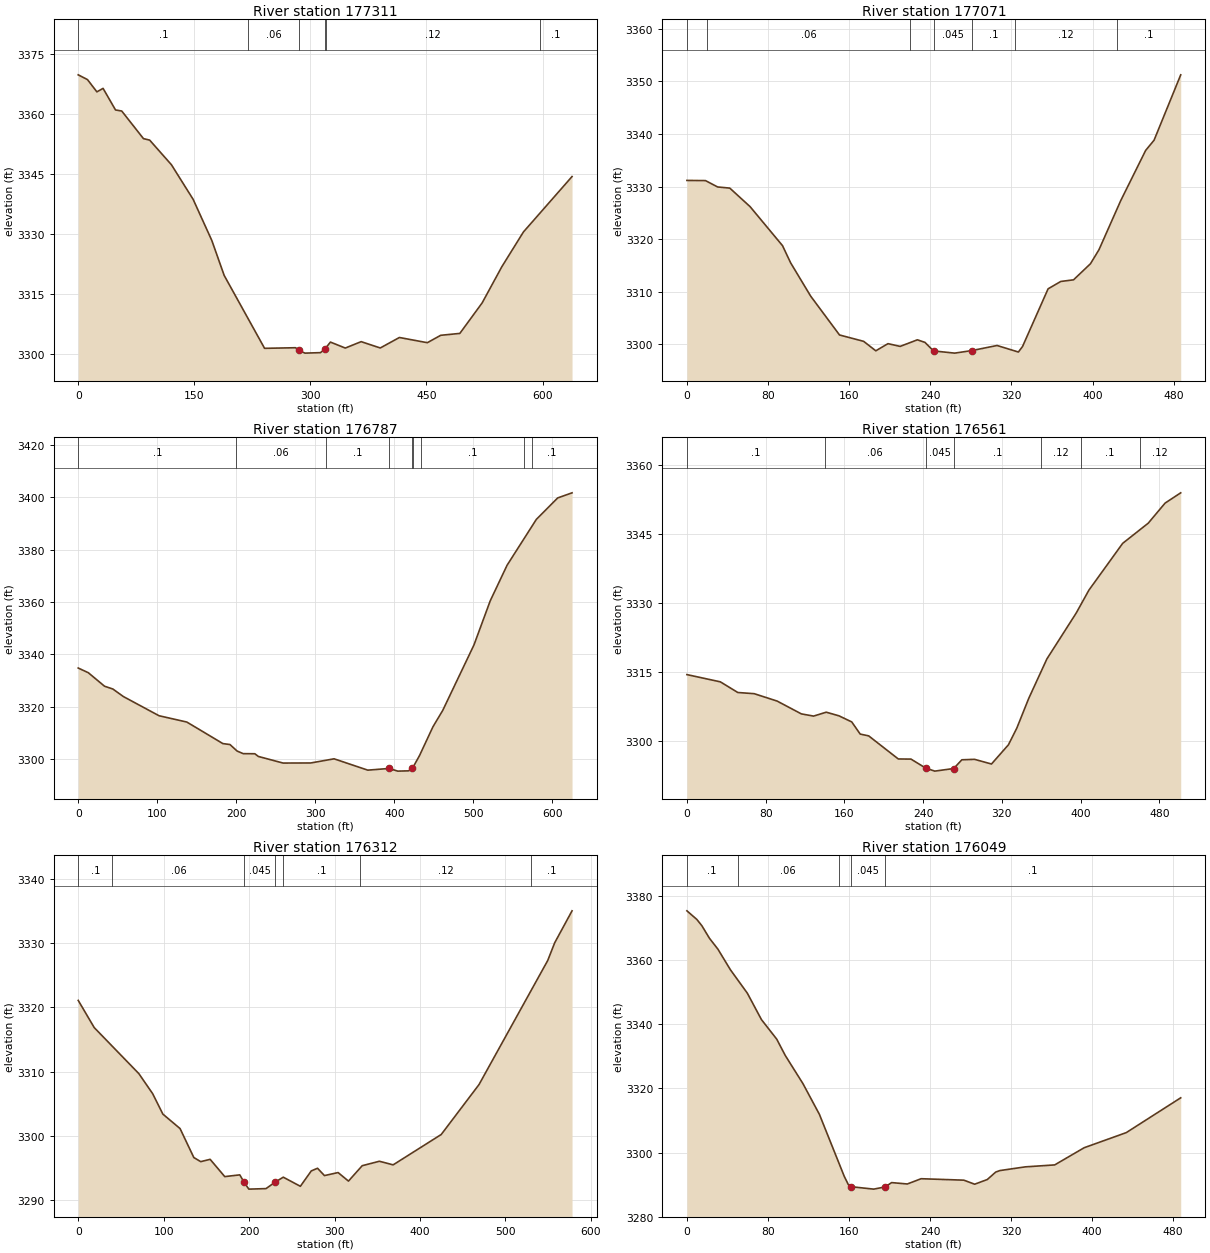
Type RM Length L Ch R = 1 ,177311  ,240.3,240.3,240.3
XS GIS Cut Line= 3
2335860.16466451625688.2876121022336206.29568467625660.239018549
2336489.25777904625593.120387898
#Sta/Elev= 30
       0 3369.86      12 3368.66    24.1  3365.6    32.1 3366.47    48.2 3361.07
    56.2 3360.81    84.3  3353.9    92.3 3353.53   120.4 3347.38   148.5 3338.71
   172.6 3328.44   188.6 3319.68   240.8 3301.45   280.9  3301.6   284.8 3300.95
     293 3300.25     313 3300.37   318.4 3301.19   325.9 3303.01   345.1 3301.52
   365.6 3303.12   390.3 3301.54     415 3304.16   451.1 3302.86   468.4 3304.71
   493.1 3305.18   521.9  3312.8   547.4 3321.87   575.3 3330.56   638.1 3344.42
#Mann= 6 ,-1,0
       0      .1       0     220     .06       0   284.8    .045       0
   318.4     .06       0     320     .12       0  597.27      .1       0
Bank Sta=284.8,318.4
XS Rating Curve= 0 ,0
Exp/Cntr=0.3,0.1

Type RM Length L Ch R = 1 ,177071  ,283.8,283.8,283.8
XS GIS Cut Line= 3
2335953.83060183625840.9778839952336177.77483616625840.977883995
2336429.25319767625918.073440076
#Sta/Elev= 30
       0 3331.17    18.3 3331.14    30.3 3329.93    42.3 3329.71    62.3 3326.19
    94.3 3318.77   102.3 3315.51   122.1 3309.17   150.5  3301.8   174.3 3300.59
   186.3 3298.79   198.3 3300.15   210.3 3299.63   227.3 3300.88   234.8 3300.39
   243.2 3298.77   264.1 3298.35   280.8 3298.83   305.9  3299.8   326.9 3298.56
     331 3299.61   356.2 3310.57   368.7 3311.97   381.3 3312.28     398 3315.34
   406.4 3318.01   427.8 3327.32   452.4 3336.87   460.7 3338.81     487 3351.24
#Mann= 7 ,-1,0
       0      .1       0      20     .06       0     220      .1       0
   243.2    .045       0   280.8      .1       0  323.94     .12       0
  423.94      .1       0
Bank Sta=243.2,280.8
XS Rating Curve= 0 ,0
Exp/Cntr(USF)=0,0
Exp/Cntr=0.3,0.1

Type RM Length L Ch R = 1 ,176787  ,226.6,226.6,226.6
XS GIS Cut Line= 3
2335801.19002849625887.3624350242336071.58475122626025.484875608
2336320.26371716626228.659451702
#Sta/Elev= 30
       0 3334.74    12.8 3332.94    33.3 3327.78    43.8 3326.71    57.1 3323.83
   102.2 3316.49   137.4 3314.07     183 3305.83     192 3305.46     201 3302.98
   208.7 3301.98   223.4 3301.94   227.9 3300.91   259.2 3298.38   294.2 3298.41
   323.7    3300   366.4 3295.66   393.33296.315   404.3 3295.29     418  3295.4
   422.9 3296.39   431.8 3301.23   448.8 3312.25   461.2 3318.53   500.7 3343.57
   521.3 3360.46   542.6 3374.07   579.6  3391.6   606.6 3399.82   624.8 3401.78
#Mann= 9 ,-1,0
       0      .1       0     200     .06       0  313.63      .1       0
   393.3    .045       0   422.9      .1       0  423.63     .12       0
  433.63      .1       0  563.63     .12       0  573.63      .1       0
Bank Sta=393.3,422.9
XS Rating Curve= 0 ,0
Exp/Cntr=0.3,0.1

Type RM Length L Ch R = 1 ,176561  ,248.6,248.6,248.6
XS GIS Cut Line= 2
2335744.57123533626145.6888913642336210.81578877626331.085347654
#Sta/Elev= 30
       0 3314.42      34 3312.84    51.7 3310.52    68.4 3310.26    91.7 3308.65
   116.3 3305.86   128.7 3305.38   141.6 3306.23   154.5 3305.44   167.5 3304.11
   176.1 3301.46   184.7 3301.07   214.8 3296.04   227.7 3296.01   242.6 3294.06
   251.9 3293.39   271.13293.959   279.4 3295.86   292.3 3295.96   309.5 3294.94
   326.7 3299.12   335.3 3302.79   347.3 3309.21   365.8 3317.83   395.6 3327.83
   408.5 3332.82   442.8 3343.01   468.8 3347.41   485.9 3351.78   501.8 3354.02
#Mann= 7 ,-1,0
       0      .1       0     140     .06       0   242.6    .045       0
   271.1      .1       0     360     .12       0     400      .1       0
     460     .12       0
Bank Sta=242.6,271.1
XS Rating Curve= 0 ,0
Exp/Cntr(USF)=0,0
Exp/Cntr=0.3,0.1

Type RM Length L Ch R = 1 ,176312  ,262.9,262.9,262.9
XS GIS Cut Line= 2
2335645.58614733626420.0737797082336220.49069562626480.177734538
#Sta/Elev= 30
       0 3321.08    18.7 3316.85      71 3309.67    87.1 3306.56    99.1 3303.37
   119.2 3301.12   135.3 3296.61   143.4 3295.97   154.4 3296.33   171.5 3293.64
   189.1 3293.91   194.33292.727   199.7 3291.69   219.8 3291.77   230.63292.791
     240 3293.55     260 3292.13   272.8 3294.53   280.1 3294.94   288.2  3293.8
   304.2 3294.27   316.3 3292.94   332.4 3295.34   352.5 3296.03   368.6 3295.47
   424.9  3300.2   469.1 3307.97   549.6 3327.31   557.6 3330.03     578 3335.03
#Mann= 7 ,-1,0
       0      .1       0      40     .06       0   194.3    .045       0
   230.6     .06       0     240      .1       0     330     .12       0
     530      .1       0
Bank Sta=194.3,230.6
XS Rating Curve= 0 ,0
Exp/Cntr=0.3,0.1

Type RM Length L Ch R = 1 ,176049  ,233.9,233.9,233.9
XS GIS Cut Line= 2
2335730.76853142626729.1953436232336199.86847583626596.623620203
#Sta/Elev= 30
       0 3375.27     9.8 3372.59    14.8 3370.62    22.2 3366.75    30.6 3363.34
      43  3356.9    59.7 3349.61    73.6  3341.4    88.7 3335.31    97.1 3330.24
   114.6 3321.45   130.8 3311.91   155.3 3292.63   159.4 3290.01   161.9 3289.39
   184.4 3288.63   195.6 3289.31   202.1 3290.66   217.6 3290.23   231.2 3291.87
   273.4 3291.42   284.1 3290.16   296.6 3291.63   304.9 3293.95     309 3294.41
     334 3295.56   363.1 3296.17   392.2 3301.52   433.8 3306.23   487.5 3317.06
#Mann= 5 ,-1,0
       0      .1       0      50     .06       0     150      .1       0
   161.9    .045       0   195.6      .1       0
Bank Sta=161.9,195.6
XS Rating Curve= 0 ,0
Exp/Cntr(USF)=0,0
Exp/Cntr=0.3,0.1

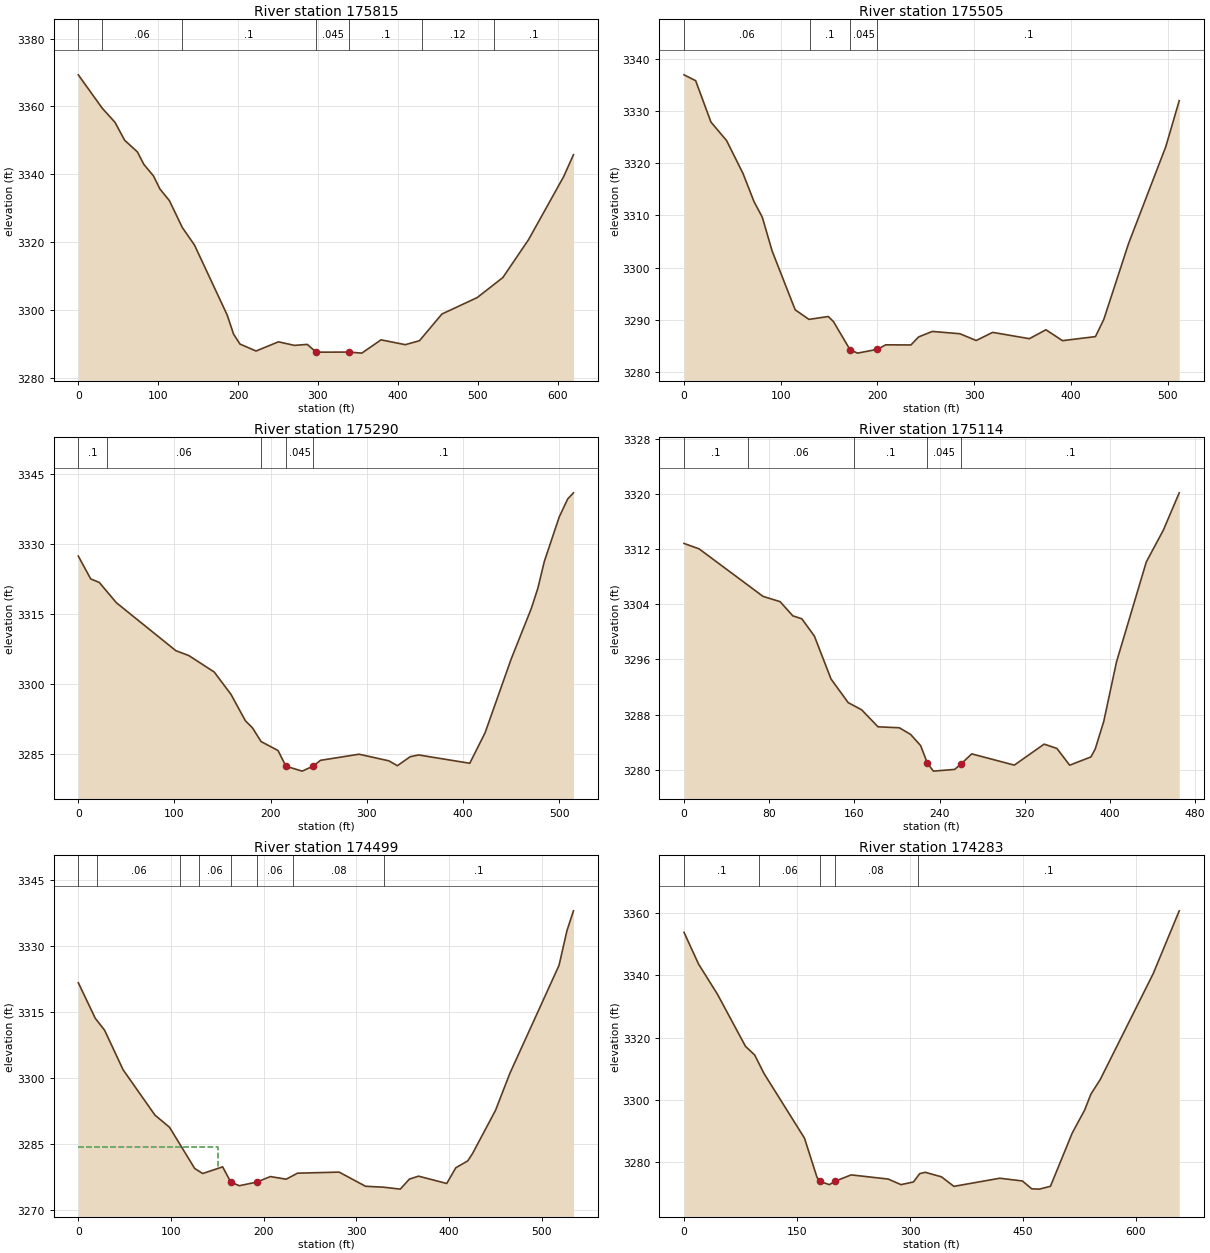
Type RM Length L Ch R = 1 ,175815  ,310.2,310.2,310.2
XS GIS Cut Line= 2
 2335750.3980524626872.0981669372336368.26971853626822.487204034
#Sta/Elev= 30
       0 3369.32    29.9 3359.51    45.9 3355.35      58 3350.06      74 3346.62
      82 3342.97    94.1 3339.55   102.1 3335.74   114.1 3332.25   130.2 3324.37
   145.5 3319.18   186.4 3298.59   194.4 3292.96   202.4 3290.04   222.5 3287.99
   250.6  3290.7   270.6 3289.65   286.7 3289.94   297.8 3287.65   338.9 3287.68
   354.9 3287.37     379 3291.28   409.3 3289.86   427.1 3291.02   455.2 3298.88
   499.4 3303.73   531.5 3309.63   563.6 3320.76   607.7 3339.38   619.9 3345.81
#Mann= 7 ,-1,0
       0      .1       0      30     .06       0     130      .1       0
   297.8    .045       0   338.9      .1       0     430     .12       0
     520      .1       0
Bank Sta=297.8,338.9
XS Rating Curve= 0 ,0
Exp/Cntr=0.3,0.1

Type RM Length L Ch R = 1 ,175505  ,215.6,215.6,215.6
XS GIS Cut Line= 3
2335783.07323492626960.2478468842336044.13755181627184.599994211
2336201.18405494627243.747378506
#Sta/Elev= 30
       0 3336.97      12 3335.85    27.8 3327.92      44 3324.36      61 3318.04
    72.4 3312.64    80.9 3309.68    91.1 3303.18   114.9 3291.92   129.1 3290.08
   149.1 3290.63   154.4 3289.68   171.6 3284.28   179.4 3283.61     200 3284.34
   208.5  3285.2   234.6 3285.18   242.5 3286.71   256.7 3287.77   285.1 3287.33
   302.1 3286.03   319.1 3287.59   357.1 3286.38   374.2 3288.09   391.3    3286
   425.4 3286.78     434 3290.07   459.6 3304.61   498.1 3323.19     512 3332.01
#Mann= 4 ,-1,0
       0     .06       0     130      .1       0   171.6    .045       0
     200      .1       0
Bank Sta=171.6,200
XS Rating Curve= 0 ,0
Exp/Cntr(USF)=0,0
Exp/Cntr=0.3,0.1

Type RM Length L Ch R = 1 ,175290  ,175.1,175.1,175.1
XS GIS Cut Line= 2
2335608.49864349627169.4205125052336073.60952014 627390.16662823
#Sta/Elev= 30
       0 3327.41    12.9 3322.53    21.8 3321.78    39.5 3317.45   101.5 3307.17
   114.8 3306.15   141.3 3302.62   158.7 3297.85   173.7  3292.2   181.2 3290.64
     190 3287.75   207.7 3285.82   215.8 3282.48   232.7 3281.42   244.2 3282.49
   251.8 3283.73   291.9 3285.04   322.9 3283.62   331.7 3282.58     345  3284.5
   353.8 3284.88     407  3283.1   422.9 3289.62     450 3305.38     471 3316.23
   477.8 3320.55   484.5 3326.27     500 3335.78   508.8 3339.64   514.8 3340.94
#Mann= 5 ,-1,0
       0      .1       0      30     .06       0     190      .1       0
   215.8    .045       0   244.2      .1       0
Bank Sta=215.8,244.2
XS Rating Curve= 0 ,0
Exp/Cntr=0.3,0.1

Type RM Length L Ch R = 1 ,175114  ,615.2,615.2,615.2
XS GIS Cut Line= 2
2335522.00891803627439.5456161722335987.02973249 627431.38735627
#Sta/Elev= 30
       0 3312.81    14.2 3312.02    74.2 3305.14    90.2 3304.38   102.2 3302.32
   110.6  3301.9   122.4  3299.4   138.1 3293.16   154.2 3289.75   166.8 3288.71
   182.2 3286.25   202.2 3286.11   212.8 3285.15   222.2 3283.53   228.6 3280.97
   234.2 3279.83   254.2 3280.08   260.4  3280.9   270.2 3282.33   310.2  3280.7
   338.2 3283.74   350.2 3283.12   362.2 3280.69   382.2 3281.89   386.2 3283.03
   394.2 3287.02   406.2 3295.66   434.2 3310.14   450.2 3314.74   465.1 3320.14
#Mann= 5 ,-1,0
       0      .1       0      60     .06       0     160      .1       0
   228.6    .045       0   260.4      .1       0
Bank Sta=228.6,260.4
XS Rating Curve= 0 ,0
Exp/Cntr(USF)=0,0
Exp/Cntr=0.3,0.1

Type RM Length L Ch R = 1 ,174499  ,215.8,215.8,215.8
XS GIS Cut Line= 4
2335936.41609815627982.215241508 2336016.9915046627775.740762487
2336037.13535621627669.985541525 2336110.1568183627478.618951213
#Sta/Elev= 30
       0 3321.65    18.3 3313.58    28.4 3310.86    48.3 3301.91    82.7 3291.61
    98.4 3288.86   125.6  3279.5   134.2 3278.37   155.7 3279.88   164.4 3276.45
   173.6  3275.6   192.4 3276.42   207.2 3277.68   224.2 3277.08   236.5 3278.45
   281.3 3278.69   309.8 3275.48   329.3 3275.27   347.3 3274.83   357.1  3277.1
     367 3277.77   397.4 3276.11   407.2 3279.68   420.1 3281.24   425.2 3282.89
     450 3292.69   465.5 3301.09   518.5 3325.57   527.1 3333.47   534.1 3337.95
#Mann= 8 ,-1,0
       0      .1       0      20     .06       0     110      .1       0
     130     .06       0   164.4    .045       0   192.4     .06       0
  231.64     .08       0   329.3      .1       0
#XS Ineff= 2 , 0
          151.01 3284.43
Permanent Ineff=
       F       F
Bank Sta=164.4,192.4
XS Rating Curve= 0 ,0
Exp/Cntr(USF)=0,0
Exp/Cntr=0.3,0.1

Type RM Length L Ch R = 1 ,174283  ,255.7,255.7,255.7
XS GIS Cut Line= 2
2336155.32091522628059.9018478112336321.35155316 627423.74952606
#Sta/Elev= 30
       0 3353.81    19.3 3343.63    44.2 3334.03    81.6 3317.24    93.8 3314.46
   106.2 3308.51   159.9 3287.78   176.4 3275.29     180 3273.91     193 3272.85
   200.2 3273.91   221.9 3275.98   271.1 3274.64   288.1 3272.85   304.6 3273.71
   312.9 3276.38   320.2 3276.81   341.8 3275.36   358.3  3272.3   419.3 3274.91
   449.3 3274.02   461.7  3271.5   471.7 3271.41   486.5 3272.31   515.4  3289.4
     532 3296.83   540.2 3301.89   552.6 3306.58   622.9 3340.54   657.5 3360.73
#Mann= 5 ,-1,0
       0      .1       0     100     .06       0     180    .045       0
   200.2     .08       0     310      .1       0
Bank Sta=180,200.2
XS Rating Curve= 0 ,0
Exp/Cntr=0.3,0.1

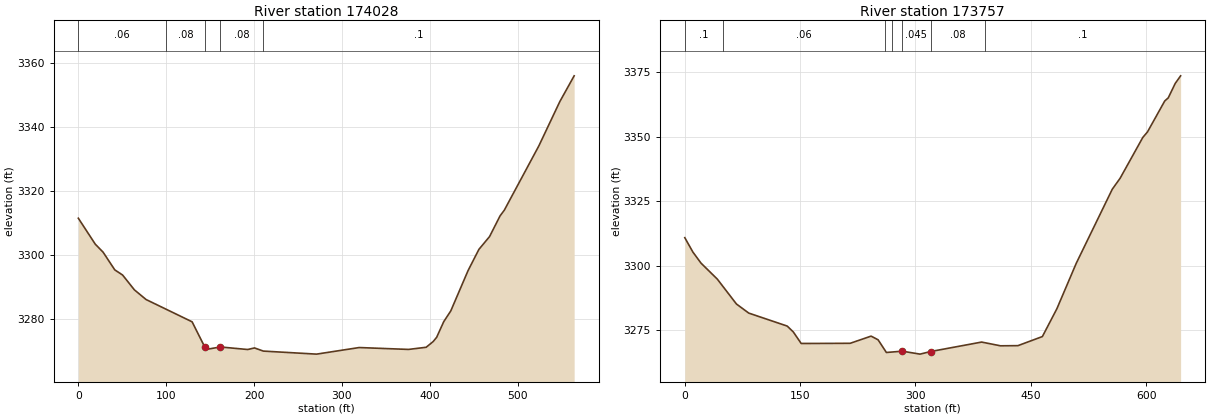
Type RM Length L Ch R = 1 ,174028  ,270.5,270.5,270.5
XS GIS Cut Line= 3
2336507.99788764627954.5174455412336412.31459248627758.114892326
2336387.13477797627413.151433474
#Sta/Elev= 30
       0 3311.51    19.3 3303.39    28.2 3300.89    41.5 3295.35    50.4 3293.74
    63.8 3289.11    77.1 3286.08   129.5 3279.11   143.9 3271.24   148.3  3270.6
   161.7 3271.24   192.8 3270.44   200.5 3270.94   210.6 3269.95   271.2    3269
   319.7 3271.06   375.8 3270.47   395.9 3271.14   403.9 3272.93   407.9 3274.27
   415.9 3279.13     424 3282.53   443.7 3295.17     456 3301.77   468.1 3305.77
   480.1 3312.26   484.9 3314.03   524.2 3334.13   548.1    3348   564.4 3356.05
#Mann= 5 ,-1,0
       0     .06       0     100     .08       0   143.9    .045       0
   161.7     .08       0     210      .1       0
Bank Sta=143.9,161.7
XS Rating Curve= 0 ,0
Exp/Cntr(USF)=0,0
Exp/Cntr=0.3,0.1

Type RM Length L Ch R = 1 ,173757  ,208,208,208
XS GIS Cut Line= 2
2336782.21667269627906.4032321062336475.68381508627338.983235982
#Sta/Elev= 30
       0 3310.82    10.5 3305.25    21.1 3300.94    42.3 3294.73    67.2 3285.06
    83.2 3281.54   133.2  3276.5   141.1 3274.23   151.4 3269.74   215.1 3269.81
   242.3  3272.6   251.4 3271.18   262.2 3266.25   282.8 3266.75     306 3265.61
   319.6 3266.61   386.1 3270.29   410.6 3268.84   433.3  3268.9   465.1 3272.43
     484 3283.26   509.2 3300.91     556 3329.63   566.2 3333.89   595.7 3349.73
   601.8 3351.88   624.2 3363.88   628.8  3365.1   637.9 3370.72   644.9 3373.66
#Mann= 7 ,-1,0
       0      .1       0      50     .06       0     260      .1       0
     270     .08       0   282.8    .045       0   319.6     .08       0
     390      .1       0
Bank Sta=282.8,319.6
XS Rating Curve= 0 ,0
Exp/Cntr=0.3,0.1