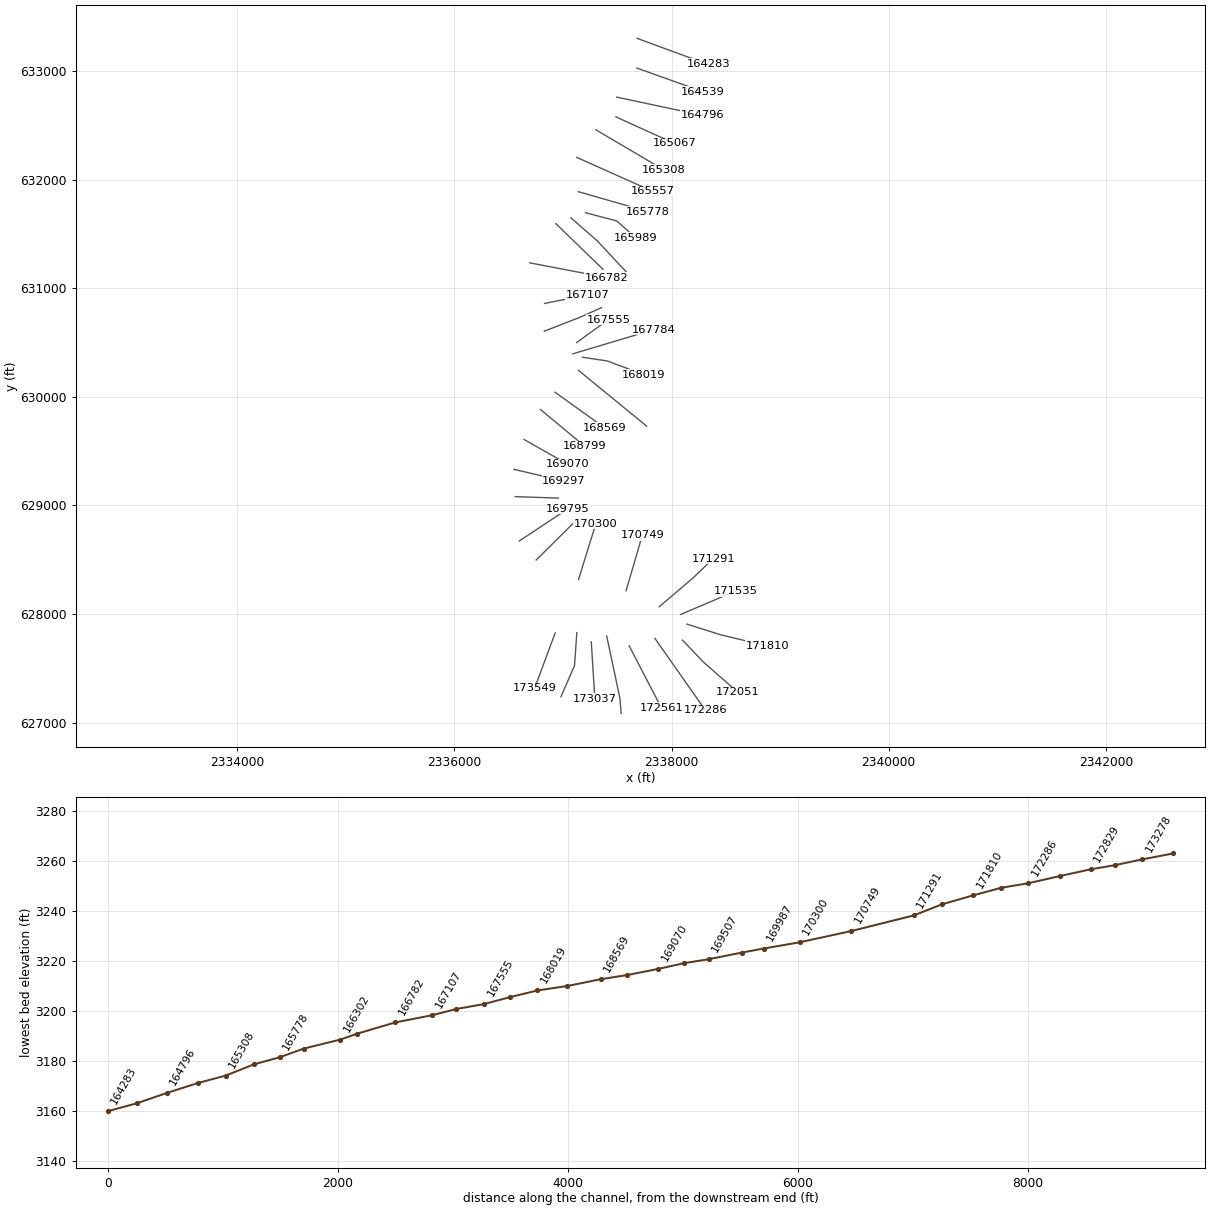
HEC-RAS study LAURELFK.prj: LAURELFK

--- LAURELFK.g01 (geometry) --- (continued)

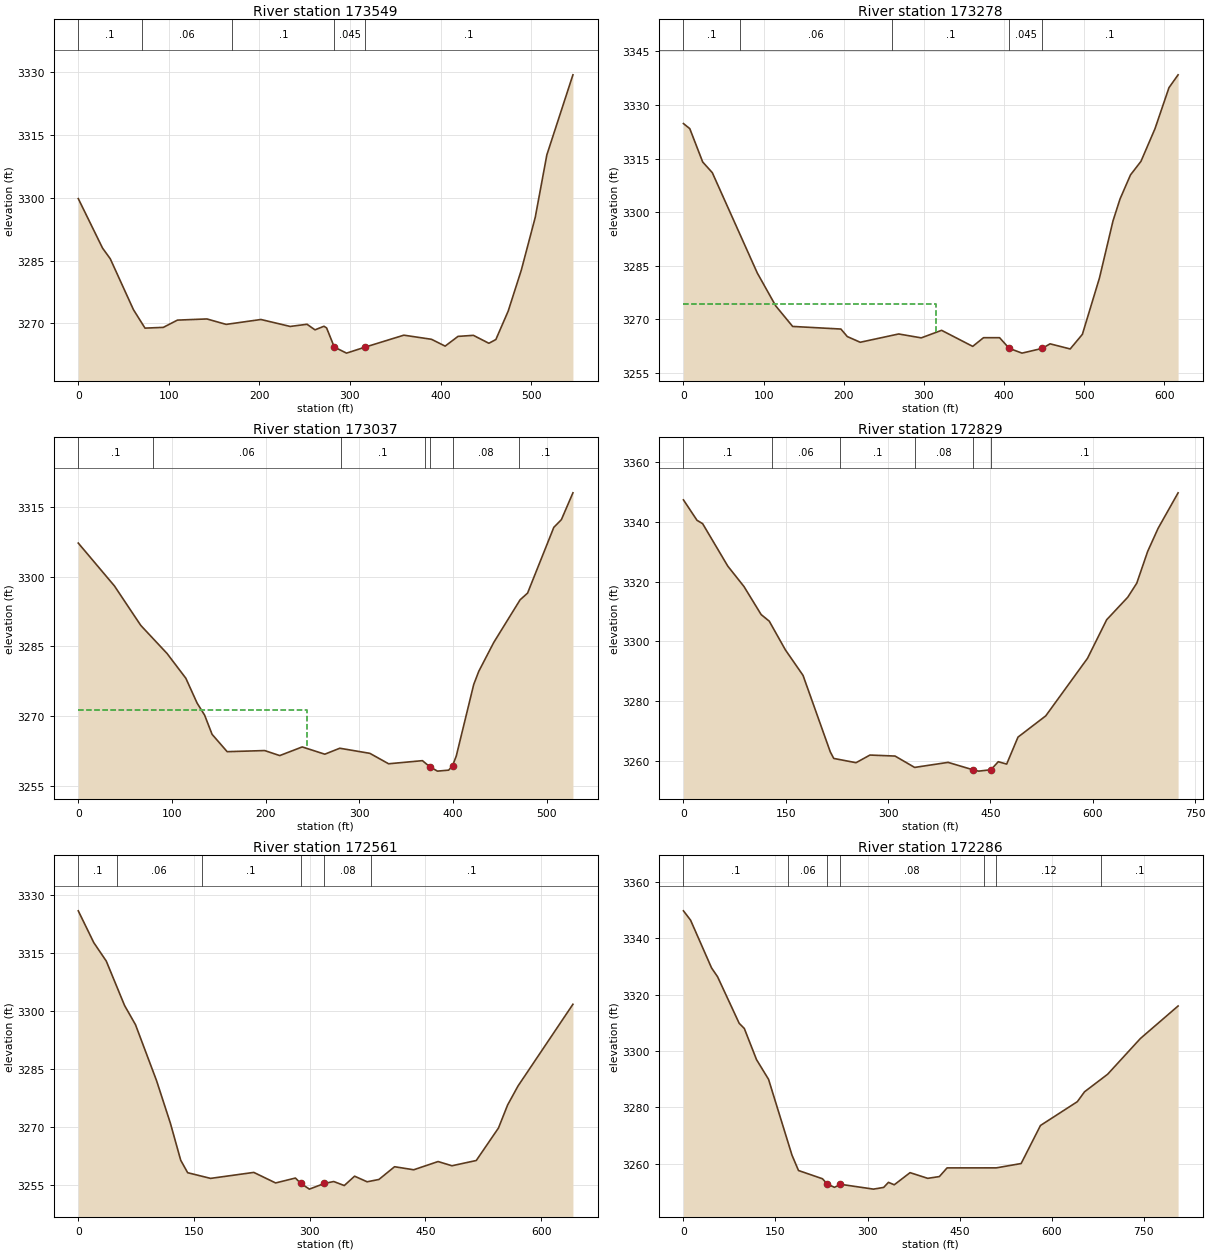
Type RM Length L Ch R = 1 ,173549  ,270.8,270.8,270.8
XS GIS Cut Line= 2
2336927.83436801627826.2686465612336737.84889053627314.133881164
#Sta/Elev= 30
       0 3299.76    26.8 3287.96    35.3 3285.43    60.9 3273.29    73.7 3268.88
    93.9 3269.06   109.5 3270.79     142 3271.07   163.3 3269.77   201.7 3270.94
     234 3269.28   252.6  3269.8   261.4 3268.47   271.3 3269.33   274.2 3268.93
   282.7 3264.36   296.2 3262.92   316.23264.316   359.5  3267.2     390 3266.22
   405.1 3264.59   419.3 3266.91   436.3 3267.16   453.4 3265.27   461.1 3266.16
   474.7 3272.93   489.2 3282.71   504.6  3295.3   517.4 3310.18   546.2 3329.27
#Mann= 5 ,-1,0
       0      .1       0      70     .06       0     170      .1       0
   282.7    .045       0   316.2      .1       0
Bank Sta=282.7,316.2
XS Rating Curve= 0 ,0
Exp/Cntr(USF)=0,0
Exp/Cntr=0.3,0.1

Type RM Length L Ch R = 1 ,173278  ,241,241,241
XS GIS Cut Line= 3
2337127.26206033 627829.081641942337105.62582789627523.596834534
2336981.42584118627238.772841175
#Sta/Elev= 30
       0 3324.78     7.9 3323.36      24 3314.03      36 3311.04    92.1 3282.97
   115.1 3273.76   136.2 3268.01   196.4 3267.28   204.4 3265.17   220.5 3263.58
   268.5  3265.9   296.6 3264.81     322 3266.92   360.8 3262.43   374.3 3264.86
   394.3 3264.86   406.4 3261.87   422.3 3260.54   447.4 3261.86   457.3 3263.14
   482.4 3261.71   497.6  3265.8   518.9 3281.56   535.8 3297.54   544.5 3303.64
   557.6 3310.41   570.7 3314.22   588.2 3323.36   605.6 3334.82     617 3338.42
#Mann= 5 ,-1,0
       0      .1       0      70     .06       0     260      .1       0
   406.4    .045       0   447.4      .1       0
#XS Ineff= 2 , 0
          314.77 3274.35
Permanent Ineff=
       F       F
Bank Sta=406.4,447.4
XS Rating Curve= 0 ,0
Exp/Cntr=0.3,0.1

Type RM Length L Ch R = 1 ,173037  ,208.7,208.7,208.7
XS GIS Cut Line= 2
2337260.37707201627743.7474186552337293.41802461627216.927785433
#Sta/Elev= 30
       0  3307.2    38.6 3297.99    66.7 3289.51    94.8 3283.46   114.8 3278.15
   126.8 3272.82   134.8 3270.24   142.8  3266.1   158.9 3262.37     199 3262.61
     215 3261.53     239 3263.39   263.1 3261.83   279.1 3263.11   311.2 3262.01
   331.2 3259.77   367.3 3260.44     375 3259.15   383.3 3258.19   395.3  3258.4
   399.4 3259.35   403.4 3261.43     422 3276.79   427.4 3279.63   443.4 3285.84
   471.5    3295   479.5 3296.45   507.5 3310.58   515.6 3312.24   527.9    3318
#Mann= 7 ,-1,0
       0      .1       0      80     .06       0     280      .1       0
     370     .08       0     375    .045       0   399.4     .08       0
     470      .1       0
#XS Ineff= 2 , 0
          243.62 3271.22
Permanent Ineff=
       F       F
Bank Sta=375,399.4
XS Rating Curve= 0 ,0
Exp/Cntr(USF)=0,0
Exp/Cntr=0.3,0.1

Type RM Length L Ch R = 1 ,172829  ,267.5,267.5,267.5
XS GIS Cut Line= 3
2337402.48732542627796.6366286572337524.30420531627223.468748199
     2337535.087      627084.789
#Sta/Elev= 30
       0 3347.31    19.9 3340.47    28.1 3339.36      65 3325.15    88.7 3318.33
   113.9 3308.94   125.8 3306.73   149.4 3297.14   175.3 3288.59   215.2 3263.03
   220.3 3260.81     253 3259.38   273.4 3261.94   310.2  3261.6   338.9  3257.8
   387.9 3259.49   424.7 3256.98   432.9 3256.56   450.7 3257.03   461.5 3259.71
   473.8 3258.91   490.4 3267.94   531.1 3275.05   592.3 3294.31   620.4 3307.21
   651.3 3314.74   664.5 3319.44   680.5 3330.08   695.9 3337.84   725.1 3349.67
#Mann= 6 ,-1,0
       0      .1       0     130     .06       0     230      .1       0
     340     .08       0   424.7    .045       0   450.7      .1       0
Bank Sta=424.7,450.7
XS Rating Curve= 0 ,0
Exp/Cntr=0.3,0.1

Type RM Length L Ch R = 1 ,172561  ,275,275,275
XS GIS Cut Line= 2
2337609.14268285627707.0352490932337904.67564783627137.996620874
#Sta/Elev= 30
       0 3325.91    20.1 3317.68    36.3  3312.9      60 3301.41    74.2 3296.42
   101.5 3281.93   119.3 3270.99   132.8 3261.34   141.8 3258.11   171.5 3256.64
   227.5 3258.19   255.8 3255.46   281.5 3256.73   288.4 3255.34   299.6 3253.86
     319 3255.33   331.1 3255.83   344.8 3254.79   358.2 3257.21   374.4 3255.76
   389.7 3256.36     410 3259.66   434.8 3258.87   466.4    3261   484.4 3259.91
   515.9 3261.27   544.7 3269.69   556.5 3275.63     570 3280.55   641.2 3301.72
#Mann= 6 ,-1,0
       0      .1       0      50     .06       0     160      .1       0
   288.4    .045       0     319     .08       0     380      .1       0
Bank Sta=288.4,319
XS Rating Curve= 0 ,0
Exp/Cntr(USF)=0,0
Exp/Cntr=0.3,0.1

Type RM Length L Ch R = 1 ,172286  ,234.8,234.8,234.8
XS GIS Cut Line= 2
 2337847.2244516627774.6912047492338310.09947704627114.788317649
#Sta/Elev= 30
       0 3349.78    11.6 3346.47    45.8 3329.51    55.6 3326.38    90.8 3309.86
    99.2 3308.01   119.1 3296.95   138.7 3289.95   176.9 3263.02   187.5 3257.59
   226.6 3254.66   234.13252.827   246.1 3251.62   255.9 3252.69   309.7 3250.98
   326.3 3251.59   334.1 3253.39   343.5 3252.52   369.3 3256.83   398.1 3254.81
   417.1 3255.44   429.6 3258.52     510 3258.53   550.3 3260.07   581.8 3273.57
   641.9 3282.03   653.6 3285.53   691.3 3291.77   744.5 3304.42   806.1    3316
#Mann= 7 ,-1,0
       0      .1       0     170     .06       0   234.1    .045       0
   255.9     .08       0     490      .1       0     510     .12       0
     680      .1       0
Bank Sta=234.1,255.9
XS Rating Curve= 0 ,0
Exp/Cntr=0.3,0.1

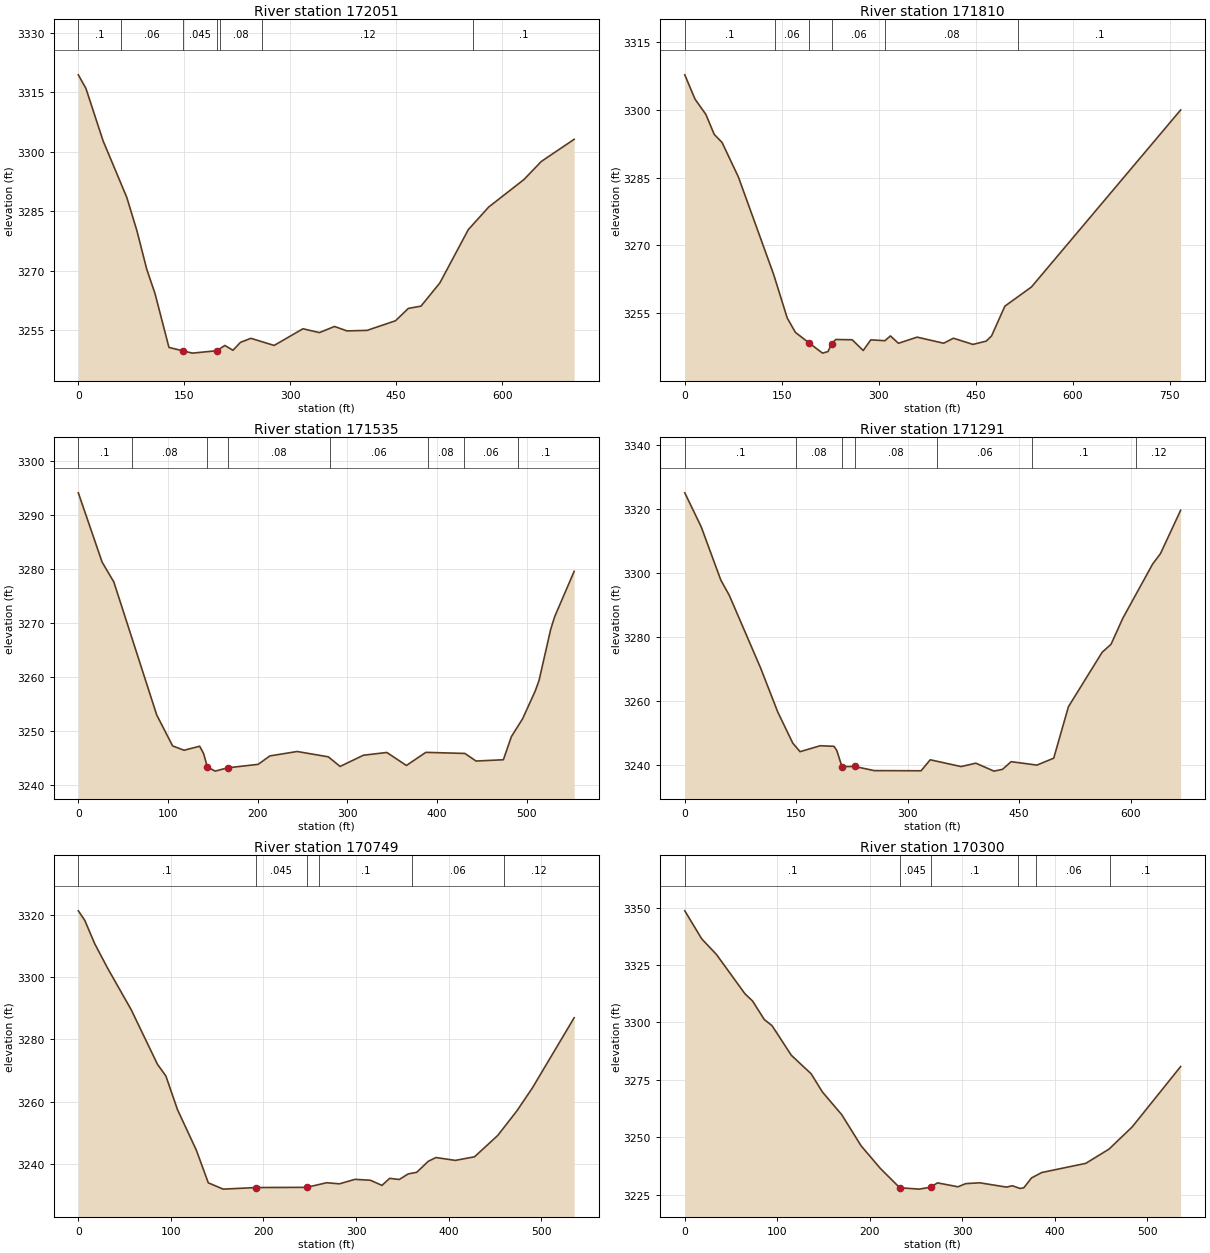
Type RM Length L Ch R = 1 ,172051  ,241.7,241.7,241.7
XS GIS Cut Line= 3
2338100.74955783627759.1910071382338293.48844804627557.274074545
2338611.04871475627278.261585869
#Sta/Elev= 30
       0 3319.44    10.8 3315.99      35  3302.8    68.7 3288.45    83.1 3279.98
    96.8 3270.39   108.5 3264.25   128.3 3250.62   148.1 3249.76   161.4 3249.18
   196.2 3249.79   207.4 3251.12   218.9  3249.9   229.5  3251.9   244.3 3252.92
   277.2 3251.12     318 3255.33   341.3 3254.36   362.6 3255.91   380.3 3254.79
   408.7 3254.92     449 3257.35   467.2 3260.47   485.1 3261.05   511.7 3266.88
     552 3280.34   580.9 3286.06   630.8    3293   655.4 3297.57   701.9 3303.16
#Mann= 7 ,-1,0
       0      .1       0      60     .06       0   148.1    .045       0
   196.2     .06       0     200     .08       0     260     .12       0
  559.14      .1       0
Bank Sta=148.1,196.2
XS Rating Curve= 0 ,0
Exp/Cntr(USF)=0,0
Exp/Cntr=0.3,0.1

Type RM Length L Ch R = 1 ,171810  ,274.4,274.4,274.4
XS GIS Cut Line= 3
2338141.14709837627907.245222531 2338451.1917987627808.940333874
2338880.43951688627705.890774763
#Sta/Elev= 30
       0 3307.77    15.8  3302.4    32.6    3299    45.5 3294.59    57.7 3292.78
    82.9 3285.15   137.5 3263.54   158.4 3253.94     171 3250.77     192 3248.45
     192 3248.44     213 3246.17   221.4 3246.51   227.1 3248.24   233.5 3249.19
   258.9 3249.12   275.9 3246.75   287.6 3249.11   309.5 3248.92   317.9 3249.98
   330.4 3248.35   359.2 3249.71   400.3 3248.36   415.4 3249.47   445.6  3248.1
   466.1 3248.83   474.4 3249.99   494.9 3256.56   536.1 3260.82   766.7 3299.99
#Mann= 6 ,-1,0
       0      .1       0     140     .06       0     192    .045       0
   227.1     .06       0     310     .08       0  515.26      .1       0
Bank Sta=192,227.1
XS Rating Curve= 0 ,0
Exp/Cntr=0.3,0.1

Type RM Length L Ch R = 1 ,171535  ,244.1,244.1,244.1
XS GIS Cut Line= 2
2338083.75246805627995.9861172982338592.21601649628212.587917717
#Sta/Elev= 30
       0 3294.15    26.5 3281.31    39.6 3277.61    87.4 3252.95   105.1 3247.22
   117.9 3246.41   135.2 3247.16   139.6 3245.82   143.9 3243.29   152.6 3242.54
   166.3 3243.15   200.5  3243.8   213.5 3245.36   243.9 3246.18   278.7 3245.19
   291.8 3243.41   317.8 3245.49   343.9    3246   365.7 3243.59   387.4 3246.02
   430.9 3245.82   443.3 3244.41   473.8 3244.65   482.7 3248.93   495.2 3252.24
   509.2 3257.36   513.5 3259.32   526.5  3268.8   530.9 3271.15   552.7 3279.59
#Mann= 8 ,-1,0
       0      .1       0      60     .08       0   143.9    .045       0
   166.3     .08       0     280     .06       0     390     .08       0
     430     .06       0     490      .1       0
Bank Sta=143.9,166.3
XS Rating Curve= 0 ,0
Exp/Cntr(USF)=0,0
Exp/Cntr=0.3,0.1

Type RM Length L Ch R = 1 ,171291  ,542.5,542.5,542.5
XS GIS Cut Line= 3
2337886.14113435628066.8679213962338196.28481507628331.304081847
2338383.77178233628511.081531928
#Sta/Elev= 30
       0 3324.99    22.1 3314.37    48.5 3297.75    59.8 3293.04   102.2 3270.22
   125.1 3256.58   145.4 3246.83   155.1 3244.19   182.4 3246.05   200.8 3245.86
   204.5 3244.59   211.5 3239.53   228.7 3239.58     255 3238.28     318 3238.23
   330.3 3241.66   371.9 3239.54   391.7  3240.6   416.1 3238.12   427.6 3238.68
   439.2 3241.07   473.9    3240   496.5 3242.16   516.3 3258.22   561.6 3275.19
   573.7 3277.73   589.4  3285.8   629.5 3302.71   640.2 3306.02   667.3 3319.53
#Mann= 7 ,-1,0
       0      .1       0     150     .08       0   211.5    .045       0
   228.7     .08       0     340     .06       0  467.57      .1       0
  607.57     .12       0
Bank Sta=211.5,228.7
XS Rating Curve= 0 ,0
Exp/Cntr=0.3,0.1

Type RM Length L Ch R = 1 ,170749  ,449.3,449.3,449.3
XS GIS Cut Line= 2
2337580.79574505628214.4235261952337731.31564025 628728.39390007
#Sta/Elev= 30
       0 3321.21       7 3318.13    17.8 3310.59      32 3302.61    57.1 3289.48
    85.5 3271.95    94.6 3268.19   107.1 3257.42   127.5 3244.38   140.4 3233.91
   156.5 3231.89   191.9  3232.4   246.6 3232.46   268.2 3233.94   282.1 3233.59
   298.8 3235.03   315.5 3234.74     328 3233.09   336.3 3235.35   346.7 3234.98
   356.3 3236.77   365.5 3237.28     378 3240.82   386.3 3242.03   407.2 3241.11
     428 3242.27   453.1 3249.13   473.9 3257.07   490.5 3264.38   535.6 3286.89
#Mann= 6 ,-1,0
       0      .1       0   191.9    .045       0   246.6     .08       0
     260      .1       0     360     .06       0     460     .12       0
Bank Sta=191.9,246.6
XS Rating Curve= 0 ,0
Exp/Cntr(USF)=0,0
Exp/Cntr=0.3,0.1

Type RM Length L Ch R = 1 ,170300  ,312.9,312.9,312.9
XS GIS Cut Line= 2
2337143.34264165628319.1302192882337301.99359903628831.084263532
#Sta/Elev= 30
       0 3348.61    18.3  3336.4    34.3 3329.56      65 3312.49    73.3 3309.31
    85.9 3301.28    94.3  3298.6   115.2 3285.68   136.6 3277.63   148.7 3269.74
   169.7 3259.79   190.6 3246.26   211.5 3236.36   232.4 3227.99   253.4 3227.39
     266 3228.24   273.1 3230.12   295.3 3228.41   303.7 3229.78   318.8 3230.15
   347.6 3228.28   354.2 3228.85   362.3 3227.69   366.5 3227.98   374.8 3232.26
   385.9 3234.63   433.5 3238.62   458.6 3244.82   483.7 3254.52     536 3280.78
#Mann= 6 ,-1,0
       0      .1       0   232.4    .045       0     266      .1       0
     360     .08       0     380     .06       0     460      .1       0
Bank Sta=232.4,266
XS Rating Curve= 0 ,0
Exp/Cntr=0.3,0.1

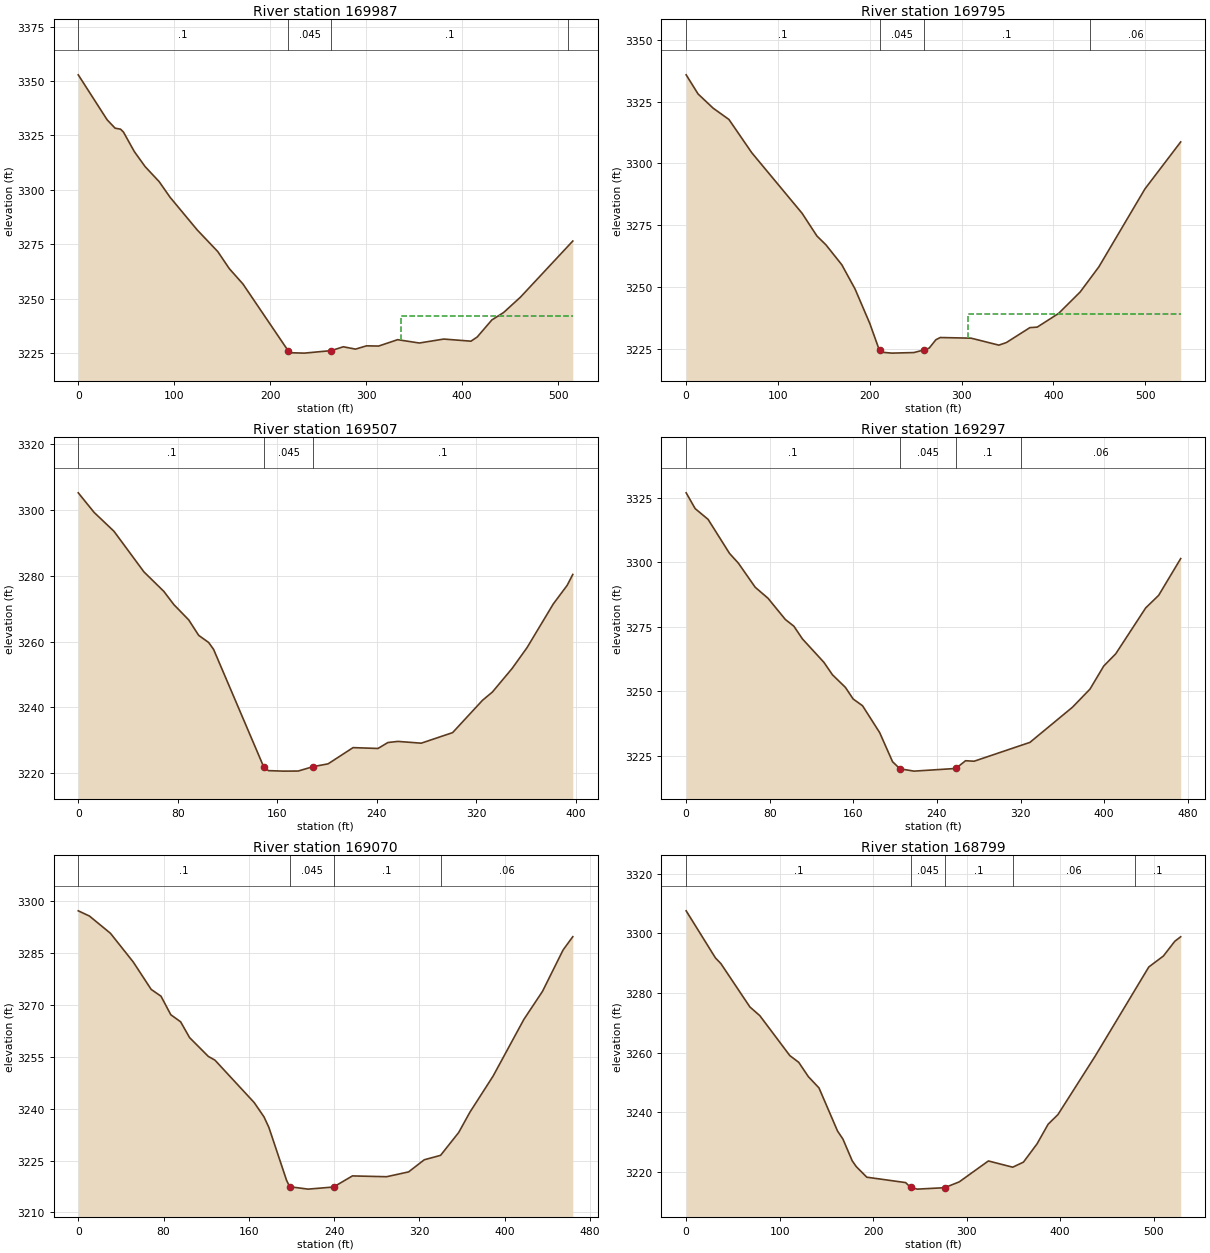
Type RM Length L Ch R = 1 ,169987  ,191.8,191.8,191.8
XS GIS Cut Line= 2
 2336752.8758415628497.8493490042337119.00208822628860.521574526
#Sta/Elev= 30
       0 3352.85    30.1 3332.16    38.4 3328.32    44.1 3327.86    47.1 3326.53
    58.4 3317.58    69.7 3310.63    84.3 3303.74    95.7 3296.53   124.1 3281.46
   145.4 3271.57   157.4 3263.73   171.6 3256.68   218.6 3226.06   222.5 3225.05
   235.5 3224.89   263.6 3226.04   276.2 3227.81   288.9 3226.73   300.3 3228.24
     313 3228.14   332.8 3231.07   355.4 3229.54   380.9 3231.36   409.2 3230.38
   415.7  3232.3     431 3240.16   443.1 3243.52   460.7  3250.6   515.3 3276.43
#Mann= 4 ,-1,0
       0      .1       0   218.6    .045       0   263.6      .1       0
     510     .06       0
#XS Ineff= 2 , 0
                           336.8         3241.98
Permanent Ineff=
       F       F
Bank Sta=218.6,263.6
XS Rating Curve= 0 ,0
Exp/Cntr(USF)=0,0
Exp/Cntr=0.3,0.1

Type RM Length L Ch R = 1 ,169795  ,287.4,287.4,287.4
XS GIS Cut Line= 2
 2336597.3704141628672.9297659642337046.45389692628970.675297892
#Sta/Elev= 30
       0 3335.79      13 3328.04    29.4 3322.31    46.6 3317.74    71.5 3304.28
   126.3 3279.81   142.5 3270.61   152.3 3267.04   169.6 3258.98     184  3249.2
   200.1 3235.24   209.7 3225.27   211.33224.592   214.5 3223.58   224.1 3223.26
   248.1 3223.49     259 3224.53   264.8  3225.3   272.1 3228.68   276.9 3229.57
   310.5 3229.31   340.7 3226.49   348.9 3227.54   374.5 3233.57   382.5 3233.78
   405.8 3239.32   429.3 3247.99   449.7 3258.17   499.9 3289.69   538.8 3308.66
#Mann= 4 ,-1,0
       0      .1       0   211.3    .045       0     259      .1       0
     440     .06       0
#XS Ineff= 2 , 0
                          306.95         3239.15
Permanent Ineff=
       F       F
Bank Sta=211.3,259
XS Rating Curve= 0 ,0
Exp/Cntr=0.3,0.1

Type RM Length L Ch R = 1 ,169507  ,210.5,210.5,210.5
XS GIS Cut Line= 2
2336559.45065456629081.5789310342336956.66309203629067.762846252
#Sta/Elev= 30
       0 3305.25    12.7 3299.31    28.7 3293.56    52.8  3281.2    68.8 3275.27
    76.8 3271.27    88.8  3266.6    96.8  3261.9   104.8 3259.74   108.8 3257.62
   148.8 3222.14   149.6 3221.92   152.8 3220.76   164.8 3220.61   176.8 3220.64
   188.8 3221.98   200.8 3222.82   220.9 3227.76   240.9  3227.5   248.9 3229.31
   256.9 3229.65   275.7 3229.11   300.9 3232.32   324.9 3242.14   332.9 3244.67
   348.7 3251.82   360.8 3258.21   381.8 3271.44     393 3277.12   397.5 3280.43
#Mann= 3 ,-1,0
       0      .1       0   149.6    .045       0   188.8      .1       0
Bank Sta=149.6,188.8
XS Rating Curve= 0 ,0
Exp/Cntr(USF)=0,0
Exp/Cntr=0.3,0.1

Type RM Length L Ch R = 1 ,169297  ,227.4,227.4,227.4
XS GIS Cut Line= 2
2336547.76433063629332.6494822622337008.73416369629225.486408068
#Sta/Elev= 30
       0  3326.9     8.6 3320.79      21 3316.61    41.5 3303.42    49.9 3299.69
    66.1  3290.3    78.4 3286.02    94.9 3277.83   103.1 3275.21   111.3 3270.28
   131.8 3261.24     140  3256.4   152.4 3251.52   159.8 3247.02   168.8  3244.4
   185.2 3233.99   197.5 3222.73   204.6 3219.96   218.1 3219.06   258.1 3220.09
   267.4 3223.09   275.6  3222.9     329  3230.2   369.8 3243.85   386.5 3250.85
   399.7 3259.81   411.1  3264.5   439.8  3282.3   452.2 3287.17   473.3 3301.42
#Mann= 4 ,-1,0
       0      .1       0   204.6    .045       0   258.1      .1       0
     320     .06       0
Bank Sta=204.6,258.1
XS Rating Curve= 0 ,0
Exp/Cntr=0.3,0.1

Type RM Length L Ch R = 1 ,169070  ,270.8,270.8,270.8
XS GIS Cut Line= 2
2336640.67846662629608.0585952912337044.05909515629379.174081352
#Sta/Elev= 30
       0 3297.23    10.5 3295.72    30.2 3290.73    51.6 3282.42    68.4  3274.5
    77.6 3272.54    86.8 3267.18      96 3265.14   104.4 3260.57     122 3255.12
   128.2 3254.05     165 3241.78   174.2 3237.64   178.8 3234.58   195.4 3219.27
   198.3 3217.44   215.6 3216.75   239.4 3217.36   257.1 3220.57   289.2 3220.34
   309.8 3221.73   324.5 3225.24   339.8 3226.52   356.8 3233.13   367.3 3238.99
   389.1 3249.46   417.9 3265.82   435.4 3273.95   454.7 3285.91   463.8 3289.75
#Mann= 4 ,-1,0
       0      .1       0   198.3    .045       0   239.4      .1       0
     340     .06       0
Bank Sta=198.3,239.4
XS Rating Curve= 0 ,0
Exp/Cntr(USF)=0,0
Exp/Cntr=0.3,0.1

Type RM Length L Ch R = 1 ,168799  ,230.2,230.2,230.2
XS GIS Cut Line= 2
2336791.57946534629884.6907757962337198.38398307629546.522054024
#Sta/Elev= 30
       0 3307.53    31.3 3291.76    37.2 3289.82    68.2 3275.31    78.8  3272.4
   110.9 3259.02   120.4 3256.77   130.7 3251.98   142.1 3248.18   161.9 3233.76
   167.7 3231.05   177.6 3223.79   181.9 3221.85   193.2 3218.28   234.8 3216.47
     240 3214.87   247.2 3214.28   276.5 3214.76   292.1 3216.71   323.3 3223.72
   349.3 3221.63   360.8 3223.33   375.3 3229.43   387.2 3236.03   397.7 3239.26
   437.5 3258.84   494.9 3288.72   510.5 3292.39   522.7 3297.33     529 3298.84
#Mann= 5 ,-1,0
       0      .1       0     240    .045       0   276.5      .1       0
     350     .06       0     480      .1       0
Bank Sta=240,276.5
XS Rating Curve= 0 ,0
Exp/Cntr=0.3,0.1

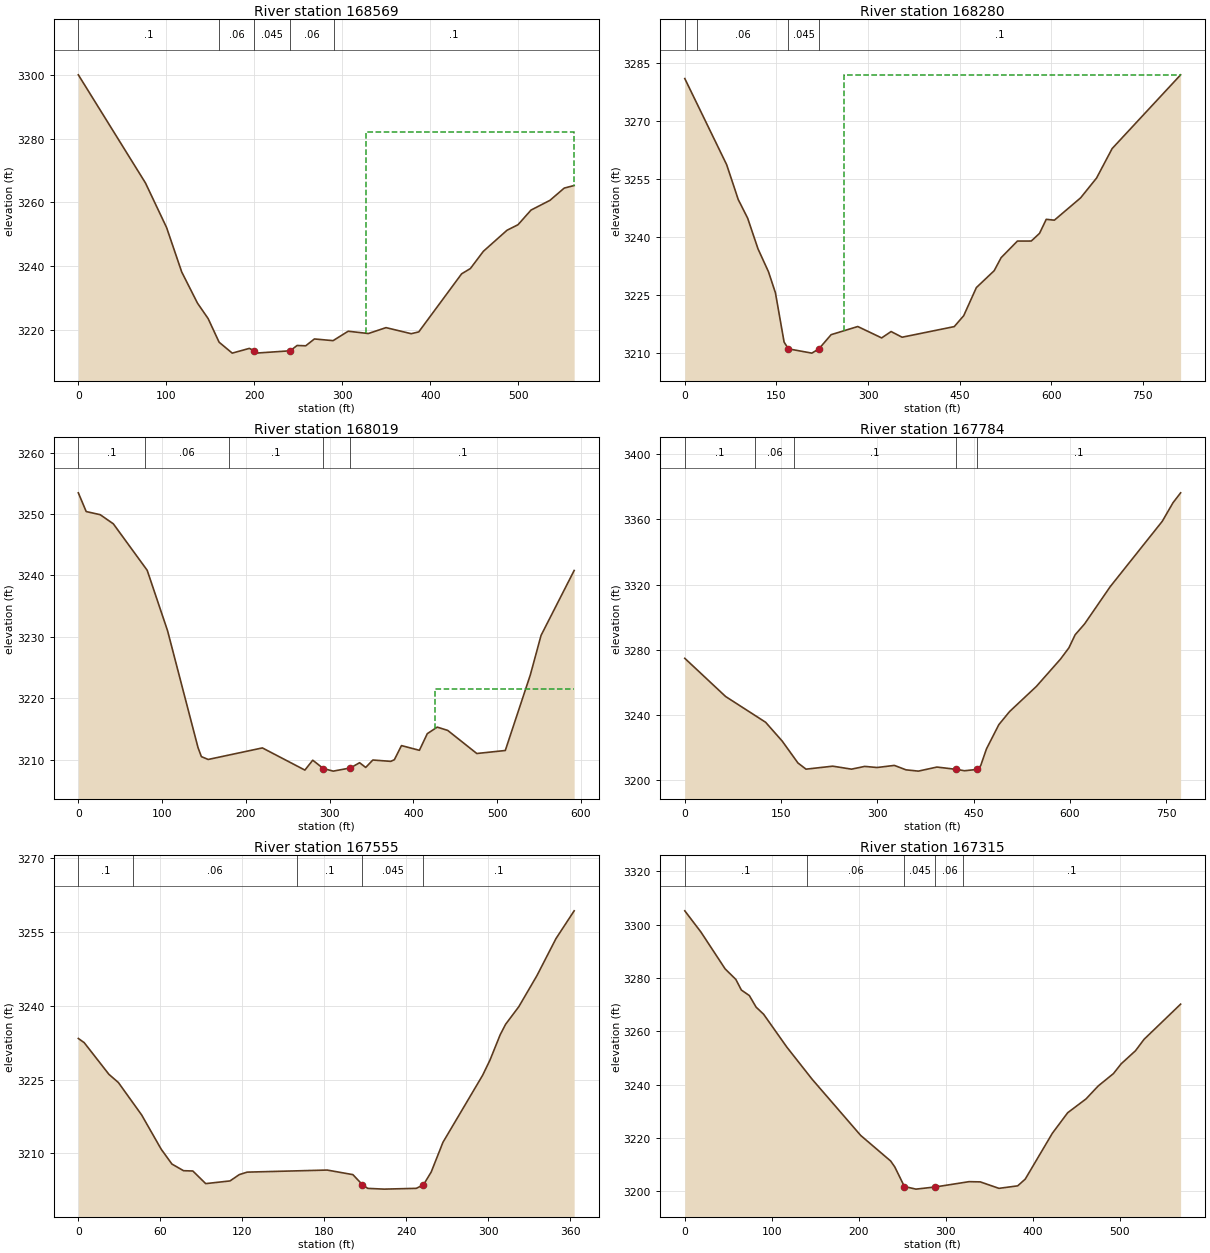
Type RM Length L Ch R = 1 ,168569  ,288.2,288.2,288.2
XS GIS Cut Line= 2
2336926.21756322630043.165790106 2337383.9865911629714.569210688
#Sta/Elev= 30
       0 3300.04    76.3 3266.07   100.3 3252.07   117.5 3238.11   135.4 3228.33
   147.5 3223.48     160 3216.05   174.9 3212.62   194.4 3214.11   199.4  3213.4
   204.3 3212.67   240.7 3213.35   248.6 3215.02   258.4 3214.92   268.3 3217.07
   289.5 3216.54   306.7  3219.5   329.6 3218.78   349.7 3220.63   378.3 3218.72
   386.9 3219.29   435.6 3237.53   445.6  3239.2   460.3  3244.6   487.2 3251.22
   499.7 3252.96   514.5 3257.56     536 3260.61   552.2 3264.46   563.5 3265.27
#Mann= 5 ,-1,0
       0      .1       0     160     .06       0   199.4    .045       0
   240.7     .06       0     290      .1       0
#XS Ineff= 1 ,-1
 326.656 563.496 3281.99
Permanent Ineff=
       F
Bank Sta=199.4,240.7
XS Rating Curve= 0 ,0
Exp/Cntr(USF)=0,0
Exp/Cntr=0.3,0.1

Type RM Length L Ch R = 1 ,168280  ,261.5,261.5,261.5
XS GIS Cut Line= 2
 2337142.8404517630244.6189833222337770.89957346629730.218285545
#Sta/Elev= 30
       0 3281.02    68.6  3258.7    87.5  3249.7   102.9 3244.87   119.9 3236.91
     137    3231   148.4 3225.54   162.6 3212.77   169.6 3211.03     208 3209.92
   219.4    3211   239.6  3214.7   283.2 3216.81   322.3 3213.86   337.8 3215.51
   355.8 3214.04   441.2 3216.79   456.7 3219.63   477.4  3226.9   506.5 3231.26
   517.9 3234.64   544.6 3238.94   567.3 3238.95   580.8 3240.94   591.8 3244.57
   605.1 3244.35     648 3250.12   674.2 3255.27   699.7  3262.9   811.8 3281.99
#Mann= 4 ,-1,0
       0      .1       0      20     .06       0   169.6    .045       0
   219.4      .1       0
#XS Ineff= 2 , 0
                        260.9106         3281.99
Permanent Ineff=
       F       F
Bank Sta=169.6,219.4
XS Rating Curve= 0 ,0
Exp/Cntr=0.3,0.1

Type RM Length L Ch R = 1 ,168019  ,235.4,235.4,235.4
XS GIS Cut Line= 3
2337178.89027668630365.5477188422337407.40628477 630331.13281146
 2337745.2044839630204.522065634
#Sta/Elev= 30
       0 3253.46     9.4 3250.41    26.1  3249.9    41.8 3248.41    82.2 3240.84
   106.5    3231   142.9 3211.94   146.9 3210.49     155 3210.03   219.7 3211.91
   270.4  3208.3   279.8 3209.91   292.43208.556   304.2 3208.13   324.83208.652
   335.7  3209.5     343 3208.73   351.5 3209.94   372.9 3209.72   377.2 3209.99
   385.7 3212.29   407.1 3211.52   416.5 3214.23   428.4  3215.3   440.9 3214.76
   475.6    3211   509.6 3211.49   539.5 3223.81   552.3 3230.24   591.8 3240.81
#Mann= 5 ,-1,0
       0      .1       0      80     .06       0     180      .1       0
   292.4    .045       0   324.8      .1       0
#XS Ineff= 2 , 0
                          425.84         3221.53
Permanent Ineff=
       F       F
Bank Sta=292.4,324.8
XS Rating Curve= 0 ,0
Exp/Cntr(USF)=0,0
Exp/Cntr=0.3,0.1

Type RM Length L Ch R = 1 ,167784  ,228.4,228.4,228.4
XS GIS Cut Line= 2
2337091.22753162630397.1387345382337831.58038847630618.403281687
#Sta/Elev= 30
       0 3274.74    63.6  3251.3   125.9  3235.5   151.9 3223.88   176.3 3210.51
   188.9  3206.7   230.6 3208.53   259.8  3206.7   280.4 3208.39   299.7 3207.71
   326.6    3209   344.7 3206.29     364 3205.49   392.9 3207.99   422.6 3206.59
     436 3205.72     456 3206.56   461.1 3208.83   470.1 3219.12   489.4 3234.02
   506.1 3242.04   547.9 3257.49   585.5 3274.27   598.6 3281.18   608.3 3289.19
     623 3295.84   662.9 3318.69   744.1 3358.86   760.8 3370.23   772.7 3376.33
#Mann= 5 ,-1,0
       0      .1       0     110     .06       0     170      .1       0
   422.6    .045       0     456      .1       0
Bank Sta=422.6,456
XS Rating Curve= 0 ,0
Exp/Cntr=0.3,0.1

Type RM Length L Ch R = 1 ,167555  ,240.4,240.4,240.4
XS GIS Cut Line= 2
2337124.72257914630500.0087914482337418.41993563 630712.93937491
#Sta/Elev= 30
       0 3233.35     4.3  3232.5    22.4 3226.05    29.3 3224.39    46.3  3217.8
    60.6 3210.83    68.5 3207.79      77 3206.44    83.8 3206.38    93.2 3203.81
     111 3204.36   117.8 3205.65   123.6 3206.15   182.1 3206.57   200.9 3205.64
   207.9 3203.58   211.8 3202.84   223.8 3202.69   247.3 3202.85   252.5 3203.56
   258.2 3206.17   266.8 3212.22   295.8 3225.85   301.2 3228.95   308.7 3234.12
   312.6 3236.22   322.3 3239.82   335.6 3246.16   349.5 3253.68   362.8 3259.33
#Mann= 5 ,-1,0
       0      .1       0      40     .06       0     160      .1       0
   207.9    .045       0   252.5      .1       0
Bank Sta=207.9,252.5
XS Rating Curve= 0 ,0
Exp/Cntr(USF)=0,0
Exp/Cntr=0.3,0.1

Type RM Length L Ch R = 1 ,167315  ,208.2,208.2,208.2
XS GIS Cut Line= 3
2336827.74985893630605.5712883952337161.43272898630735.559084781
2337354.58108409630822.506841557
#Sta/Elev= 30
       0 3305.21    18.6 3297.22    46.4  3283.4    58.7 3279.45      65 3275.48
    74.2 3273.39      82 3269.04    90.6 3266.38   117.4 3253.99   146.4 3241.96
   202.2 3220.87   236.6 3211.28   241.4 3209.03   252.4  3201.7   265.7 3200.72
   288.1 3201.54   326.7 3203.52   339.6 3203.44   361.1 3201.01   382.6 3201.95
   391.3 3204.48   422.5 3221.71   440.1  3229.4   461.2  3234.6   475.2 3239.46
   492.7  3244.1   501.5 3247.75     518 3252.67   527.8 3256.94   569.9 3270.17
#Mann= 5 ,-1,0
       0      .1       0     140     .06       0   252.4    .045       0
   288.1     .06       0     320      .1       0
Bank Sta=252.4,288.1
XS Rating Curve= 0 ,0
Exp/Cntr=0.3,0.1

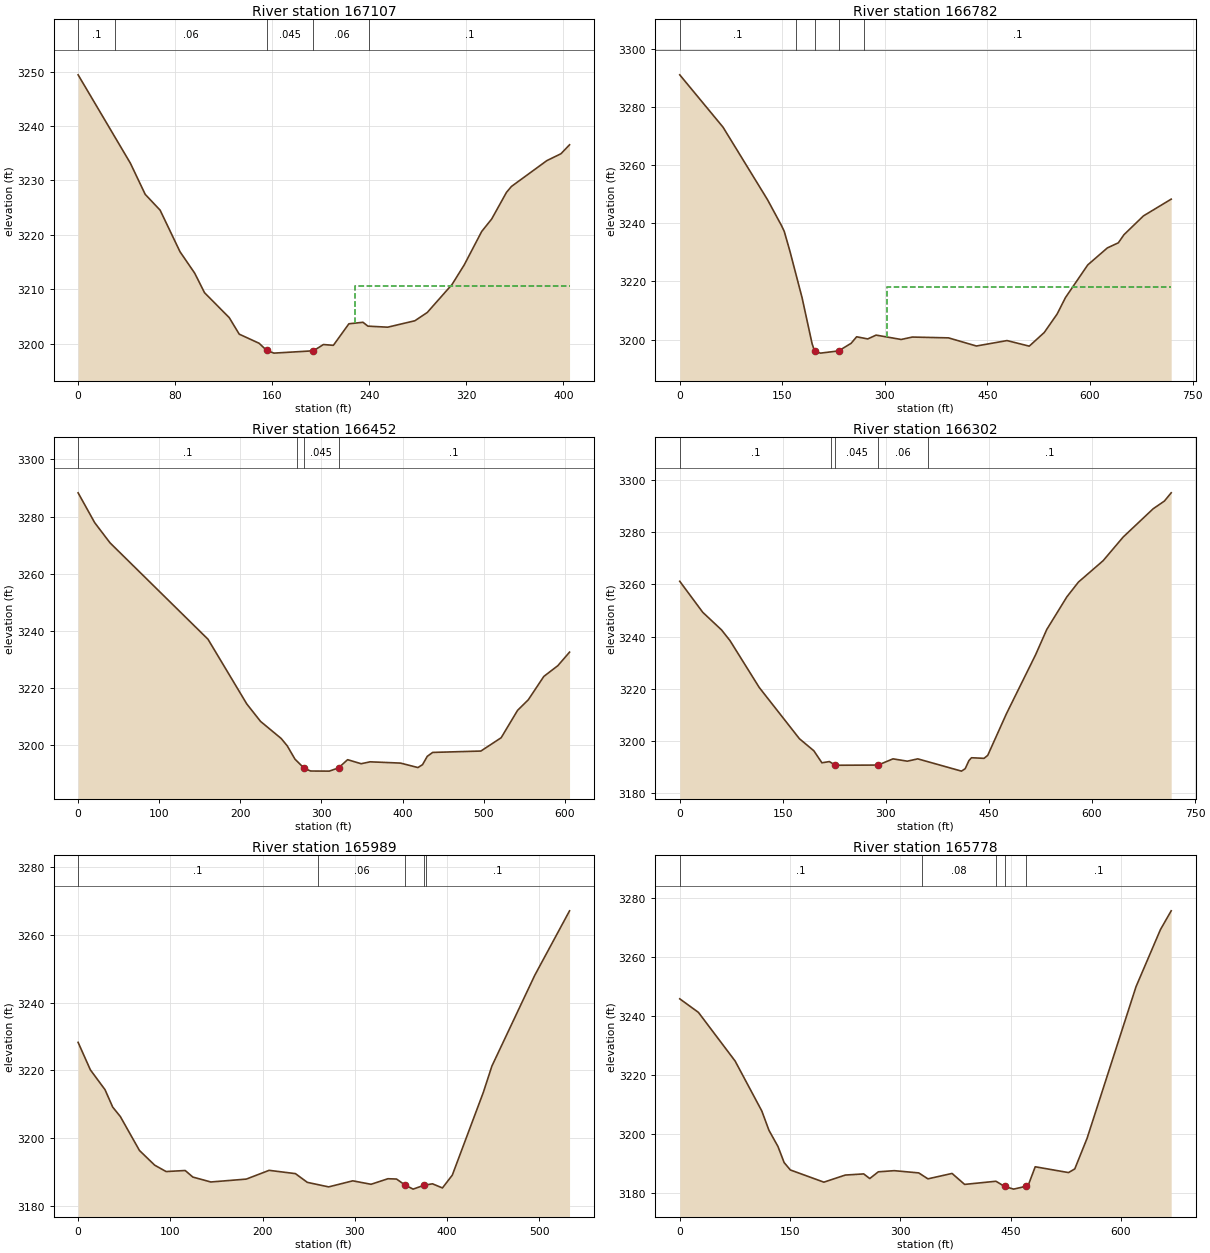
Type RM Length L Ch R = 1 ,167107  ,324.6,324.6,324.6
XS GIS Cut Line= 2
2336829.90596088630860.8303834982337227.11839836630940.272870993
#Sta/Elev= 30
       0 3249.42    43.1 3233.17    55.3 3227.45    67.6 3224.54      84  3216.9
    96.1 3212.96   104.2 3209.37   124.6 3204.78   132.8 3201.75   149.2 3200.07
   155.4 3198.77   161.4 3198.26     194 3198.69   202.2 3199.84   210.4 3199.69
   223.2 3203.65   234.8 3203.93   238.9 3203.22   255.2 3203.03   277.6 3204.21
   287.8 3205.73   308.3  3210.9   318.4 3214.53   332.7 3220.63   340.9 3222.91
   353.1 3227.81   357.2  3228.9   386.4 3233.65     398 3234.91   405.1 3236.56
#Mann= 5 ,-1,0
       0      .1       0      30     .06       0   155.4    .045       0
     194     .06       0     240      .1       0
#XS Ineff= 2 , 0
                          228.19         3210.66
Permanent Ineff=
       F       F
Bank Sta=155.4,194
XS Rating Curve= 0 ,0
Exp/Cntr(USF)=0,0
Exp/Cntr=0.3,0.1

Type RM Length L Ch R = 1 ,166782  ,329.7,329.7,329.7
XS GIS Cut Line= 2
2336694.03950243631234.7645826582337400.02455316631099.792382982
#Sta/Elev= 30
       0 3291.12    63.3  3273.1   128.4 3248.13   148.8 3239.24   152.9  3237.2
     161 3230.53   178.9 3214.42   193.6 3198.55   197.13196.087   205.8 3195.33
   232.3 3196.09   250.6  3198.7   258.7 3200.95     275 3200.22   287.2 3201.53
   323.9 3200.03   340.2 3200.86   393.1 3200.58   433.9 3197.78   478.7 3199.65
   511.2 3197.73   533.1 3202.42     552  3208.8   564.2 3214.47   596.8  3225.7
   625.4 3231.54   641.5  3233.3   649.7 3236.08   678.2 3242.56   718.8 3248.33
#Mann= 5 ,-1,0
       0      .1       0     170     .06       0   197.1    .045       0
   232.3     .06       0     270      .1       0
#XS Ineff= 2 , 0
                          303.36          3218.1
Permanent Ineff=
       F       F
Bank Sta=197.1,232.3
XS Rating Curve= 0 ,0
Exp/Cntr=0.3,0.1

Type RM Length L Ch R = 1 ,166452  ,150.4,150.4,150.4
XS GIS Cut Line= 2
2336933.52659675631596.5368981272337368.73326737631175.146312283
#Sta/Elev= 30
       0 3288.29    20.4 3277.86    39.3 3270.79   160.1 3237.03   207.9 3214.38
   224.9 3208.26   250.4 3202.26   257.8  3199.7   267.3 3195.06   278.6 3191.87
   286.6 3190.89   309.6 3190.85   321.1 3191.99   321.1    3192   321.1 3192.01
   332.2 3194.86   348.9 3193.44     360 3194.11   397.5 3193.66   418.9  3192.1
   424.6 3193.12   430.4 3196.03   437.1  3197.4   496.5 3197.88   521.5 3202.54
   541.7 3212.12   554.9 3215.82   574.1 3224.01   591.4 3227.78   605.8 3232.51
#Mann= 4 ,-1,0
       0      .1       0     270     .06       0   278.6    .045       0
   321.1      .1       0
Bank Sta=278.6,321.1
XS Rating Curve= 0 ,0
Exp/Cntr(USF)=0,0
Exp/Cntr=0.3,0.1

Type RM Length L Ch R = 1 ,166302  ,313,313,313
XS GIS Cut Line= 3
2337072.92340645631649.2372242042337315.40766613631437.596315325
2337583.70713146631149.996055646
#Sta/Elev= 30
       0 3261.16    33.5 3249.27    60.9 3242.51    73.1 3238.45   115.7 3220.48
   174.2 3200.85   195.1 3196.26   206.9 3191.64   217.8 3192.11   226.3  3190.7
   288.7 3190.77   310.3 3193.15   331.2 3192.26   346.4 3193.15     410 3188.45
   415.4 3189.38   420.9 3192.52   424.6 3193.57   442.8 3193.35   448.2 3194.48
   475.4 3210.42     518 3233.09   534.1 3242.69   563.4 3255.21   580.2 3260.85
   616.2 3269.06   645.3  3278.1   688.9 3288.92   705.3 3291.88   715.2 3295.04
#Mann= 5 ,-1,0
       0      .1       0     220     .06       0   226.3    .045       0
   288.7     .06       0  361.85      .1       0
Bank Sta=226.3,288.7
XS Rating Curve= 0 ,0
Exp/Cntr=0.3,0.1

Type RM Length L Ch R = 1 ,165989  ,211.4,211.4,211.4
XS GIS Cut Line= 3
2337207.85489413631696.5616605822337495.43355571631621.097756482
2337670.83614362631464.051253353
#Sta/Elev= 30
       0 3228.25    13.3 3220.13    29.2 3214.26    37.5 3209.13    45.8 3206.33
    66.5 3196.32      83 3191.98    95.4 3190.09   116.1  3190.4   124.4 3188.46
   143.9 3187.01   182.3 3187.86   207.1 3190.45   235.6 3189.48   248.5  3186.9
   271.6 3185.56   297.8 3187.35   317.6 3186.33   335.9 3187.97   345.2 3187.88
   354.4 3186.12   363.2  3184.9   375.1 3186.05   384.2 3186.47     395 3185.25
   405.7 3189.04   439.4 3213.54   448.6 3221.24   495.1 3248.07   532.8  3267.1
#Mann= 5 ,-1,0
       0      .1       0     260     .06       0   354.4    .045       0
   375.1     .06       0  377.32      .1       0
Bank Sta=354.4,375.1
XS Rating Curve= 0 ,0
Exp/Cntr(USF)=0,0
Exp/Cntr=0.3,0.1

Type RM Length L Ch R = 1 ,165778  ,221,221,221
XS GIS Cut Line= 2
2337139.80838081631890.8823327032337782.11990616631706.499952133
#Sta/Elev= 30
       0 3245.95    25.4 3241.35    75.3 3224.85   111.6 3207.91   121.3 3201.36
   133.6 3195.86   141.9 3190.44   150.4 3187.91     196 3183.77   225.1 3186.18
   250.1 3186.57   258.4    3185     270 3187.28   291.7 3187.67     325 3186.91
   337.5  3184.9   370.3 3186.73   387.4 3183.01     430 3184.08   441.7 3182.33
     454 3181.41   470.5 3182.35   474.8  3183.3   483.4 3188.99   528.7 3187.02
   537.2 3188.27   553.9 3198.63   620.5 3250.08   653.7 3269.43   668.3 3275.79
#Mann= 5 ,-1,0
       0      .1       0     330     .08       0     430      .1       0
   441.7    .045       0   470.5      .1       0
Bank Sta=441.7,470.5
XS Rating Curve= 0 ,0
Exp/Cntr=0.3,0.1

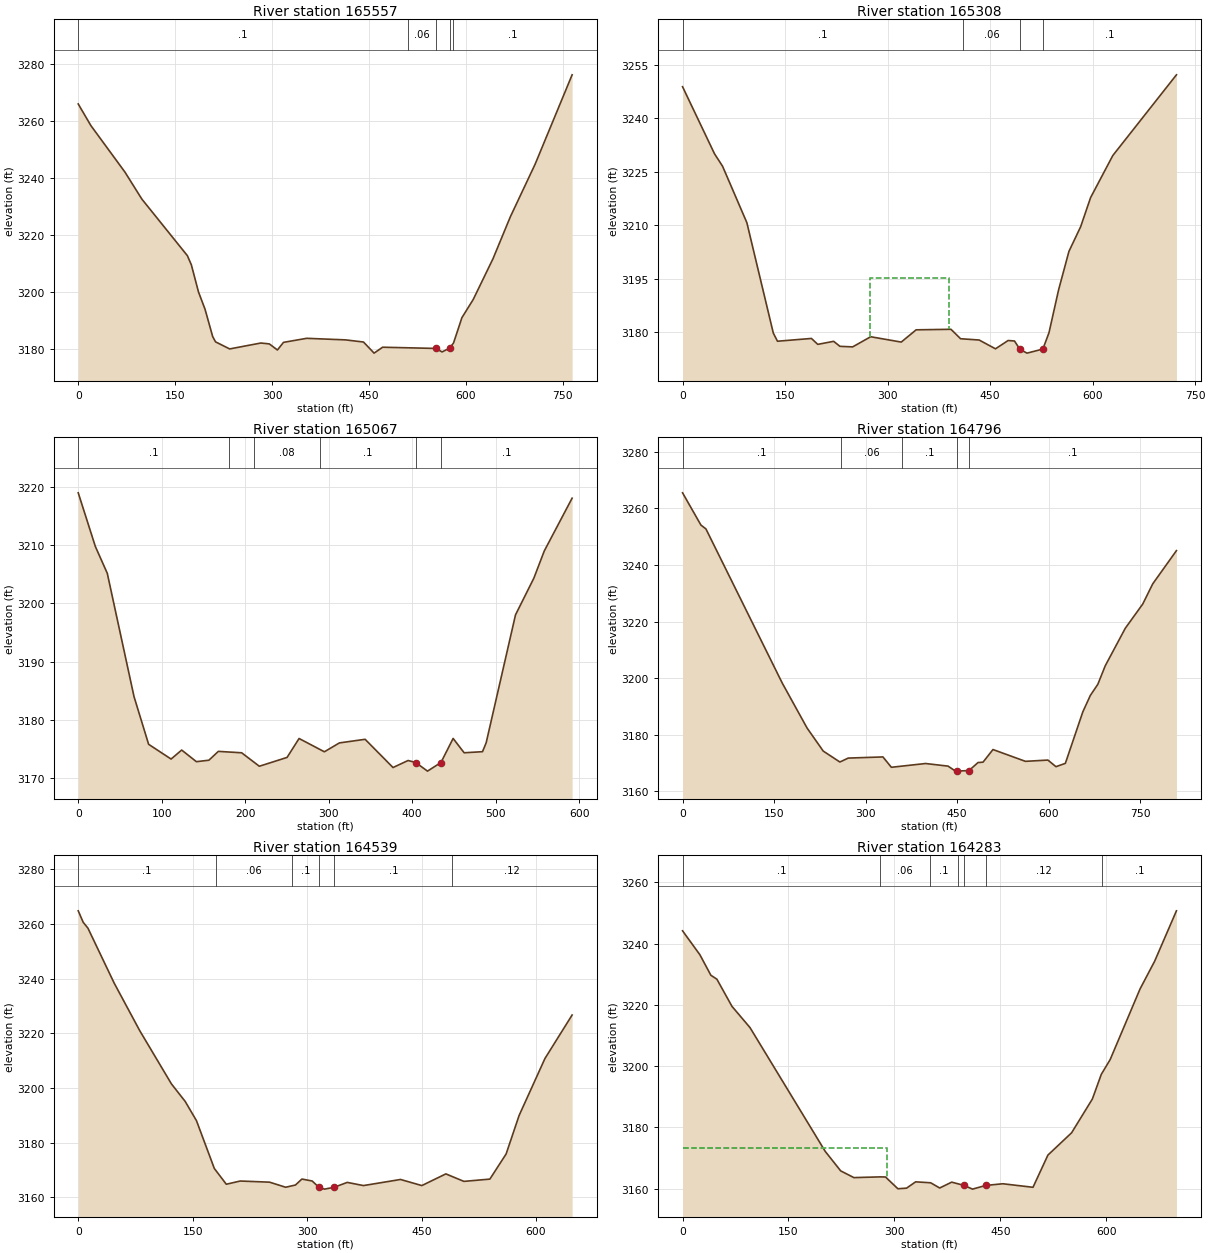
Type RM Length L Ch R = 1 ,165557  ,248.5,248.5,248.5
XS GIS Cut Line= 2
 2337126.2722951632206.4529045062337823.80351679631894.399463225
#Sta/Elev= 30
       0 3265.91    19.6 3258.33    72.2 3242.07    98.5 3232.57   168.9 3212.76
     175 3209.58   186.1 3200.04   196.2 3194.01     208 3184.45   212.4 3182.58
   234.3 3180.09   282.5 3182.16   295.7 3181.85   308.2 3179.72   317.6 3182.39
   353.6 3183.81   413.6 3183.26   441.4 3182.51   457.8 3178.62     471 3180.69
   553.4 3180.26     563 3179.04   574.6 3180.35   580.7 3182.16   593.7 3191.05
   611.2 3197.42   641.9 3211.75   668.5 3226.32     707 3244.83   764.2 3276.12
#Mann= 5 ,-1,0
       0      .1       0     510     .06       0   553.4    .045       0
   574.6     .06       0     580      .1       0
Bank Sta=553.4,574.6
XS Rating Curve= 0 ,0
Exp/Cntr(USF)=0,0
Exp/Cntr=0.3,0.1

Type RM Length L Ch R = 1 ,165308  ,241.3,241.3,241.3
XS GIS Cut Line= 2
2337301.73533387632460.9428516122337924.34964596632093.980871782
#Sta/Elev= 30
       0 3248.85    46.8 3230.01    58.5 3226.55    94.1 3210.69   132.8 3179.69
   138.9 3177.41   188.6 3178.19   197.8 3176.53   221.1 3177.38   230.3 3175.98
   248.9 3175.82   275.3 3178.67     320 3177.17   341.8 3180.61   392.8 3180.76
   406.8 3178.11     434 3177.75   457.9 3175.28   476.4 3177.61   485.7 3177.48
   493.8  3175.1   504.1 3174.07   527.3 3175.22   536.2  3179.8   550.3 3191.86
   565.4 3202.63   582.5 3209.54   597.1 3217.73   629.6 3229.54   722.7 3252.19
#Mann= 4 ,-1,0
       0      .1       0     410     .06       0   493.8    .045       0
   527.3      .1       0
#XS Ineff= 1 ,-1
  273.83   390.63195.262
Permanent Ineff=
       F
Bank Sta=493.8,527.3
XS Rating Curve= 0 ,0
Exp/Cntr=0.3,0.1

Type RM Length L Ch R = 1 ,165067  ,270.5,270.5,270.5
XS GIS Cut Line= 2
2337487.39767177632579.5895362622338025.84282536632334.841739178
#Sta/Elev= 30
       0 3219.05    20.5 3209.81    34.8 3205.19    66.8 3183.96    84.3 3175.74
   111.2  3173.2   123.9 3174.75   141.5 3172.75   156.5    3173   167.8 3174.52
   195.7 3174.28   216.9 3171.96   250.1 3173.48   264.5 3176.74   294.8 3174.45
   312.8 3175.98   343.6  3176.6     377 3171.74   395.1 3172.95   404.2  3172.6
   418.3 3171.12   434.4  3172.6     449 3176.75   462.2 3174.28   484.2 3174.47
   488.6 3176.02   523.7 3198.03   545.7 3204.36   558.2 3209.05   591.5 3218.13
#Mann= 6 ,-1,0
       0      .1       0     180     .07       0     210     .08       0
     290      .1       0   404.2    .045       0   434.4      .1       0
Bank Sta=404.2,434.4
XS Rating Curve= 0 ,0
Exp/Cntr(USF)=0,0
Exp/Cntr=0.3,0.1

Type RM Length L Ch R = 1 ,164796  ,257.4,257.4,257.4
XS GIS Cut Line= 2
     2337494.717632761.5623335312338286.17995142632593.017238152
#Sta/Elev= 30
       0 3265.53    30.1 3254.13    38.3 3252.77   163.4 3198.25     204 3182.38
   230.5 3174.23   257.8 3170.36   271.4 3171.75   328.3 3172.16   342.1  3168.5
   398.2 3169.83     435 3168.91   447.3 3167.14   449.2 3167.15   469.33167.333
   484.1 3170.17   492.3 3170.31   508.6 3174.77   561.8  3170.6   598.6 3171.05
   611.8 3168.71   627.2 3169.89   655.8 3188.08   668.1 3193.89   680.4 3197.83
   692.6  3204.4   725.4 3217.65     754 3226.22   770.4 3233.36   809.2 3245.09
#Mann= 5 ,-1,0
       0      .1       0     260     .06       0     360      .1       0
   449.2    .045       0   469.3      .1       0
Bank Sta=449.2,469.3
XS Rating Curve= 0 ,0
Exp/Cntr=0.3,0.1

Type RM Length L Ch R = 1 ,164539  ,255.8,255.8,255.8
XS GIS Cut Line= 2
2337680.21134844633029.4717764872338289.63336318 632811.03436759
#Sta/Elev= 30
       0 3264.82     6.5 3260.63    12.7 3258.49    47.1  3238.4    80.7 3220.96
   122.2 3201.52   140.2 3195.12     155 3188.08   178.4  3170.6   194.1 3164.84
   212.4 3166.01   250.7  3165.6   271.9 3163.74   284.7 3164.55   293.2 3166.73
   306.7 3166.02   315.73163.657   322.9 3163.05   335.93163.761   352.6 3165.51
   373.9 3164.35   422.5 3166.58   450.4 3164.35   481.9 3168.62   505.6 3165.88
   539.6 3166.72   560.9 3175.91   577.9 3189.97   611.8 3210.82   647.4 3226.72
#Mann= 6 ,-1,0
       0      .1       0     180     .06       0     280      .1       0
   315.7    .045       0   335.9      .1       0     490     .12       0
Bank Sta=315.7,335.9
XS Rating Curve= 0 ,0
Exp/Cntr(USF)=0,0
Exp/Cntr=0.3,0.1

Type RM Length L Ch R = 1 ,164283  ,292.8,292.8,292.8
XS GIS Cut Line= 3
2337682.52609909633303.0699316422338156.01742391633128.675523697
2338341.53601501633069.553852814
#Sta/Elev= 30
       0  3244.2    24.6 3236.37    40.1 3229.69    48.6 3228.41      70 3219.53
    95.5  3212.6     202 3172.18   223.9 3165.81   242.6 3163.61     280 3163.85
   287.4 3163.81   304.9 3159.97   317.2 3160.17     330 3162.23   351.3 3161.92
   364.1 3160.22   381.1 3162.13     399 3161.04   410.5 3159.85   429.6 3161.07
   453.6  3161.6   496.2 3160.45   517.3 3170.96   550.9 3178.26   580.3  3189.3
   592.9 3197.33   605.5 3202.17   647.8 3225.23   668.5  3234.3   699.3 3250.73
#Mann= 7 ,-1,0
       0      .1       0     280     .06       0     350      .1       0
     390     .12       0     399    .045       0   429.6     .12       0
  594.59      .1       0
#XS Ineff= 2 , 0
          288.93 3173.15
Permanent Ineff=
       F       F
Bank Sta=399,429.6
XS Rating Curve= 0 ,0
Exp/Cntr=0.3,0.1