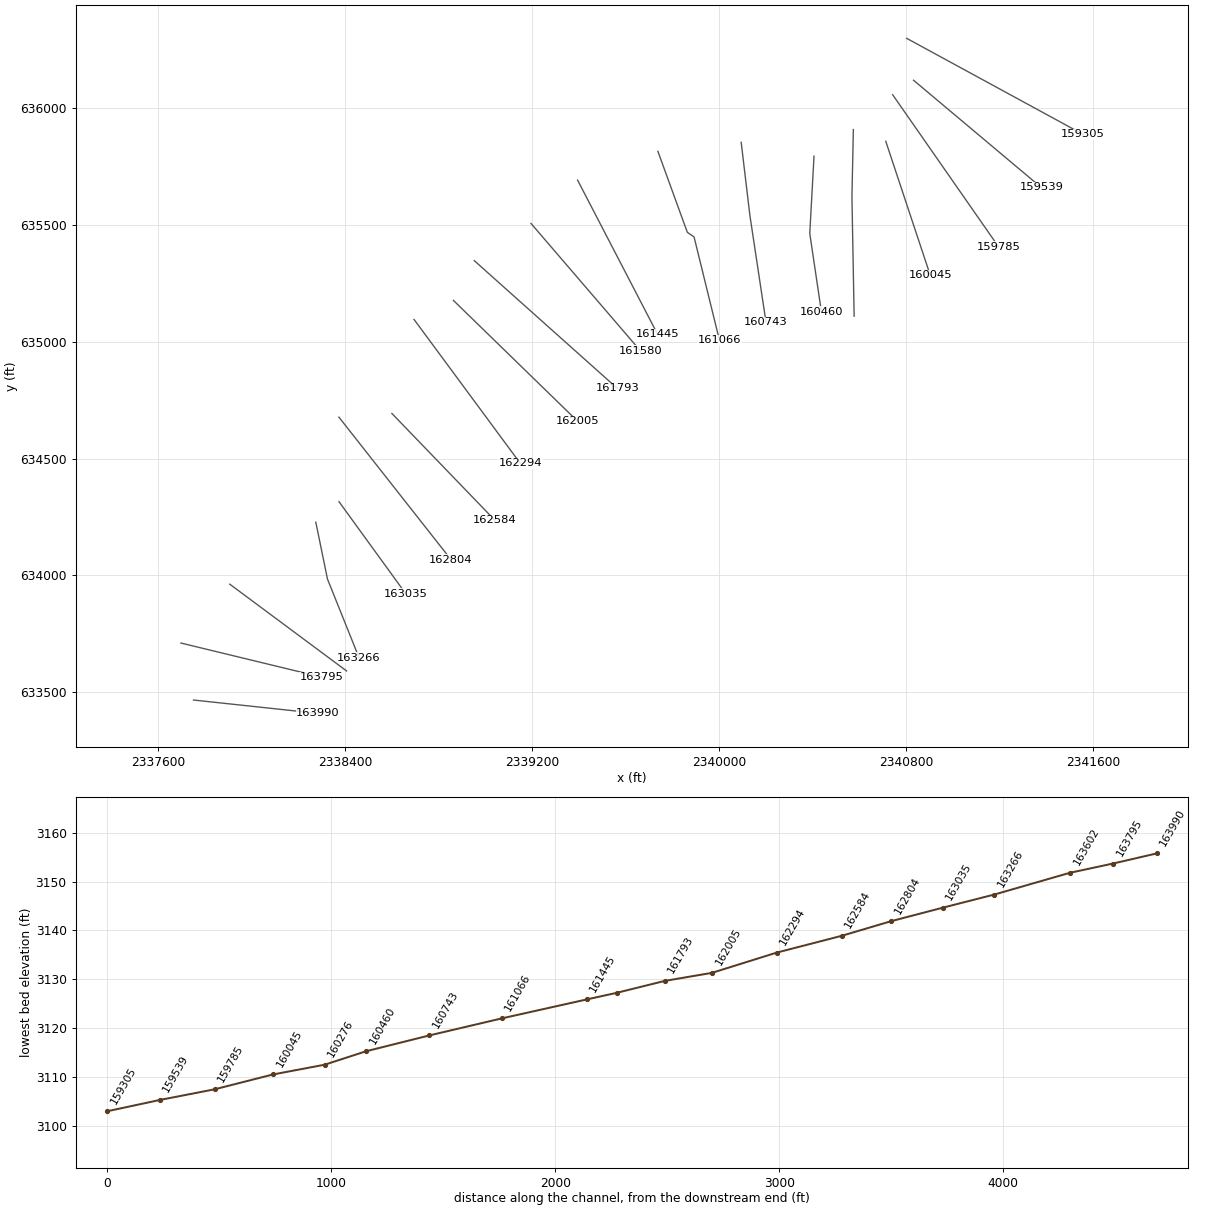
HEC-RAS study LAURELFK.prj: LAURELFK

--- LAURELFK.g01 (geometry) --- (continued)

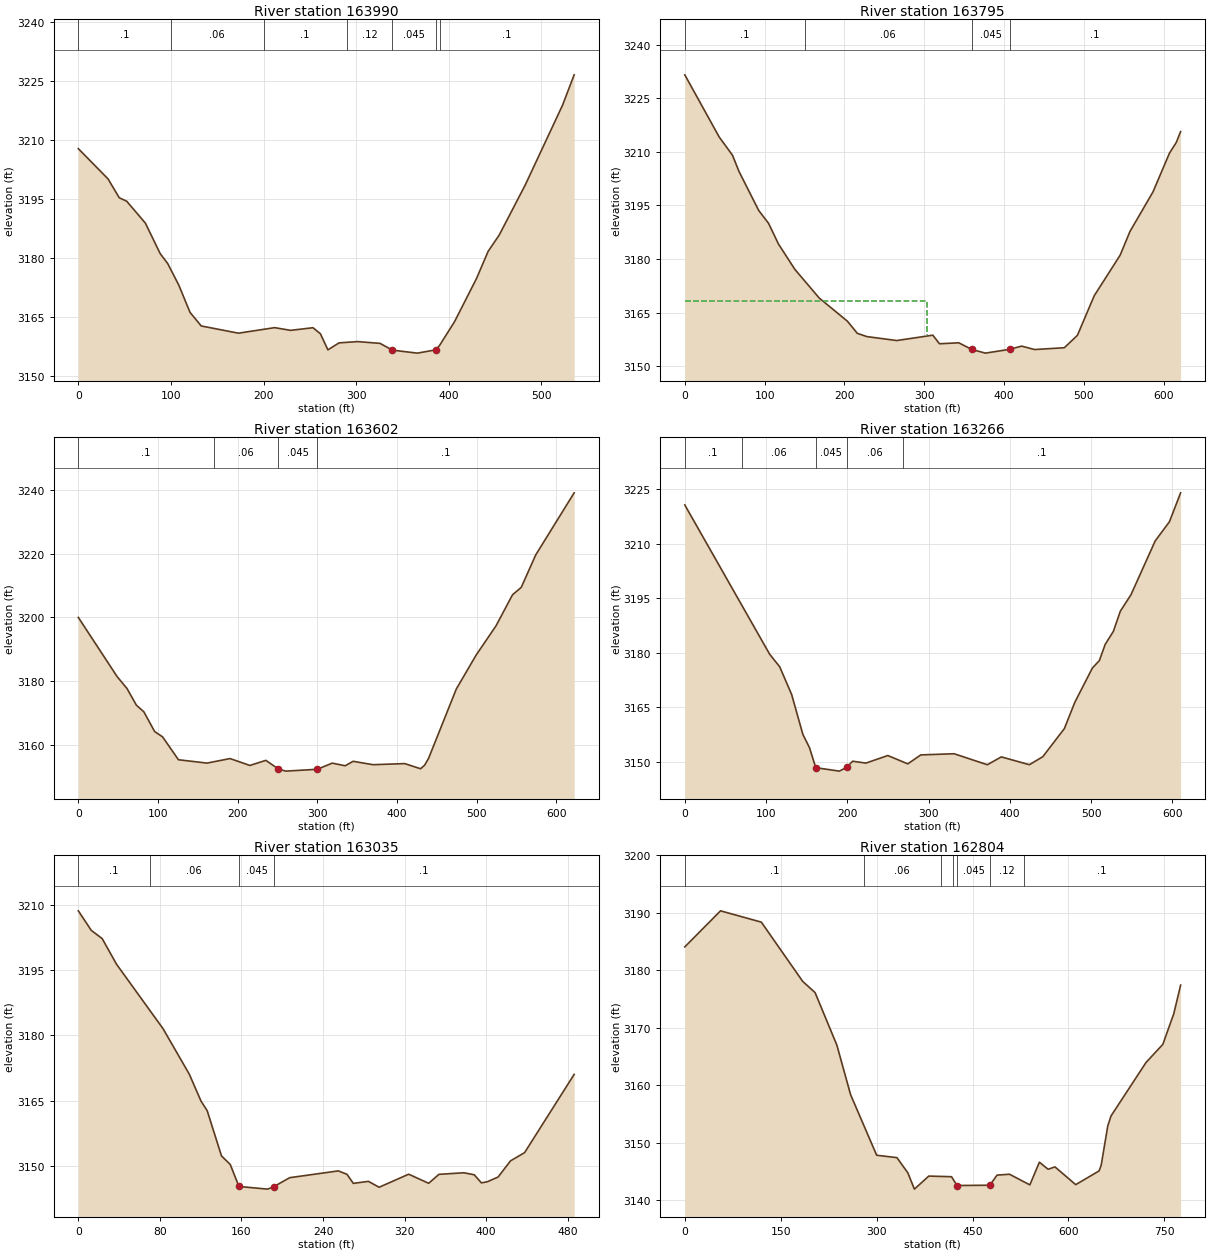
Type RM Length L Ch R = 1 ,163990  ,194.8,194.8,194.8
XS GIS Cut Line= 2
  2337752.237334  633466.62641492338284.56379265633409.518595581
#Sta/Elev= 30
       0 3207.76    32.1 3200.06    44.2 3195.27    52.2  3194.4    72.4 3188.83
    88.4 3181.07    96.5 3178.56   108.6 3173.01   120.6 3166.14   132.7 3162.68
   172.9 3160.84     212 3162.25   229.2 3161.56   253.4 3162.23   261.4 3160.69
   269.5  3156.6   281.5 3158.38   301.7  3158.7   325.8 3158.25   339.1 3156.53
     366 3155.77   385.8 3156.59     390  3157.7   406.3 3163.79     430 3174.76
   442.5 3181.64   454.5  3185.8   482.7 3198.58   522.9 3218.83   535.4 3226.53
#Mann= 7 ,-1,0
       0      .1       0     100     .06       0     200      .1       0
     290     .12       0   339.1    .045       0   385.8     .12       0
     390      .1       0
Bank Sta=339.1,385.8
XS Rating Curve= 0 ,0
Exp/Cntr(USF)=0,0
Exp/Cntr=0.3,0.1

Type RM Length L Ch R = 1 ,163795  ,193.1,193.1,193.1
XS GIS Cut Line= 2
2337698.16920917633710.456678249 2338301.7877123633564.245875608
#Sta/Elev= 30
       0 3231.54    43.2 3214.11    59.7 3209.07    67.9 3204.51    92.6  3193.6
     105 3189.98   117.3 3184.23   137.9 3177.12   168.4 3169.11   203.7 3162.63
   216.1 3159.24     228 3158.33   265.5 3157.22   310.7 3158.72     319 3156.32
   343.2 3156.59   359.5 3154.73   376.6  3153.7   406.9 3154.76   421.9 3155.66
   438.3  3154.7   475.4 3155.21   491.8 3158.67   512.9 3169.76   545.3 3181.08
   557.7 3187.75   586.5  3198.8   607.1 3209.62   615.7 3212.64   621.1 3215.67
#Mann= 4 ,-1,0
       0      .1       0     150     .06       0   359.5    .045       0
   406.9      .1       0
#XS Ineff= 2 , 0
          303.02 3168.25
Permanent Ineff=
       F       F
Bank Sta=359.5,406.9
XS Rating Curve= 0 ,0
Exp/Cntr=0.3,0.1

Type RM Length L Ch R = 1 ,163602  ,336.7,336.7,336.7
XS GIS Cut Line= 2
2337907.24427215633962.2407039942338406.93769119633591.039878418
#Sta/Elev= 30
       0 3200.02    48.7 3181.46      61 3177.76    72.9 3172.49    82.3  3170.4
    95.8 3164.22   105.8 3162.55   125.7 3155.37   161.5 3154.32   190.5 3155.74
   215.4 3153.58   235.4 3155.18   251.3 3152.45   260.3  3151.8   300.1 3152.38
   318.8 3154.31     335 3153.48     345 3154.88   369.9 3153.82   409.8 3154.16
   429.7 3152.55   434.7 3153.65   439.7 3155.79   474.5 3177.54   499.5 3188.23
   524.4 3197.38   545.1 3207.12   556.1 3209.46   574.2 3219.61   622.5 3239.11
#Mann= 4 ,-1,0
       0      .1       0     170     .06       0   251.3    .045       0
   300.1      .1       0
Bank Sta=251.3,300.1
XS Rating Curve= 0 ,0
Exp/Cntr(USF)=0,0
Exp/Cntr=0.3,0.1

Type RM Length L Ch R = 1 ,163266  ,230.9,230.9,230.9
XS GIS Cut Line= 3
2338275.25378304634227.5418478112338325.25911217633984.169614612
 2338460.0100624633648.303089784
#Sta/Elev= 30
       0 3220.73   104.5 3179.57   116.8 3176.13   131.5  3168.5   145.3 3157.51
   153.5 3153.82   161.2 3148.31   190.3 3147.36   199.3 3148.42   206.6 3150.09
   222.9 3149.57   249.9 3151.66   274.5 3149.36   290.5 3151.83   331.5 3152.15
   372.4 3149.12   389.6 3151.28   424.1 3149.13   440.6 3151.32   467.2 3159.08
   480.1 3166.34   501.7 3175.78   510.3 3177.84   517.5 3182.32   527.5 3185.87
   536.1 3191.45   549.1 3195.94     579 3210.81   596.5 3216.09   610.3 3224.07
#Mann= 5 ,-1,0
       0      .1       0      70     .06       0   161.2    .045       0
   199.3     .06       0  268.46      .1       0
Bank Sta=161.2,199.3
XS Rating Curve= 0 ,0
Exp/Cntr=0.3,0.1

Type RM Length L Ch R = 1 ,163035  ,230.5,230.5,230.5
XS GIS Cut Line= 2
 2338374.4354592634315.472690457 2338659.9745558633921.836650147
#Sta/Elev= 30
       0 3208.62    12.7 3204.13    23.4 3202.24    37.4 3196.37    83.1 3181.53
   108.9 3171.05   120.3 3164.91   126.4 3162.68   140.4  3152.3     149 3150.33
   157.5 3145.27   185.7 3144.66   191.9 3145.25   207.3 3147.29     255 3148.85
   263.5 3148.07   269.7 3145.98   284.5 3146.45     295 3145.09     324 3148.09
   343.6    3146   353.7 3148.06   378.1 3148.42   388.3 3147.96   395.3  3146.1
     401 3146.34   411.7 3147.44   423.9 3151.16   437.7 3153.05   486.3 3171.03
#Mann= 4 ,-1,0
       0      .1       0      70     .06       0   157.5    .045       0
   191.9      .1       0
Bank Sta=157.5,191.9
XS Rating Curve= 0 ,0
Exp/Cntr(USF)=0,0
Exp/Cntr=0.3,0.1

Type RM Length L Ch R = 1 ,162804  ,220.2,220.2,220.2
XS GIS Cut Line= 2
     2338374.138      634677.0732338853.66866775634067.562065477
#Sta/Elev= 30
       0 3184.07    55.9 3190.35   119.7 3188.38   184.4 3178.07   203.8 3176.11
   237.8 3166.99   259.4 3158.32   300.1  3147.8   331.8 3147.38   348.9 3144.73
   359.1  3141.9   381.6 3144.17   417.2 3144.06   425.8 3142.53   477.1 3142.58
   488.4 3144.34   507.9 3144.49   539.7 3142.64   554.6 3146.59   568.2 3145.36
     579 3145.77   611.4 3142.68     648 3145.07   651.3 3146.07   661.5 3152.87
   666.6 3154.63   721.4 3163.95   747.7 3167.11   764.8 3172.44   775.5 3177.41
#Mann= 7 ,-1,0
       0      .1       0     280     .06       0     400      .1       0
     420     .12       0   425.8    .045       0   477.1     .12       0
     530      .1       0
Bank Sta=425.8,477.1
XS Rating Curve= 0 ,0
Exp/Cntr=0.3,0.1

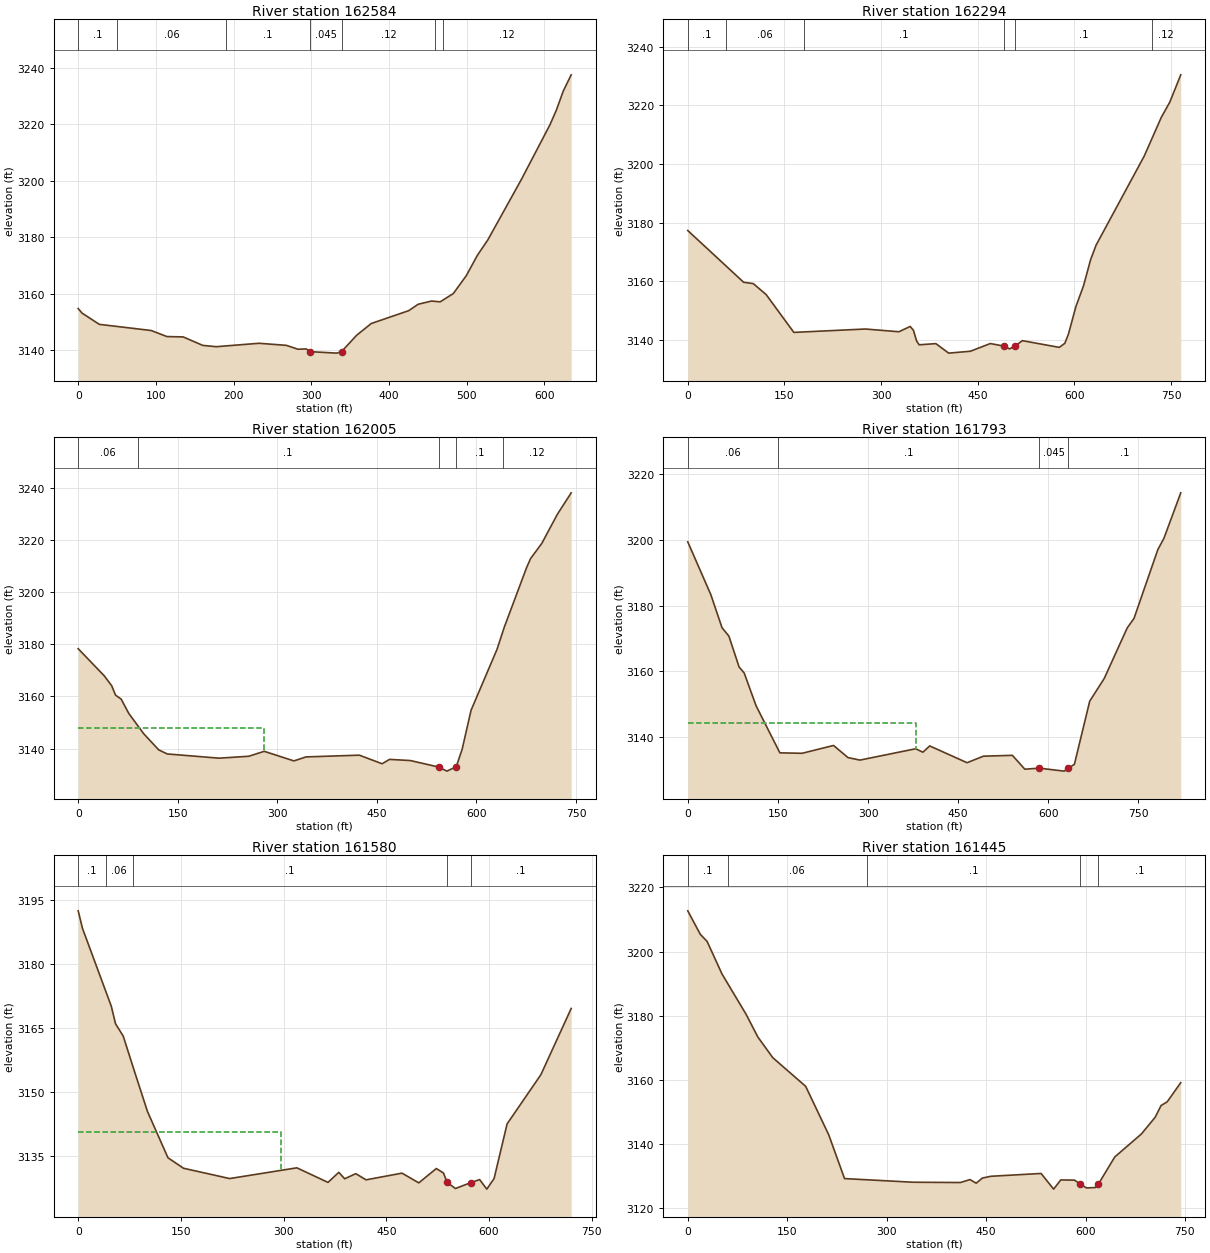
Type RM Length L Ch R = 1 ,162584  ,290.5,290.5,290.5
XS GIS Cut Line= 2
2338600.82717151634692.7922109612339041.37320626634235.929656405
#Sta/Elev= 30
       0 3154.71       5  3153.1    27.2 3149.11    93.9 3146.93   114.3 3144.78
   135.1 3144.66   160.4 3141.65   177.7 3141.19   232.8  3142.4     268 3141.67
   282.9 3140.29   293.5  3140.4   298.7 3139.43   332.9 3138.91   339.1 3139.46
   358.5 3145.25   377.3 3149.41   425.5 3153.96   437.7 3156.24   455.1 3157.38
     466 3157.09   482.9 3160.02   499.6 3166.35   514.1 3173.66   527.4 3179.06
   570.7 3200.55   607.5 3219.94   615.7 3225.11   624.5 3231.82   634.7 3237.57
#Mann= 7 ,-1,0
       0      .1       0      50     .06       0     190      .1       0
   298.7    .045       0   339.1     .12       0     460      .1       0
     470     .12       0
Bank Sta=298.7,339.1
XS Rating Curve= 0 ,0
Exp/Cntr(USF)=0,0
Exp/Cntr=0.3,0.1

Type RM Length L Ch R = 1 ,162294  ,288.8,288.8,288.8
XS GIS Cut Line= 2
2338695.71124113635094.9257032232339150.10794598 634479.45772015
#Sta/Elev= 30
       0 3177.27    86.7 3159.63   101.7 3159.17   121.7 3155.42   164.6 3142.54
   275.6 3143.69   327.7 3142.76   345.2 3144.57   350.2 3143.25   355.2 3139.57
   359.1 3138.31     385 3138.71   404.9 3135.47   438.5 3136.11   469.5 3138.73
   490.7 3137.86   499.4 3136.91   507.9 3137.91   519.3 3139.72   576.5 3137.43
   585.1 3138.81   590.8 3142.01   602.2 3151.29   614.1 3158.43   625.1 3167.32
   633.6 3172.28   708.2 3202.61   734.8 3215.85     748 3221.05     765 3230.35
#Mann= 6 ,-1,0
       0      .1       0      60     .06       0     180      .1       0
   490.7    .045       0   507.9      .1       0     720     .12       0
Bank Sta=490.7,507.9
XS Rating Curve= 0 ,0
Exp/Cntr=0.3,0.1

Type RM Length L Ch R = 1 ,162005  ,211.9,211.9,211.9
XS GIS Cut Line= 2
2338863.99983828635176.6418352172339396.32629694 634658.59233139
#Sta/Elev= 30
       0 3178.28    39.3 3167.87    50.5 3164.06    56.3 3160.46    64.8 3158.95
    76.1 3153.51    98.7 3145.68   121.4 3139.47   134.2 3137.92   212.3  3136.3
     257 3137.03   280.3 3138.93     325 3135.25   343.3 3136.78   423.6 3137.45
   457.9 3134.16   469.1 3135.83   500.4 3135.39   542.9 3132.91   555.6 3131.33
   569.6 3133.02   578.5 3139.72   591.9 3154.64     631 3178.01   642.1 3186.61
   675.6 3209.38   681.7 3212.88   698.4 3218.62   721.9  3229.8   742.8 3238.06
#Mann= 5 ,-1,0
       0     .06       0      90      .1       0   542.9    .045       0
   569.6      .1       0     640     .12       0
#XS Ineff= 2 , 0
          279.48 3147.89
Permanent Ineff=
       F       F
Bank Sta=542.9,569.6
XS Rating Curve= 0 ,0
Exp/Cntr(USF)=0,0
Exp/Cntr=0.3,0.1

Type RM Length L Ch R = 1 ,161793  ,212.5,212.5,212.5
XS GIS Cut Line= 2
2338953.25298477635346.7802867312339565.10805557634800.324187265
#Sta/Elev= 30
       0 3199.37    38.4 3183.32      57 3173.27    68.5  3170.7    85.4 3161.34
    93.9  3159.5   113.7 3149.54   153.3 3135.23   190.2 3135.09   242.6 3137.47
   266.6 3133.79   286.5 3133.02   379.3 3136.47   391.3 3135.42   402.6 3137.33
   464.8 3132.23     492 3134.21   540.2 3134.47   560.9 3130.26   584.9 3130.57
   626.4 3129.67   632.9 3130.49   643.4 3131.75   668.9 3150.94     693 3157.82
   731.3  3173.2   742.6  3176.1   782.3 3197.03   792.3  3200.4   820.4 3214.27
#Mann= 4 ,-1,0
       0     .06       0     150      .1       0   584.9    .045       0
   632.9      .1       0
#XS Ineff= 2 , 0
          379.31 3144.25
Permanent Ineff=
       F       F
Bank Sta=584.9,632.9
XS Rating Curve= 0 ,0
Exp/Cntr=0.3,0.1

Type RM Length L Ch R = 1 ,161580  ,135.6,135.6,135.6
XS GIS Cut Line= 2
2339196.05461826635505.9137448592339665.15456267634959.763568034
#Sta/Elev= 30
       0 3192.57     6.3 3188.44    48.4 3170.16    54.5 3166.07    65.8 3163.16
      80 3155.99      80 3155.97   101.2 3145.47   131.1 3134.61   153.8 3132.15
   221.2 3129.73   319.4 3132.25   364.8 3128.83   380.6 3131.19   389.2 3129.68
   405.4 3130.88   420.4 3129.43   472.9    3131   497.4 3128.72     523 3132.08
   533.5 3131.04   538.8 3128.85   550.9 3127.39   573.6 3128.79   586.3 3129.49
   596.8 3127.25   607.4 3129.74   626.4 3142.56   675.7  3154.1     720 3169.65
#Mann= 5 ,-1,0
       0      .1       0      40     .06       0      80      .1       0
   538.8    .045       0   573.6      .1       0
#XS Ineff= 2 , 0
          296.21  3140.7
Permanent Ineff=
       F       F
Bank Sta=538.8,573.6
XS Rating Curve= 0 ,0
Exp/Cntr(USF)=0,0
Exp/Cntr=0.3,0.1

Type RM Length L Ch R = 1 ,161445  ,379.2,379.2,379.2
XS GIS Cut Line= 2
2339395.46588389635691.0671842952339738.05012805635030.942141738
#Sta/Elev= 30
       0 3212.72    18.9  3205.4    29.2 3203.17    51.7    3193    87.8 3180.51
   105.7 3173.36   128.3 3166.89   177.9 3157.95   212.6 3142.86   236.5 3129.17
   340.1 3128.03   411.4 3127.94   425.7 3128.86   435.1 3127.73   444.4 3129.33
   457.3 3129.89     533 3130.77   551.9 3125.88   562.7 3128.75   583.6 3128.68
     592 3127.46   601.5 3126.25     615 3126.38  619.43 3127.44   644.1 3135.91
   684.3 3143.09   705.1 3148.31     714 3151.97   723.2 3153.11   743.7 3159.11
#Mann= 5 ,-1,0
       0      .1       0      60     .06       0     270      .1       0
     592    .045       0  619.43      .1       0
Bank Sta=592,619.43
XS Rating Curve= 0 ,0
Exp/Cntr=0.3,0.1

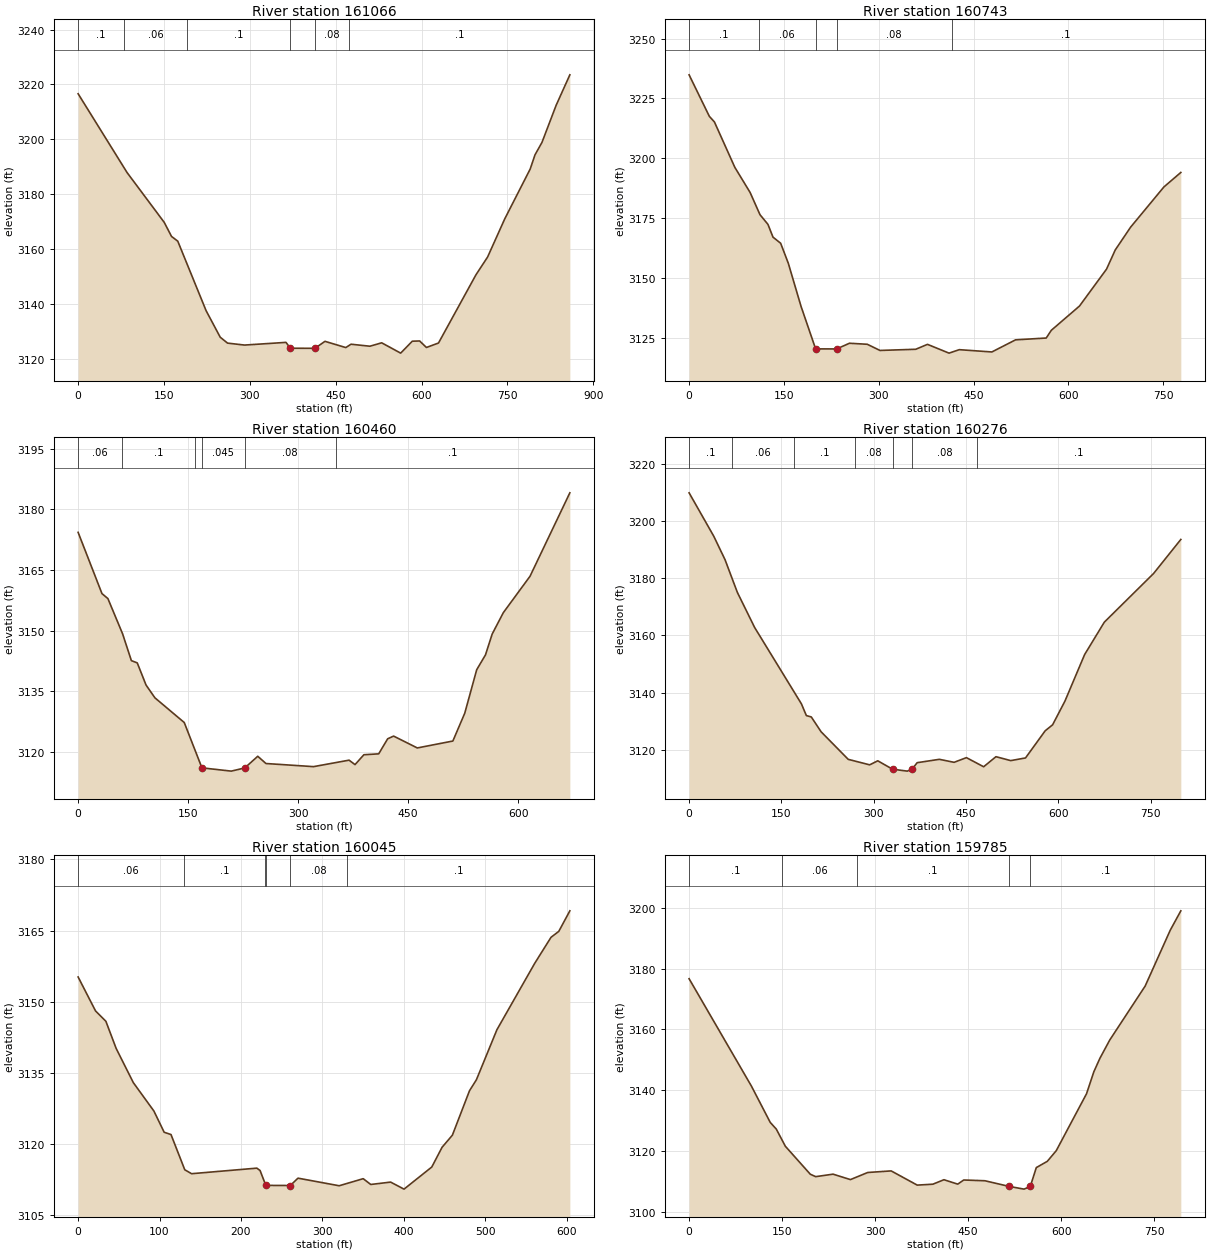
Type RM Length L Ch R = 1 ,161066  ,322.8,322.8,322.8
XS GIS Cut Line= 4
 2339738.9415004635814.5185648242339864.98508698635467.868936326
2339893.74697943635448.207658711 2340002.4895684635005.839946596
#Sta/Elev= 30
       0  3216.6    85.5 3187.87   150.4 3169.71   163.2 3164.56   174.1 3162.84
   223.6 3137.49   248.3  3127.8   261.1 3125.65   290.8 3124.94   363.2 3125.92
   370.8 3123.78   413.9 3123.76   431.3  3126.3   467.7 3124.03   476.8 3125.25
   509.8 3124.52   530.4 3125.76   563.6    3122   583.9 3126.35   596.7 3126.44
   608.6 3124.06   629.7 3125.69   695.1 3150.56   715.5 3157.06   745.4 3170.95
   789.9 3189.15   798.3 3194.33   810.5 3198.87   835.2 3212.38   859.2 3223.51
#Mann= 6 ,-1,0
       0      .1       0      80     .06       0     190      .1       0
   370.8    .045       0   413.9     .08       0  473.69      .1       0
Bank Sta=370.8,413.9
XS Rating Curve= 0 ,0
Exp/Cntr(USF)=0,0
Exp/Cntr=0.3,0.1

Type RM Length L Ch R = 1 ,160743  ,283.2,283.2,283.2
XS GIS Cut Line= 3
2340095.38625806635852.9745951752340132.66949919635540.096686296
2340201.70394788635082.712192368
#Sta/Elev= 30
       0 3234.83      32 3217.49    40.1 3215.12    72.3 3196.18    96.5 3185.66
   112.1 3176.38   124.7 3172.34   132.7 3166.99   144.8 3164.44   156.9 3156.08
     177 3138.11   200.1  3120.3   233.4 3120.27   253.6 3122.65   281.8 3122.22
   301.9 3119.64   358.5 3120.13     377 3122.19   411.1 3118.52   427.3 3119.96
   478.9 3119.01   516.3 3124.07   564.8 3124.83   572.9 3128.07   617.4 3138.19
   660.2 3153.62     674 3161.64   698.3 3171.17   750.9 3187.96   777.7 3194.02
#Mann= 5 ,-1,0
       0      .1       0     110     .06       0   200.1    .045       0
   233.4     .08       0  415.09      .1       0
Bank Sta=200.1,233.4
XS Rating Curve= 0 ,0
Exp/Cntr=0.3,0.1

Type RM Length L Ch R = 1 ,160460  ,183.9,183.9,183.9
XS GIS Cut Line= 3
2340407.01034799635793.6780754232340388.88088154635462.815312699
2340438.73691428635127.420183362
#Sta/Elev= 30
       0 3174.29    32.5 3159.15    40.6 3157.92    60.6 3149.22    72.6 3142.58
    80.6 3142.03    92.6 3136.55   104.7 3133.39   144.7 3127.28   168.8 3116.08
   208.8 3115.27   227.2 3116.06   244.9 3118.94   256.1 3117.15     321 3116.38
   369.4 3117.98   377.5 3116.88   389.6 3119.32   409.8 3119.54     422 3123.26
   430.1 3123.93   462.4    3121   510.9 3122.71   527.1 3129.58   543.4 3140.33
   555.4 3144.02   564.5 3149.15   579.7 3154.44   616.1 3163.44   670.4 3184.06
#Mann= 6 ,-1,0
       0     .06       0      60      .1       0     160     .08       0
   168.8    .045       0   227.2     .08       0  351.36      .1       0
Bank Sta=168.8,227.2
XS Rating Curve= 0 ,0
Exp/Cntr(USF)=0,0
Exp/Cntr=0.3,0.1

Type RM Length L Ch R = 1 ,160276  ,231.3,231.3,231.3
XS GIS Cut Line= 3
2340575.38975717635907.5978987542340569.30205735635619.947900534
2340578.72780203635108.931155555
#Sta/Elev= 30
       0 3209.89    40.1  3194.7    58.4 3186.49    78.4 3175.06   106.4 3162.81
   182.5 3136.05   190.5 3131.96   198.5 3131.48   214.5 3126.28   258.5 3116.65
   293.3 3114.73   306.5 3116.14   330.5  3113.2   354.5 3112.53   362.5 3113.32
   370.5 3115.48   406.5 3116.66   430.5 3115.61   450.5 3117.25   478.5 3114.06
   498.5 3117.58   522.5 3116.21   546.5 3117.14   578.5 3126.65   590.5 3128.73
   610.5    3137   642.5  3153.3   674.5 3164.64   754.6 3181.68   798.8 3193.58
#Mann= 7 ,-1,0
       0      .1       0      70     .06       0     170      .1       0
     270     .08       0   330.5    .045       0   362.5     .08       0
  467.71      .1       0
Bank Sta=330.5,362.5
XS Rating Curve= 0 ,0
Exp/Cntr=0.3,0.1

Type RM Length L Ch R = 1 ,160045  ,259.6,259.6,259.6
XS GIS Cut Line= 2
2340714.02341844635857.5111162182340904.38281618635284.166739716
#Sta/Elev= 30
       0 3155.22    21.4 3148.07    34.1 3145.89    46.7 3140.18    67.8 3132.97
    93.1 3126.98   105.7 3122.51   114.1 3122.03     131 3114.61   139.4 3113.78
   219.5 3114.95   223.5 3114.46   230.6 3111.32   260.7 3111.29   270.1 3112.84
   320.7 3111.24   350.2 3112.73   359.5 3111.51   383.9 3112.01   400.4 3110.53
   434.5 3115.19   447.1 3119.34   459.8  3121.9   480.8 3131.25   489.3 3133.57
   514.5 3144.11   560.9 3158.09     581 3163.59   590.5 3164.83   604.1 3169.16
#Mann= 6 ,-1,0
       0     .06       0     130      .1       0     230     .08       0
   230.6    .045       0   260.7     .08       0     330      .1       0
Bank Sta=230.6,260.7
XS Rating Curve= 0 ,0
Exp/Cntr(USF)=0,0
Exp/Cntr=0.3,0.1

Type RM Length L Ch R = 1 ,159785  ,245.6,245.6,245.6
XS GIS Cut Line= 2
2340743.54121416636056.5441854862341196.63767293635406.033455211
#Sta/Elev= 30
       0 3176.66   100.6 3141.32   130.8 3129.44   140.6 3127.23   155.2 3121.59
   195.4  3112.4   204.1  3111.6   232.1 3112.42   260.1 3110.63     288 3112.97
   325.8 3113.49   367.8 3108.82     393 3109.12   410.9 3110.59   433.1 3109.14
   442.8  3110.5     477 3110.25   515.63108.411     540  3107.5   550.1 3108.38
   559.8 3114.58   577.5 3116.63   591.9 3120.12   640.8 3138.86   652.4 3145.99
   662.2 3150.45   678.1 3156.48   735.3 3174.25   775.8 3192.63   792.8 3198.98
#Mann= 5 ,-1,0
       0      .1       0     150     .06       0     270      .1       0
   515.6    .045       0   550.1      .1       0
Bank Sta=515.6,550.1
XS Rating Curve= 0 ,0
Exp/Cntr=0.3,0.1

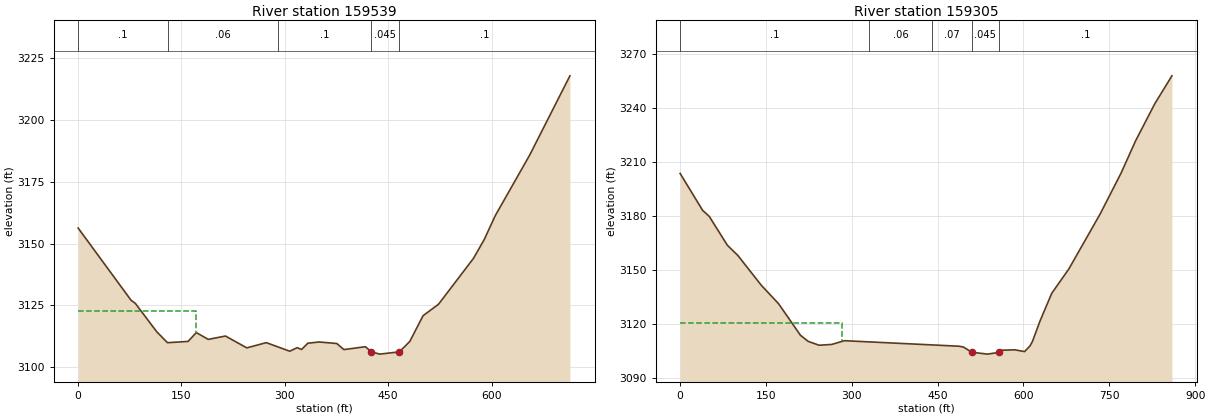
Type RM Length L Ch R = 1 ,159539  ,234,234,234
XS GIS Cut Line= 2
2340832.80522321636118.635870803 2341379.4086367635659.733751271
#Sta/Elev= 30
       0 3156.35    76.9 3127.09    82.9 3125.89   114.2 3114.32   129.7 3109.94
   159.6 3110.45   171.5 3114.03   188.9 3111.27   213.8 3112.64   244.8 3107.84
   273.1 3109.96   307.1 3106.49   317.8 3107.91   324.3 3107.21   333.4 3109.73
   349.8 3110.22   375.4 3109.61   385.7 3107.15     417 3108.31   425.3 3106.28
   437.7 3105.31   466.2 3106.23   481.3 3110.43   500.6 3120.87     523 3125.49
   573.7 3144.05   589.4 3151.71   605.3 3161.32   655.5 3185.96   713.7 3217.95
#Mann= 5 ,-1,0
       0      .1       0     130     .06       0     290      .1       0
   425.3    .045       0   466.2      .1       0
#XS Ineff= 2 , 0
           171.4 3122.76
Permanent Ineff=
       F       F
Bank Sta=425.3,466.2
XS Rating Curve= 0 ,0
Exp/Cntr(USF)=0,0
Exp/Cntr=0.3,0.1

Type RM Length L Ch R = 1 ,159305  ,205.4,205.4,205.4
XS GIS Cut Line= 2
 2340803.5946138636297.903143366 2341558.4147455635886.959327071
#Sta/Elev= 30
       0 3203.49    39.3 3182.95    50.8 3179.65    82.6 3163.52   100.9 3157.87
   141.8 3141.31     172 3131.06   210.3 3113.48   223.8  3110.1   242.8 3107.96
   264.8 3108.39     287 3110.48   486.7 3107.42   495.1 3106.96   509.5 3104.07
   536.9 3103.01   557.23103.958     562 3105.16   584.8 3105.41   601.8 3104.42
   611.4 3107.58   615.5 3109.97   628.9 3121.44   649.4 3136.85   679.3  3150.4
   733.9 3180.91   770.4 3203.61   796.2 3221.83   829.6 3242.35   859.4 3257.78
#Mann= 5 ,-1,0
       0      .1       0     330     .06       0     440     .07       0
   509.5    .045       0   557.2      .1       0
#XS Ineff= 2 , 0
          283.21  3120.5
Permanent Ineff=
       F       F
Bank Sta=509.5,557.2
XS Rating Curve= 0 ,0
Exp/Cntr=0.3,0.1