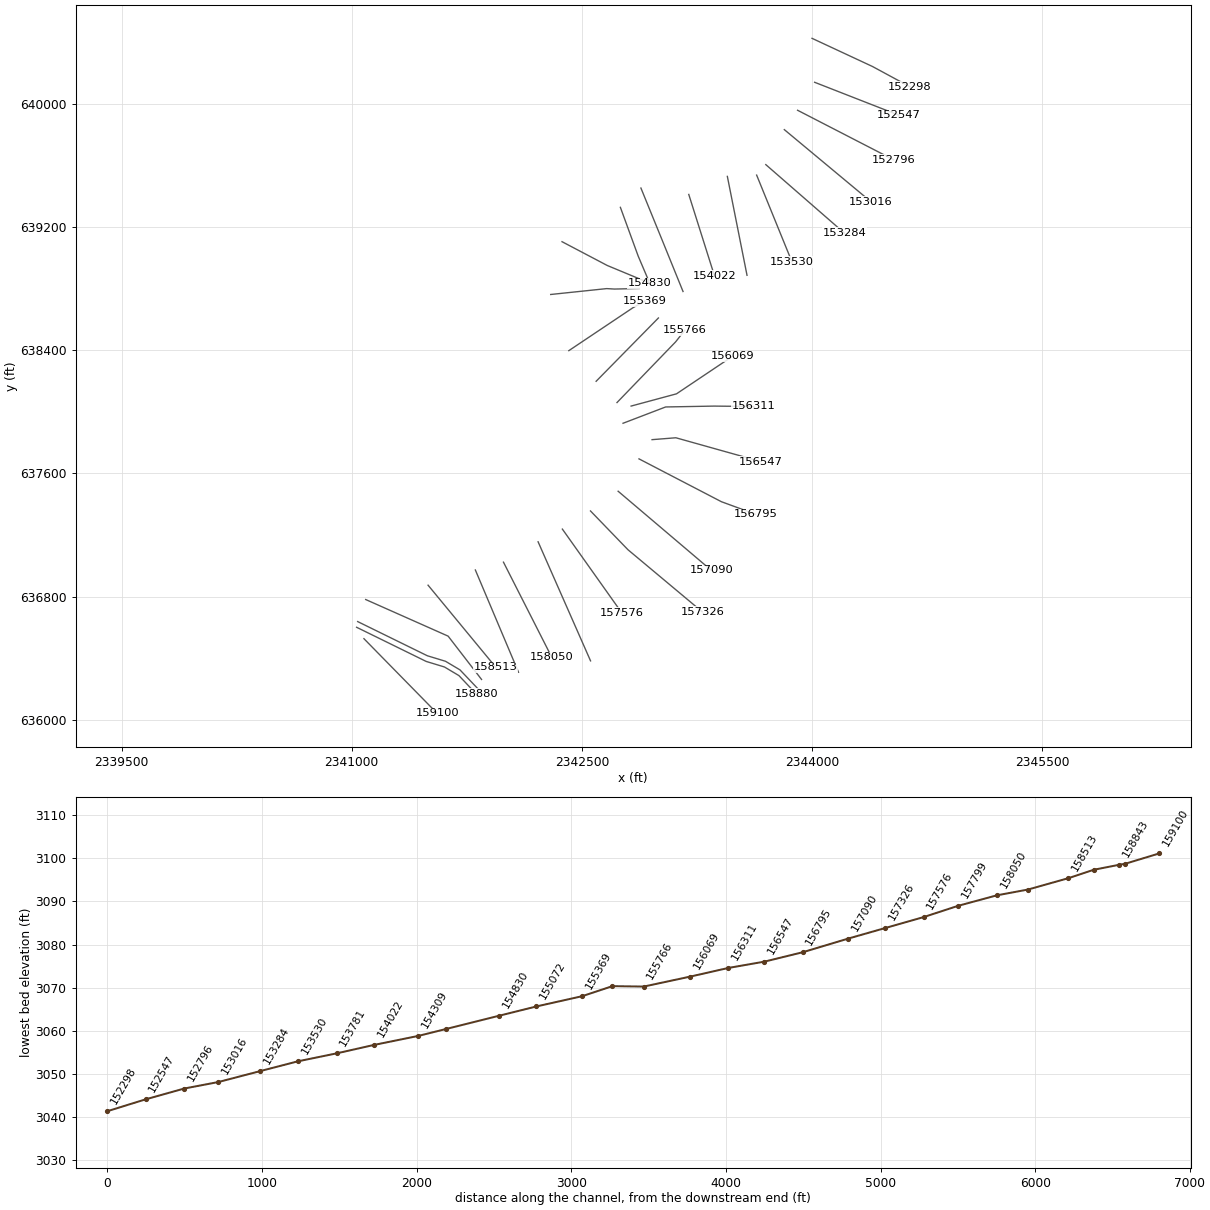
HEC-RAS study LAURELFK.prj: LAURELFK

--- LAURELFK.g01 (geometry) --- (continued)

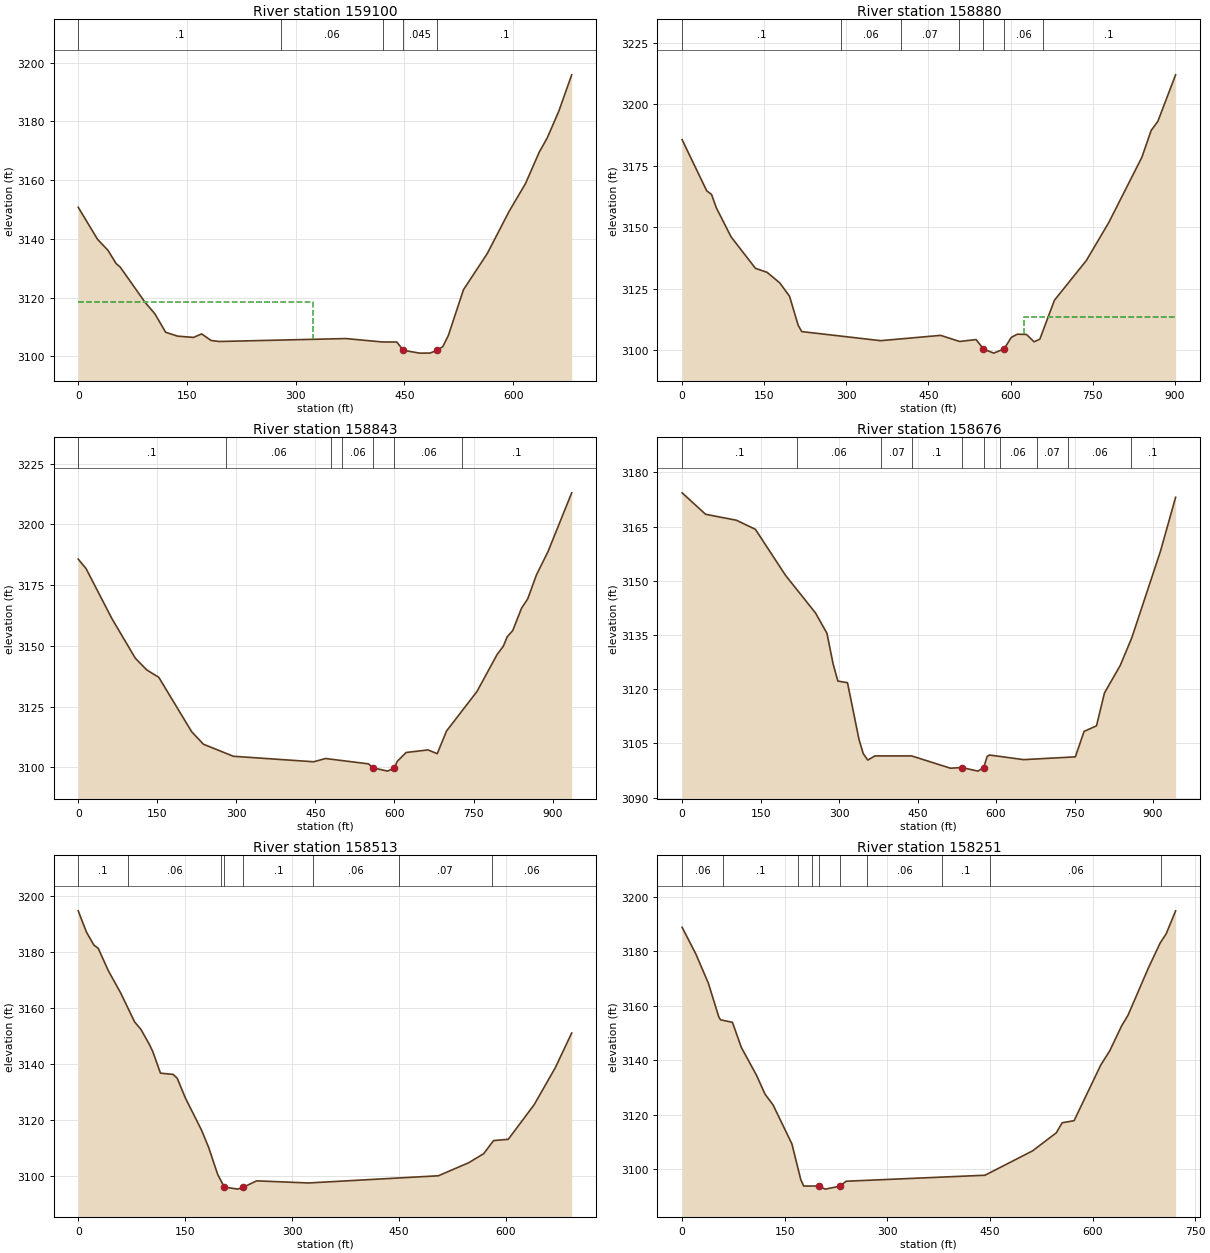
Type RM Length L Ch R = 1 ,159100  ,219.7,219.7,219.7
XS GIS Cut Line= 2
2341079.59258527636526.5488659422341556.85078958636041.132401726
#Sta/Elev= 30
       0 3150.76    26.8  3139.8      41 3136.13    52.2 3131.62      58 3130.38
    92.1 3118.44     106 3114.41   120.6 3108.21   137.1 3106.89     159 3106.46
   170.2 3107.65   183.4  3105.4   194.8 3105.07   369.1 3106.07     420  3104.9
   439.5 3104.89   448.3 3102.09   470.9 3101.11   485.1 3101.12   494.73102.044
   502.9 3103.32   510.5 3107.09   531.4 3122.69   564.3 3135.03   594.2 3149.29
     617 3158.84   635.8 3169.46     647  3174.4   662.7 3183.32   680.7 3195.84
#Mann= 5 ,-1,0
       0      .1       0     280     .06       0     420      .1       0
   448.3    .045       0   494.7      .1       0
#XS Ineff= 2 , 0
          324.08 3118.59
Permanent Ineff=
       F       F
Bank Sta=448.3,494.7
XS Rating Curve= 0 ,0
Exp/Cntr(USF)=0,0
Exp/Cntr=0.3,0.1

Type RM Length L Ch R = 1 ,158880  ,37.8,37.8,37.8
XS GIS Cut Line= 5
2341031.85837676636600.6432871552341485.63912515636378.531375229
2341604.19423984636342.654192821 2341698.3903109 636286.76592379
2341810.56638456636168.471155199
#Sta/Elev= 30
       0 3185.64    44.9 3164.82    53.7 3163.36    62.6 3157.86    89.5 3146.05
     134 3133.24   155.3 3131.62   178.5  3127.3   196.3 3121.86   212.1 3110.03
   218.6 3107.49   362.7 3103.79   472.3 3105.95     507 3103.46   537.1 3104.24
  550.57 3100.41   569.3 3098.72  588.21 3100.41   601.4 3105.13   612.4 3106.42
   629.1 3106.34     643 3103.34   653.5 3104.38   680.2 3120.24   738.6 3136.45
   779.4 3151.85     840 3178.47     857 3189.41   869.1 3193.05   901.6 3212.03
#Mann= 7 ,-1,0
       0      .1       0     290     .06       0     400     .07       0
  505.22     .06       0  550.57    .045       0  588.21     .06       0
  659.09      .1       0
#XS Ineff= 2 , 0
                          624.93         3113.24
Permanent Ineff=
       F       F
Bank Sta=550.57,588.21
XS Rating Curve= 0 ,0
Exp/Cntr(USF)=0,0
Exp/Cntr=0.3,0.1

Type RM Length L Ch R = 1 ,158843  ,166.6,166.6,166.6
XS GIS Cut Line= 5
2341038.86781772636637.6573649832341492.64856612636415.545453058
2341611.20368081 636379.668270652341705.39975186636323.780001619
    2341841.7601636180.664530276
#Sta/Elev= 30
       0  3185.7    14.8 3181.85    64.1 3161.17   108.3 3144.96   129.9 3140.15
   152.9 3137.08   215.2 3114.72   237.5 3109.57   294.4  3104.6   446.8 3102.34
   469.1 3103.68   550.7 3101.48   559.1 3099.87   586.9 3098.49  600.01 3099.84
     605 3102.43   622.2 3106.16   663.7 3107.22   681.2 3105.66   698.8 3114.99
   756.6 3131.27   794.8 3146.48   806.4 3149.82     814 3153.77   824.5 3156.36
   841.2 3165.56   852.8 3169.33   869.3 3179.16   891.4 3188.84   936.3 3212.98
#Mann= 7 ,-1,0
       0      .1       0     280     .06       0     480     .07       0
     500     .06       0   559.1    .045       0  600.01     .06       0
  729.09      .1       0
Bank Sta=559.1,600.01
XS Rating Curve= 0 ,0
Exp/Cntr(USF)=0,0
Exp/Cntr=0.3,0.1

Type RM Length L Ch R = 1 ,158676  ,163.2,163.2,163.2
XS GIS Cut Line= 3
2341091.13153794636780.9340548452341628.28988026636542.973161992
2341845.87237022636261.598505848
#Sta/Elev= 30
       0 3174.33    44.9 3168.39   103.7 3166.75   140.1 3164.23   197.7 3151.49
   254.9  3141.1   276.8 3135.47   288.6    3127   297.7 3122.24   316.1 3121.79
     338 3106.15   346.2 3102.16   354.9 3100.38   368.6 3101.53   438.6 3101.53
   512.9 3098.13   534.9 3098.31   565.5 3097.32  576.46  3098.3     583 3101.39
   587.4 3101.78   652.7  3100.5   751.6 3101.27   768.3 3108.32     792 3109.85
   807.2 3118.94   837.5  3126.6   859.6 3134.27   914.3 3158.19   943.2 3173.09
#Mann= 10 ,-1,0
       0      .1       0     220     .06       0     380     .07       0
     440      .1       0   534.9    .045       0  576.46      .1       0
  607.51     .06       0  677.51     .07       0  737.51     .06       0
  857.51      .1       0
Bank Sta=534.9,576.46
XS Rating Curve= 0 ,0
Exp/Cntr=0.3,0.1

Type RM Length L Ch R = 1 ,158513  ,261.8,261.8,261.8
XS GIS Cut Line= 2
2341497.53086158636874.1130108652341938.87801433636340.658626235
#Sta/Elev= 30
       0 3194.77    11.6 3187.15      22 3182.54    28.1 3181.38    42.3 3173.37
    59.4 3165.52    79.2 3155.07    87.8  3152.5    99.9 3147.05   104.8  3144.4
   115.4  3136.8   133.2 3136.35   138.9    3135   150.3 3127.97     173 3116.46
   182.9 3110.36   195.7 3100.62   204.9 3096.15   223.8 3095.38   231.93096.098
   250.4 3098.34   323.1 3097.58   505.4 3100.15     548 3104.82   568.9 3108.04
   582.7 3112.71   603.4 3113.17   639.8 3125.56   669.3  3138.7   692.4 3151.14
#Mann= 8 ,-1,0
       0      .1       0      70     .06       0     200      .1       0
   204.9    .045       0   231.9      .1       0     330     .06       0
     450     .07       0     580     .06       0
Bank Sta=204.9,231.9
XS Rating Curve= 0 ,0
Exp/Cntr(USF)=0,0
Exp/Cntr=0.3,0.1

Type RM Length L Ch R = 1 ,158251  ,201.4,201.4,201.4
XS GIS Cut Line= 2
2341805.63276685636972.928314115 2342086.8470212636308.525639678
#Sta/Elev= 30
       0 3188.88    20.1 3179.08    38.4 3168.35    53.6 3156.01    56.2 3154.91
    73.6 3153.99    86.6 3144.76   108.6 3134.63   121.3 3127.59     133 3123.65
   160.5 3109.36   173.5 3096.23   177.8 3093.87   199.5 3093.88   209.3 3092.74
   230.6 3093.82   239.8 3095.64   442.8 3097.84   512.3 3106.78     547  3113.4
   555.7 3117.11   573.1 3117.88   612.1 3138.32   625.2 3143.52   642.6  3152.7
   651.8 3156.53   681.7 3173.94     699 3183.16   707.7 3186.47   721.5 3194.93
#Mann= 10 ,-1,0
       0     .06       0      60      .1       0     170     .06       0
     190      .1       0   199.5    .045       0   230.6      .1       0
     270     .06       0     380      .1       0     450     .06       0
     700      .1       0
Bank Sta=199.5,230.6
XS Rating Curve= 0 ,0
Exp/Cntr=0.3,0.1

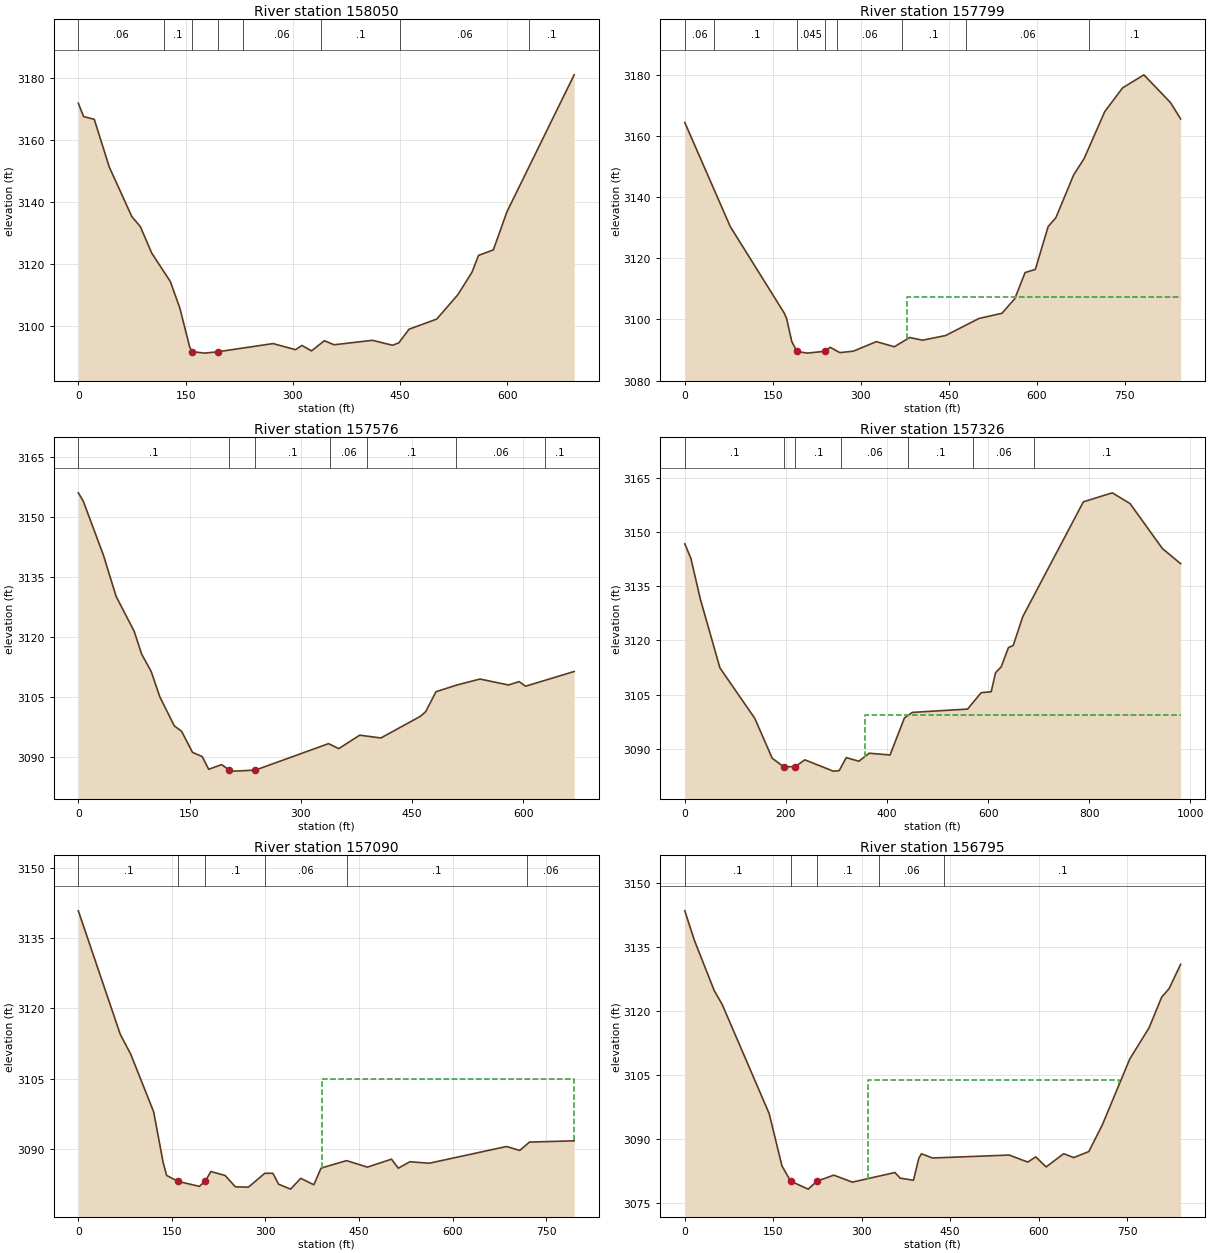
Type RM Length L Ch R = 1 ,158050  ,250.3,250.3,250.3
XS GIS Cut Line= 2
 2341988.7694316637023.7872626672342303.46914052636405.901248816
#Sta/Elev= 30
       0 3171.75     7.4 3167.47    22.3 3166.59    43.3 3151.24    74.7 3135.36
    86.8 3132.06   102.6 3123.59   128.6 3114.46   142.1  3105.8   155.6 3093.45
   159.1 3091.86     177  3091.4     196 3091.87   272.3 3094.47   303.7 3092.51
   312.7 3093.87   326.1 3092.12   344.1 3095.39   357.6 3094.09   411.4 3095.52
   439.4 3093.93   448.2 3094.71   462.5 3099.09   501.2 3102.34   530.9 3110.23
   550.6 3117.45   559.6 3122.82   580.4  3124.6   599.3 3136.81   693.4  3180.9
#Mann= 8 ,-1,0
       0     .06       0     120      .1       0   159.1    .045       0
     196      .1       0     230     .06       0     340      .1       0
     450     .06       0     630      .1       0
Bank Sta=159.1,196
XS Rating Curve= 0 ,0
Exp/Cntr(USF)=0,0
Exp/Cntr=0.3,0.1

Type RM Length L Ch R = 1 ,157799  ,223.1,223.1,223.1
XS GIS Cut Line= 2
2342214.44250869637156.1035799082342556.11955108636382.453025011
#Sta/Elev= 30
       0 3164.48    77.5 3130.43   169.4 3102.15   173.7 3100.29   182.5 3092.75
   191.2 3089.56   208.7 3088.97   239.3 3089.59   248.1 3090.88   264.4 3089.13
   287.4 3089.61   326.8 3092.73   357.4 3091.05   383.6 3094.09   405.5  3093.2
   444.8 3094.73   501.7 3100.32     541 3102.02   562.9 3106.82   580.4 3115.35
   597.9 3116.39   619.8 3130.44   632.9 3133.31   663.5 3147.43     681 3152.63
   716.3 3168.06   746.6 3175.81   783.1  3180.1   828.6 3170.96   845.7 3165.67
#Mann= 8 ,-1,0
       0     .06       0      50      .1       0   191.2    .045       0
   239.3      .1       0     260     .06       0     370      .1       0
     480     .06       0     690      .1       0
#XS Ineff= 2 , 0
                          379.19         3107.46
Permanent Ineff=
       F       F
Bank Sta=191.2,239.3
XS Rating Curve= 0 ,0
Exp/Cntr=0.3,0.1

Type RM Length L Ch R = 1 ,157576  ,250.1,250.1,250.1
XS GIS Cut Line= 2
2342372.54956442 637238.704137052342760.16749858636693.736348436
#Sta/Elev= 30
       0 3156.11     6.6 3154.06    33.9 3140.46      51 3130.14    75.3 3121.42
    85.3 3115.74    98.4 3111.28   109.9 3104.99   129.5  3097.7   139.3 3096.34
     154 3091.07   167.2 3089.99   175.8 3086.82   193.3 3087.99   203.1 3086.69
   210.2 3086.36   238.9 3086.62   337.5 3093.25   351.3    3092   379.5 3095.37
   408.1 3094.67   461.7 3100.13   468.6 3101.28   482.4 3106.26     510 3107.91
   541.8 3109.44   580.2 3107.95   594.6  3108.8   603.2 3107.64   668.8 3111.33
#Mann= 7 ,-1,0
       0      .1       0   203.1    .045       0   238.9      .1       0
     340     .06       0     390      .1       0     510     .06       0
     630      .1       0
Bank Sta=203.1,238.9
XS Rating Curve= 0 ,0
Exp/Cntr(USF)=0,0
Exp/Cntr=0.3,0.1

Type RM Length L Ch R = 1 ,157326  ,236.6,236.6,236.6
XS GIS Cut Line= 3
 2342555.8375483637356.5398690452342799.77723241637104.751468072
  2343283.932347636701.128785577
#Sta/Elev= 30
       0 3146.74      12 3142.75    30.9 3131.37    69.5 3112.39   138.5 3098.42
   172.9 3087.39   195.9 3084.99   218.9 3085.08   237.4 3086.94   293.7 3083.81
   305.4 3083.94   319.4 3087.55   344.4 3086.55   364.8 3088.77   406.1 3088.28
   434.4 3098.51     450 3100.07   559.4 3100.99   586.3 3105.53   606.2  3105.8
   614.7 3111.04     626  3112.7   640.2    3118   649.8 3118.62   668.6 3126.58
   788.5 3158.38   845.8 3160.87   880.9 3157.89   944.8 3145.45   980.9 3141.26
#Mann= 7 ,-1,0
       0      .1       0   195.9    .045       0   218.9      .1       0
     310     .06       0  440.58      .1       0  570.58     .06       0
  690.58      .1       0
#XS Ineff= 2 , 0
                           355.7         3099.38
Permanent Ineff=
       F       F
Bank Sta=195.9,218.9
XS Rating Curve= 0 ,0
Exp/Cntr=0.3,0.1

Type RM Length L Ch R = 1 ,157090  ,295,295,295
XS GIS Cut Line= 2
2342735.99576427637484.6360489112343342.82929408636970.967832809
#Sta/Elev= 30
       0 3140.84    67.3 3114.44    84.1  3110.2   120.8 3097.89     136 3087.08
   141.6 3084.31   160.1 3083.04   194.1 3081.98   203.5  3083.1   212.6 3085.15
   235.3 3084.31   251.8 3081.89   272.7 3081.81     299 3084.78   311.9 3084.77
   321.1 3082.44   340.3 3081.39   356.6  3083.7   377.6 3082.32   389.2 3085.88
     430 3087.48   463.5 3086.09   502.1 3087.79     513 3085.86   531.6 3087.24
   562.6 3086.92   686.6  3090.5   707.7 3089.65   723.4 3091.44     795 3091.71
#Mann= 6 ,-1,0
       0      .1       0   160.1    .045       0   203.5      .1       0
     300     .06       0     430      .1       0     720     .06       0
#XS Ineff= 2 , 0
                           390.6         3104.97
Permanent Ineff=
       F       F
Bank Sta=160.1,203.5
XS Rating Curve= 0 ,0
Exp/Cntr(USF)=0,0
Exp/Cntr=0.3,0.1

Type RM Length L Ch R = 1 ,156795  ,247,247,247
XS GIS Cut Line= 3
2342871.86123079637695.033818315 2343408.6181457637416.710335496
2343630.37458104637335.543800324
#Sta/Elev= 30
       0 3143.57    16.4  3136.6    49.9 3124.85    63.4 3121.59   143.1 3095.95
   164.8 3083.66   179.6 3080.08   209.3 3078.22   224.2  3080.1   252.7  3081.5
   284.2 3079.86   356.3 3082.12   365.3  3080.8   387.8  3080.3   396.9 3085.49
   401.4 3086.52     420 3085.53   550.1 3086.22   581.6 3084.58   595.1 3085.79
   612.7 3083.43   642.5 3086.54   659.5 3085.63   685.1 3087.04     708  3093.3
   754.5 3108.76   787.3 3116.11   808.6 3123.28   821.4 3125.34   840.8 3131.02
#Mann= 5 ,-1,0
       0      .1       0   179.6    .045       0   224.2      .1       0
     330     .06       0     440      .1       0
#XS Ineff= 1 ,-1
   310.4  736.583103.816
Permanent Ineff=
       F
Bank Sta=179.6,224.2
XS Rating Curve= 0 ,0
Exp/Cntr=0.3,0.1

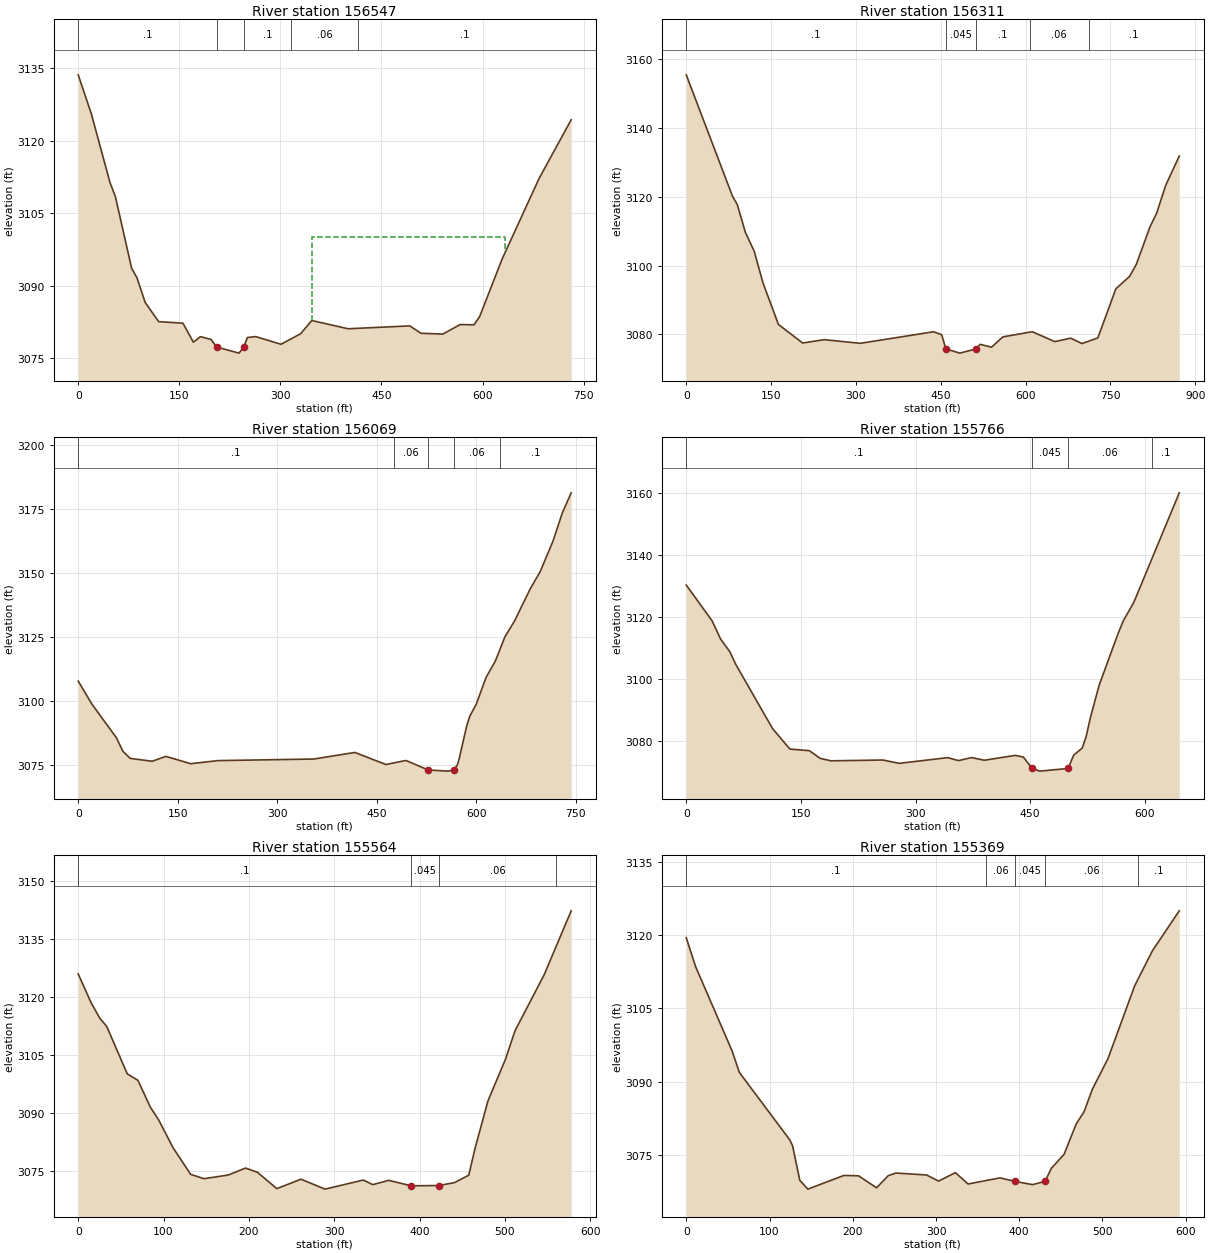
Type RM Length L Ch R = 1 ,156547  ,236.8,236.8,236.8
XS GIS Cut Line= 3
2342957.11681677637819.9043581032343112.12375492637832.141747957
2343666.88542831637677.134809804
#Sta/Elev= 30
       0 3133.64    19.4 3125.63    47.2 3111.35    55.2 3108.44    79.3 3093.61
    87.3 3091.63    99.4 3086.53   119.4 3082.57   155.5 3082.24   170.9 3078.31
   181.4 3079.46   197.1 3078.88   205.4 3077.31   238.6 3076.05   245.6  3077.3
   251.1 3079.28   263.5 3079.47   300.9 3077.88     330 3080.06   346.6  3082.8
   400.6 3081.09     492 3081.69   508.6 3080.16     541 3079.99   566.7 3081.96
   587.5 3081.91   595.8 3083.65     629 3095.51   683.8 3112.17   731.5 3124.34
#Mann= 5 ,-1,0
       0      .1       0   205.4    .045       0   245.6      .1       0
  315.49     .06       0  415.49      .1       0
#XS Ineff= 1 ,-1
  347.65  633.56 3100.17
Permanent Ineff=
       F
Bank Sta=205.4,245.6
XS Rating Curve= 0 ,0
Exp/Cntr(USF)=0,0
Exp/Cntr=0.3,0.1

Type RM Length L Ch R = 1 ,156311  ,241.8,241.8,241.8
XS GIS Cut Line= 4
2342767.88576596637926.4101505682343045.46312215638032.346780847
2343359.79671523638037.9422667752343620.17205073638035.462065478
#Sta/Elev= 30
       0 3155.46    81.7  3120.2    90.2 3117.78   104.6 3109.65   120.2 3104.18
   135.6 3095.04     163  3082.9   205.8  3077.5   244.1 3078.47   307.8 3077.41
   437.5 3080.77   451.8  3079.9   459.13075.791   483.8 3074.56   511.9 3075.76
   519.9 3077.11   539.9 3076.28   559.9 3079.28   611.9 3080.78   651.9  3077.9
   679.9 3078.91   699.9 3077.34   727.9 3078.97   759.9 3093.29   783.9 3096.83
   795.9 3100.34   819.9 3111.14   831.9 3115.23   847.9 3123.31   871.9 3131.84
#Mann= 5 ,-1,0
       0      .1       0   459.1    .045       0   511.9      .1       0
  607.11     .06       0  711.49      .1       0
Bank Sta=459.1,511.9
XS Rating Curve= 0 ,0
Exp/Cntr=0.3,0.1

Type RM Length L Ch R = 1 ,156069  ,302.4,302.4,302.4
XS GIS Cut Line= 3
 2342820.4659634638038.1378105032343116.20288487638117.680844555
2343479.24545055638360.389076663
#Sta/Elev= 30
       0 3107.75    20.4 3098.87    57.7 3085.57    67.5 3080.29    78.4 3077.56
   111.5 3076.45   132.2 3078.35   169.5 3075.49   210.9  3076.7   354.9 3077.31
   416.9 3079.88   463.7 3075.18   493.9 3076.75   527.5 3073.04   557.2 3072.59
     566 3073.06   571.2 3074.92     574 3077.31   585.3 3090.07   590.1 3094.03
   599.7 3098.66   614.8 3109.27   628.6 3115.55     643    3125   657.5  3131.2
   681.5 3143.93     696 3150.39   715.4 3162.33   729.6 3173.47   742.9 3181.26
#Mann= 5 ,-1,0
       0      .1       0  476.25     .06       0   527.5    .045       0
     566     .06       0  636.25      .1       0
Bank Sta=527.5,566
XS Rating Curve= 0 ,0
Exp/Cntr(USF)=0,0
Exp/Cntr=0.3,0.1

Type RM Length L Ch R = 1 ,155766  ,202.2,202.2,202.2
XS GIS Cut Line= 3
2342728.54966613638061.0031669372343110.56983306638455.387499189
2343170.21345003638530.602074194
#Sta/Elev= 30
       0 3130.39    33.8 3118.84    45.1 3112.88      57 3108.86    64.9 3104.71
     113 3083.99   135.6  3077.4   161.1 3076.88   175.2  3074.4   189.4  3073.6
   257.3 3073.86   278.7 3072.78   342.1 3074.63   356.3 3073.67   373.2 3074.65
   390.2 3073.79   430.6 3075.36   441.1  3074.8   452.5  3071.2   462.5 3070.27
   499.6 3071.13     507 3075.45   518.2 3077.73   523.2 3081.39   528.8 3087.54
   540.4 3098.12   564.5 3114.36   571.8 3118.79   585.7 3124.83   645.1 3160.19
#Mann= 4 ,-1,0
       0      .1       0   452.5    .045       0   499.6     .06       0
  609.07      .1       0
Bank Sta=452.5,499.6
XS Rating Curve= 0 ,0
Exp/Cntr=0.3,0.1

Type RM Length L Ch R = 1 ,155564  ,195,195,195
XS GIS Cut Line= 2
2342592.66697924638199.3138032122342998.34176864638610.584106954
#Sta/Elev= 30
       0 3126.07    15.1 3118.63    25.1 3114.68    33.5 3112.44    57.5  3100.2
      70 3098.52    84.7 3091.52    94.3 3088.29   111.3 3081.04   131.8 3074.19
   147.4 3073.07   175.9 3074.02   196.1 3075.82   210.1 3074.72   232.8  3070.5
   261.1 3072.94   289.2 3070.37   334.1 3072.72   345.3 3071.53   363.8 3072.64
   390.3 3071.23   422.4  3071.3   440.9 3072.05   457.7 3073.98   464.8 3080.72
   480.2 3093.22   500.5 3103.87   511.9 3111.36   546.1 3125.87   577.7 3142.39
#Mann= 4 ,-1,0
       0      .1       0   390.3    .045       0   422.4     .06       0
     560      .1       0
Bank Sta=390.3,422.4
XS Rating Curve= 0 ,0
Exp/Cntr(USF)=0,0
Exp/Cntr=0.3,0.1

Type RM Length L Ch R = 1 ,155369  ,297,297,297
XS GIS Cut Line= 3
2342414.69720403638398.2407774172342832.54831014638677.241740497
2342911.03797101638720.894258058
#Sta/Elev= 30
       0 3119.45    11.4 3113.47    55.1  3096.3    63.7 3091.94   124.3 3078.13
   127.7 3076.92   136.4 3069.85   146.1 3068.05   189.4 3070.85     207 3070.77
   228.6 3068.32   242.6  3070.8   251.9 3071.34   288.7 3070.94   303.1 3069.69
   323.3 3071.42   338.5  3069.1   376.9 3070.35   395.4 3069.61   415.9 3068.97
  430.98 3069.63   438.7 3072.34   453.9 3075.18   468.3 3081.33   477.9 3083.89
   487.7 3088.42   506.6 3094.74   538.6  3109.6   559.9 3116.76   592.2 3124.95
#Mann= 5 ,-1,0
       0      .1       0     360     .06       0   395.4    .045       0
  430.98     .06       0  542.44      .1       0
Bank Sta=395.4,430.98
XS Rating Curve= 0 ,0
Exp/Cntr=0.3,0.1

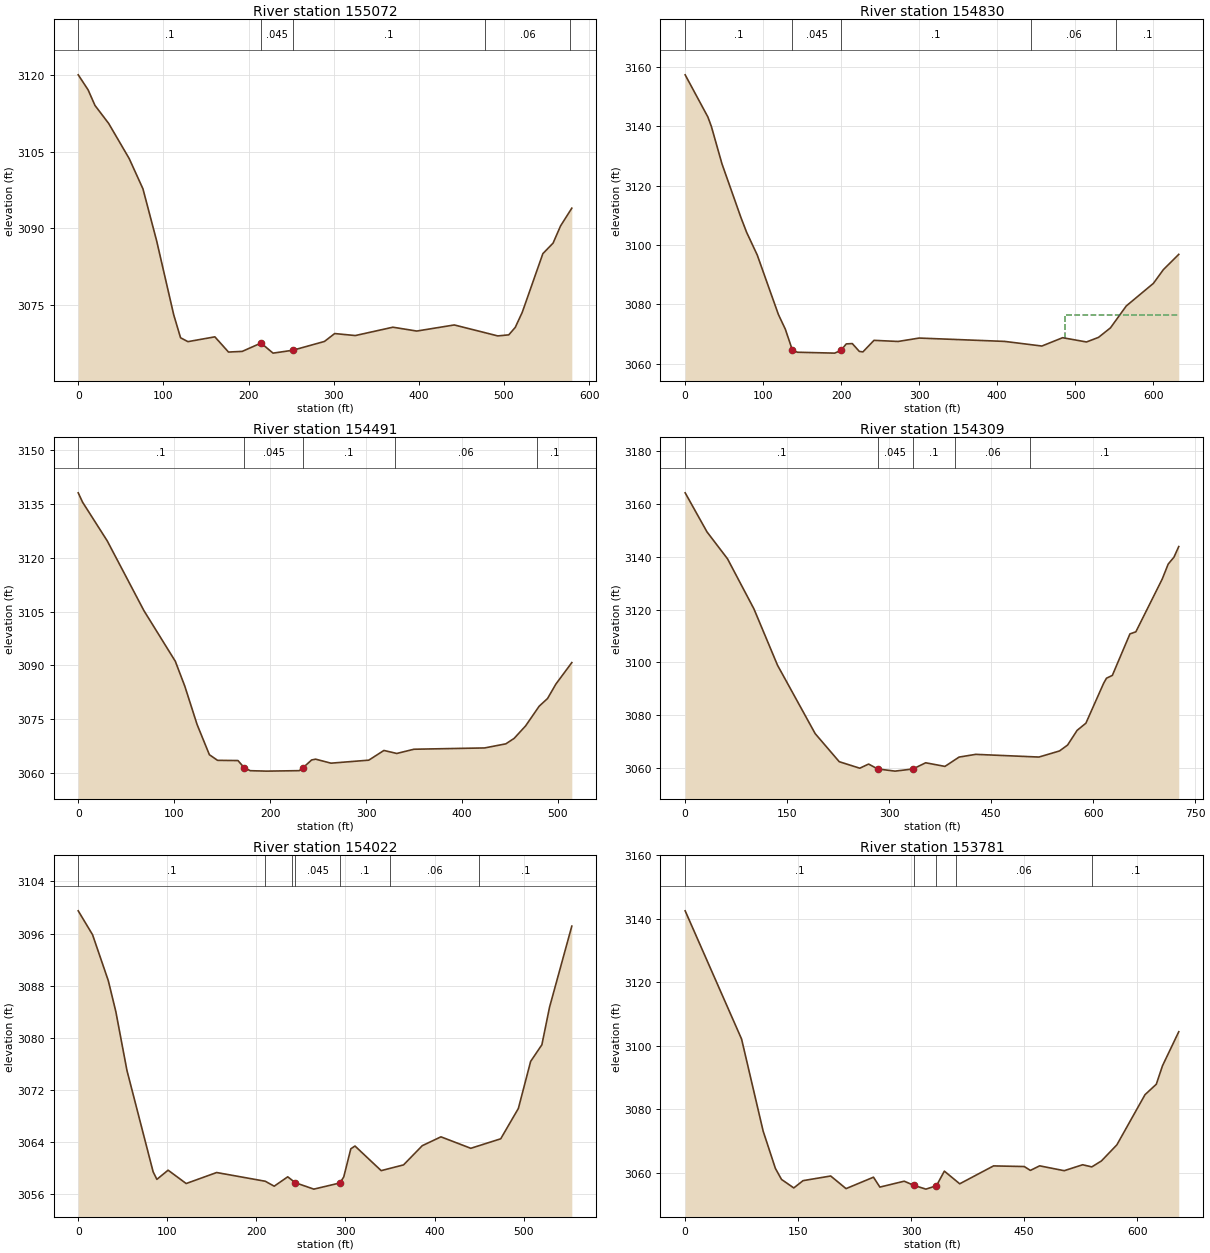
Type RM Length L Ch R = 1 ,155072  ,242.4,242.4,242.4
XS GIS Cut Line= 4
2342296.59324231638763.2913601692342661.56951265638801.519185165
2342712.04596777638798.5499819222342874.17890338638802.279775261
#Sta/Elev= 30
       0 3119.99    11.6 3117.06    19.7 3114.01    35.8 3110.49    59.9 3103.63
      76 3097.74    92.1 3087.59   112.2 3073.12   120.2 3068.66   128.8  3067.9
   160.5 3068.84   176.5 3065.87   192.6    3066   214.73067.624   228.8 3065.66
   251.93066.216   289.2 3067.94   301.2 3069.48   325.4 3069.09   369.6 3070.72
   397.6 3069.97   441.7 3071.16   492.8 3069.02   505.7 3069.23   513.3 3070.69
   521.5 3073.63   545.7 3085.08   557.7 3087.14   566.5  3090.5   579.7 3093.96
#Mann= 5 ,-1,0
       0      .1       0   214.7    .045       0   251.9      .1       0
  477.54     .06       0  577.54      .1       0
Bank Sta=214.7,251.9
XS Rating Curve= 0 ,0
Exp/Cntr(USF)=0,0
Exp/Cntr=0.3,0.1

Type RM Length L Ch R = 1 ,154830  ,338.4,338.4,338.4
XS GIS Cut Line= 3
2342370.39096128639106.3075935542342665.19247701638951.683189812
2342942.34386948638836.856390037
#Sta/Elev= 30
       0 3157.31    29.1 3143.11    33.6 3139.91    47.2 3127.29    71.3 3109.36
    78.8 3104.22    92.4 3096.59   119.5 3076.56   128.5 3071.52   137.5 3064.49
     144  3063.8   191.7  3063.5   199.7 3064.41   206.6 3066.61   214.3 3066.72
   223.3 3064.08   227.9 3063.91   242.1 3067.81     273 3067.43   300.1 3068.58
   409.7 3067.45   457.4 3065.89     484  3068.7   514.6 3067.26     530 3068.81
   545.3 3072.01   565.6  3079.4   600.4 3087.02   613.2 3091.65   632.9 3096.79
#Mann= 5 ,-1,0
       0      .1       0   137.5    .045       0   199.7      .1       0
  442.89     .06       0  552.89      .1       0
#XS Ineff= 2 , 0
                          486.72         3076.46
Permanent Ineff=
       F       F
Bank Sta=137.5,199.7
XS Rating Curve= 0 ,0
Exp/Cntr=0.3,0.1

Type RM Length L Ch R = 1 ,154491  ,182.8,182.8,182.8
XS GIS Cut Line= 3
2342750.61147872639329.4956116532342866.89742646639012.023826513
2342936.10180294638849.903608818
#Sta/Elev= 30
       0 3138.14     4.6  3135.5    30.2 3124.75    68.5 3105.25   101.2 3091.12
   111.1 3084.16   123.9 3073.47   136.7 3065.05   145.2 3063.48   166.5 3063.42
   172.9 3061.44   179.3 3060.59   196.3 3060.47   230.4  3060.6  234.34 3061.43
   243.2 3063.58   247.4 3063.81   263.4 3062.69   302.8 3063.53   318.6 3066.24
     332  3065.4   349.9 3066.58   423.5 3066.94   445.6 3068.08   454.3 3069.61
   466.2 3073.08   480.4 3078.59   489.1 3080.73   497.8 3084.76   514.4 3090.76
#Mann= 5 ,-1,0
       0      .1       0   172.9    .045       0  234.34      .1       0
     330     .06       0   478.1      .1       0
Bank Sta=172.9,234.34
XS Rating Curve= 0 ,0
Exp/Cntr(USF)=0,0
Exp/Cntr=0.3,0.1

Type RM Length L Ch R = 1 ,154309  ,286.4,286.4,286.4
XS GIS Cut Line= 3
2342884.46316694639454.8797604912343034.86881451639087.108630651
2343158.77563552638782.652703223
#Sta/Elev= 30
       0 3164.22    32.1 3149.43    62.3 3139.23   101.2 3120.24   135.8 3098.96
   191.2 3073.05   226.6 3062.41   256.8 3059.95   269.8 3061.51   283.3 3059.66
   308.7 3058.84  334.88 3059.65   353.8    3062   382.1 3060.63   402.9 3064.16
   427.4 3065.19   520.3 3064.17   550.6 3066.48   562.5 3068.72   576.5 3074.28
   589.4 3076.98   615.4 3092.05   619.7 3094.03   628.3 3095.08   654.2  3110.8
   662.9 3111.59   701.7 3131.58   710.4 3137.21     719 3139.88     726 3143.88
#Mann= 5 ,-1,0
       0      .1       0   283.3    .045       0  334.88      .1       0
  397.34     .06       0  507.34      .1       0
Bank Sta=283.3,334.88
XS Rating Curve= 0 ,0
Exp/Cntr=0.3,0.1

Type RM Length L Ch R = 1 ,154022  ,241.3,241.3,241.3
XS GIS Cut Line= 2
2343196.22168504 639413.371722092343363.46601305638885.124393385
#Sta/Elev= 30
       0 3099.49    16.1 3095.82    33.8 3088.75    42.2 3084.03    54.7 3074.98
    84.1 3059.41    88.3 3058.25   100.9 3059.66   121.2 3057.61   155.4  3059.3
     210 3057.96     220  3057.2   235.2 3058.64   243.6 3057.74   264.5 3056.75
   293.9  3057.7   298.1 3058.63     306 3062.94   310.7 3063.37   340.1 3059.59
   365.2 3060.47   386.2 3063.42   407.2 3064.78   440.7 3063.02   474.3 3064.48
   494.1 3069.14   507.9 3076.37   520.5 3078.92   529.1 3084.69   554.1 3097.14
#Mann= 7 ,-1,0
       0      .1       0     210     .08       0     240      .1       0
   243.6    .045       0   293.9      .1       0     350     .06       0
     450      .1       0
Bank Sta=243.6,293.9
XS Rating Curve= 0 ,0
Exp/Cntr(USF)=0,0
Exp/Cntr=0.3,0.1

Type RM Length L Ch R = 1 ,153781  ,250.3,250.3,250.3
XS GIS Cut Line= 2
2343447.56764976639530.6415364842343575.74028214638887.979508686
#Sta/Elev= 30
       0 3142.52    74.9  3102.1   103.5 3073.11   119.8 3061.32   127.9 3057.86
   144.2 3055.18   156.5 3057.47   193.2 3058.94   213.6 3054.96     250 3058.56
   258.5 3055.44   290.8  3057.3   303.3 3056.02   319.6  3054.8   333.63055.863
   344.1 3060.47   364.5 3056.48   409.4 3062.12   450.2 3061.92   458.3  3060.7
   470.6 3062.14   503.2 3060.61   527.7 3062.48   539.9 3061.81   552.7  3063.7
   573.1 3068.75   610.5 3084.57   625.5 3087.87   633.7 3093.68   655.3 3104.41
#Mann= 5 ,-1,0
       0      .1       0   303.3    .045       0   333.6      .1       0
     360     .06       0     540      .1       0
Bank Sta=303.3,333.6
XS Rating Curve= 0 ,0
Exp/Cntr=0.3,0.1

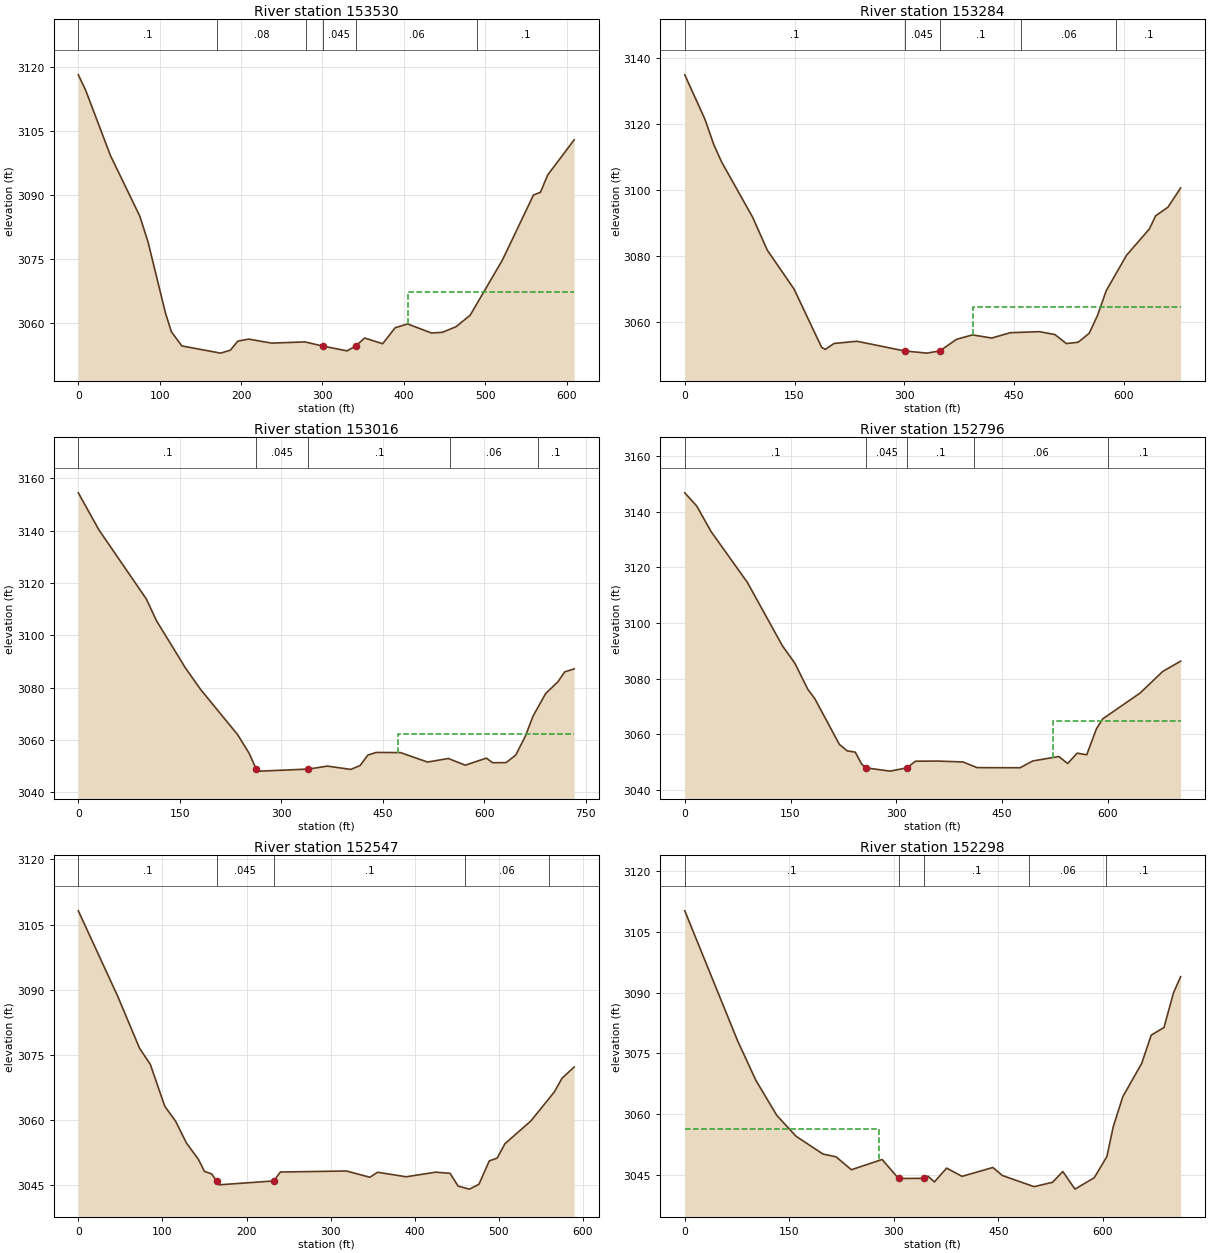
Type RM Length L Ch R = 1 ,153530  ,246.2,246.2,246.2
XS GIS Cut Line= 2
2343638.44032572639538.9902437122343868.70840542638974.833448456
#Sta/Elev= 30
       0 3118.24     8.9 3114.68    39.5 3099.29    75.4 3085.15    85.6 3079.07
     107 3062.43   114.3 3057.99   127.2 3054.65   174.8 3052.96   186.8 3053.65
     196 3055.77   209.3 3056.25   237.5 3055.31   278.5 3055.59   300.3 3054.62
   330.3 3053.48  340.96 3054.65   351.9  3056.5     374 3055.17   389.3 3058.91
   404.6 3059.81     434 3057.68   447.6 3057.85   464.2 3059.17   481.5 3061.85
   521.2 3074.82   559.3 3090.04   567.9  3090.7   576.8 3094.75   609.3 3102.99
#Mann= 6 ,-1,0
       0      .1       0     170     .08       0     280     .06       0
   300.3    .045       0  340.96     .06       0     490      .1       0
#XS Ineff= 2 , 0
                           404.8         3067.41
Permanent Ineff=
       F       F
Bank Sta=300.3,340.96
XS Rating Curve= 0 ,0
Exp/Cntr(USF)=0,0
Exp/Cntr=0.3,0.1

Type RM Length L Ch R = 1 ,153284  ,268.3,268.3,268.3
XS GIS Cut Line= 2
2343698.17624878639607.1477963872344209.87757679639162.571677554
#Sta/Elev= 30
       0 3134.79    27.4 3121.44    39.7 3113.68    50.3 3108.47    92.7 3091.77
   112.8  3081.8   149.4 3070.02   187.1 3052.42   192.1  3051.8   204.1 3053.59
   235.3 3054.26   300.5 3051.33   331.2 3050.67   348.7 3051.35   371.4 3054.83
   393.3 3056.18   419.6 3055.23   445.1 3056.84   484.8 3057.16     506 3056.29
   521.7 3053.56   537.8 3053.96   552.9 3056.66   564.2 3062.02   576.3  3069.6
   603.9 3080.23   635.1 3088.18   643.8 3092.19   660.6 3094.79   677.9  3100.6
#Mann= 5 ,-1,0
       0      .1       0   300.5    .045       0   348.7      .1       0
     460     .06       0     590      .1       0
#XS Ineff= 2 , 0
                          393.73         3064.75
Permanent Ineff=
       F       F
Bank Sta=300.5,348.7
XS Rating Curve= 0 ,0
Exp/Cntr=0.3,0.1

Type RM Length L Ch R = 1 ,153016  ,220.2,220.2,220.2
XS GIS Cut Line= 2
2343818.81698815639834.5009459882344382.97378341639366.289183939
#Sta/Elev= 30
       0 3154.47    30.3 3140.37   100.5 3113.94   115.5 3105.65   158.1 3087.68
   180.9 3079.32   235.7 3062.04   252.6 3054.95  263.03 3048.97   268.9 3048.16
   340.3 3048.95   368.3 3050.08   402.9 3048.81   416.6  3050.3     428 3054.28
   440.5  3055.3   476.3 3055.24   516.4 3051.62     547 3052.99     572 3050.44
   603.3 3053.12   612.6 3051.37   632.5 3051.42   646.7 3054.27   660.9 3061.49
   672.2 3069.12     691 3077.82   709.2 3082.32   719.1 3086.07   733.1 3087.21
#Mann= 5 ,-1,0
       0      .1       0  263.03    .045       0   340.3      .1       0
     550     .06       0     680      .1       0
#XS Ineff= 2 , 0
                          472.13         3062.46
Permanent Ineff=
       F       F
Bank Sta=263.03,340.3
XS Rating Curve= 0 ,0
Exp/Cntr(USF)=0,0
Exp/Cntr=0.3,0.1

Type RM Length L Ch R = 1 ,152796  ,249.1,249.1,249.1
XS GIS Cut Line= 2
2343905.14593128 639960.442517182344530.67924554639638.901785577
#Sta/Elev= 30
       0 3146.89    16.9 3142.15    37.3 3132.94    88.9 3114.58   138.3 3091.87
   156.2 3085.51   174.3 3076.21   184.6 3072.68   219.3 3056.27   230.4 3053.97
   241.8 3053.49   250.8 3049.23   257.2 3047.83   291.2 3046.66  315.01 3047.84
   327.2 3050.23   358.7 3050.28   394.7 3049.96   414.6 3047.92   475.6 3047.88
   493.6 3050.32   530.5 3051.92   543.1 3049.41   556.6 3053.14   570.1 3052.54
   583.9 3061.91   592.8 3065.48   645.9  3074.8     678 3082.58   703.3 3086.26
#Mann= 5 ,-1,0
       0      .1       0   257.2    .045       0  315.01      .1       0
     410     .06       0     600      .1       0
#XS Ineff= 2 , 0
                          522.15         3064.74
Permanent Ineff=
       F       F
Bank Sta=257.2,315.01
XS Rating Curve= 0 ,0
Exp/Cntr=0.3,0.1

Type RM Length L Ch R = 1 ,152547  ,248.9,248.9,248.9
XS GIS Cut Line= 2
2344016.38446737640142.1609544562344565.57383745639928.011640338
#Sta/Elev= 30
       0 3108.16      47 3088.44    72.8 3076.56    85.6 3072.84   102.8 3063.21
   115.7 3059.77   128.6 3054.74   142.7 3051.04     150 3048.23   158.6 3047.65
   164.3 3046.02   167.4 3045.15   232.3 3046.04   240.2 3048.09   318.8 3048.33
   346.6 3046.89   355.8 3048.04   389.8    3047   424.8 3048.06     442 3047.79
   451.6 3044.84   465.1 3044.16   476.3 3045.28   488.6 3050.66   497.9 3051.29
   507.2  3054.6   538.1 3059.85   565.9  3066.5   575.1 3069.67   589.5 3072.24
#Mann= 5 ,-1,0
       0      .1       0   164.3    .045       0   232.3      .1       0
     460     .06       0     560      .1       0
Bank Sta=164.3,232.3
XS Rating Curve= 0 ,0
Exp/Cntr(USF)=0,0
Exp/Cntr=0.3,0.1

Type RM Length L Ch R = 1 ,152298  ,201.1,201.1,201.1
XS GIS Cut Line= 3
2343999.33361558640427.8513996442344393.43577239640244.754128139
2344637.23085663640113.199057346
#Sta/Elev= 30
       0 3110.22    75.9 3078.04     102 3068.31   132.1 3059.62   159.7 3054.47
   198.4 3050.07     217 3049.39   239.1  3046.2   283.2 3048.73   306.8 3044.03
   342.9 3044.07     349 3044.61   358.2 3043.18   375.8  3046.6   397.9 3044.56
   442.1 3046.75   455.9 3044.76   501.3 3042.01   527.8 3043.09   542.5 3045.76
     560  3041.4   587.7 3044.23   605.8 3049.47   614.9 3056.82   628.6 3064.25
   655.8 3072.52   669.4 3079.48   687.7 3081.37   701.3  3089.9   711.6 3093.94
#Mann= 5 ,-1,0
       0      .1       0   306.8    .045       0   342.9      .1       0
  494.56     .06       0  604.56      .1       0
#XS Ineff= 2 , 0
          279.19 3056.17
Permanent Ineff=
       F       F
Bank Sta=306.8,342.9
XS Rating Curve= 0 ,0
Exp/Cntr=0.3,0.1