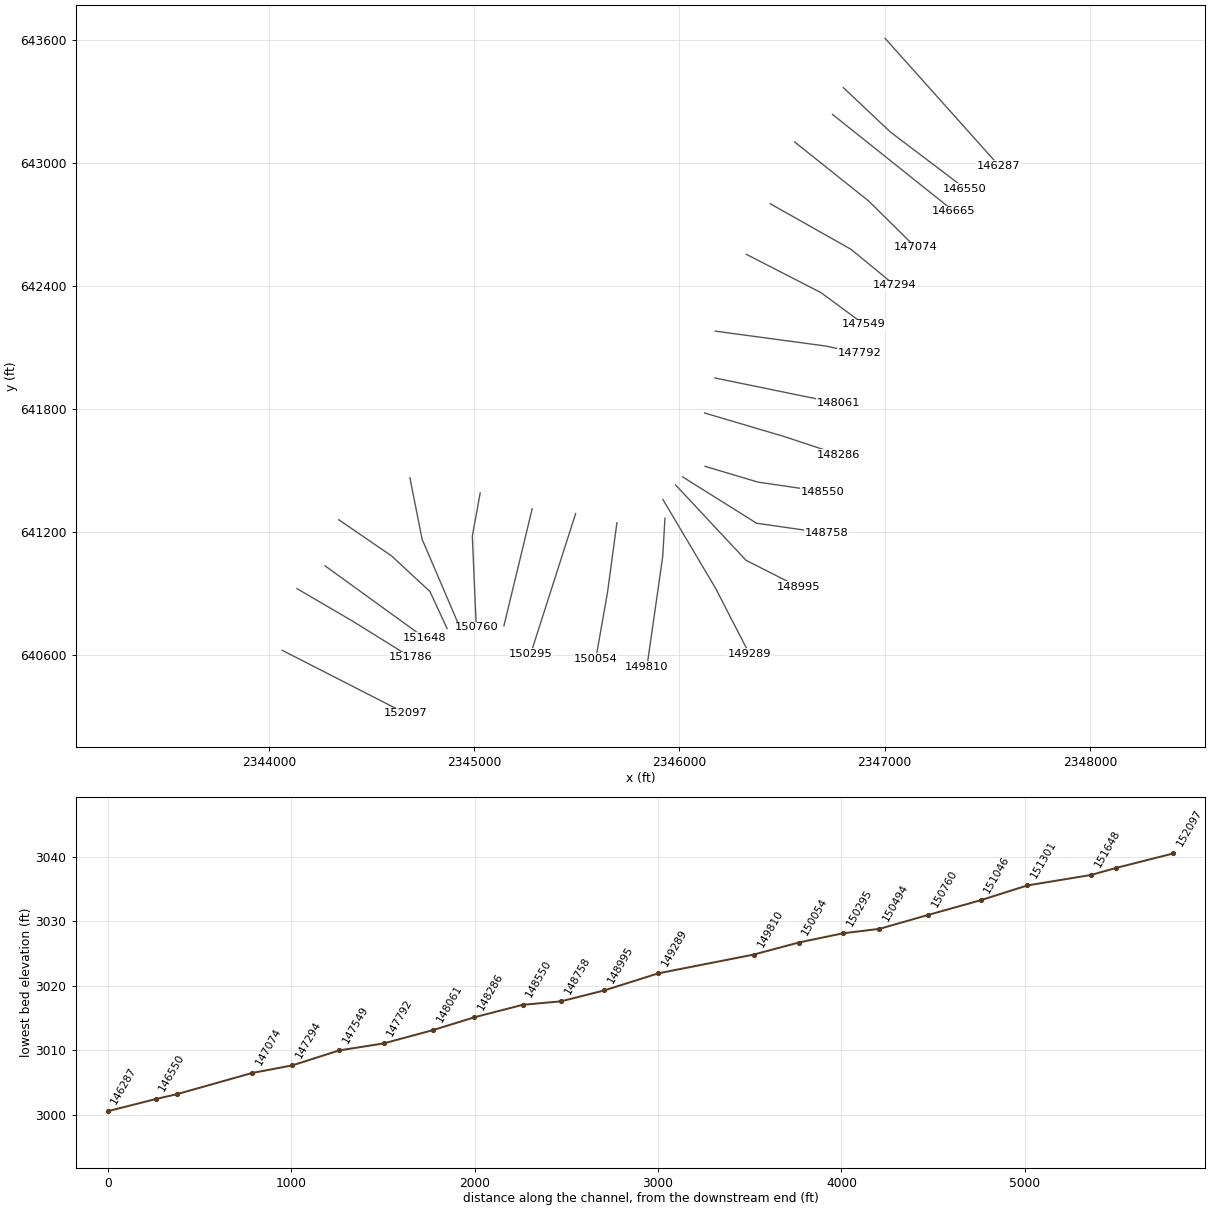
HEC-RAS study LAURELFK.prj: LAURELFK

--- LAURELFK.g01 (geometry) --- (continued)

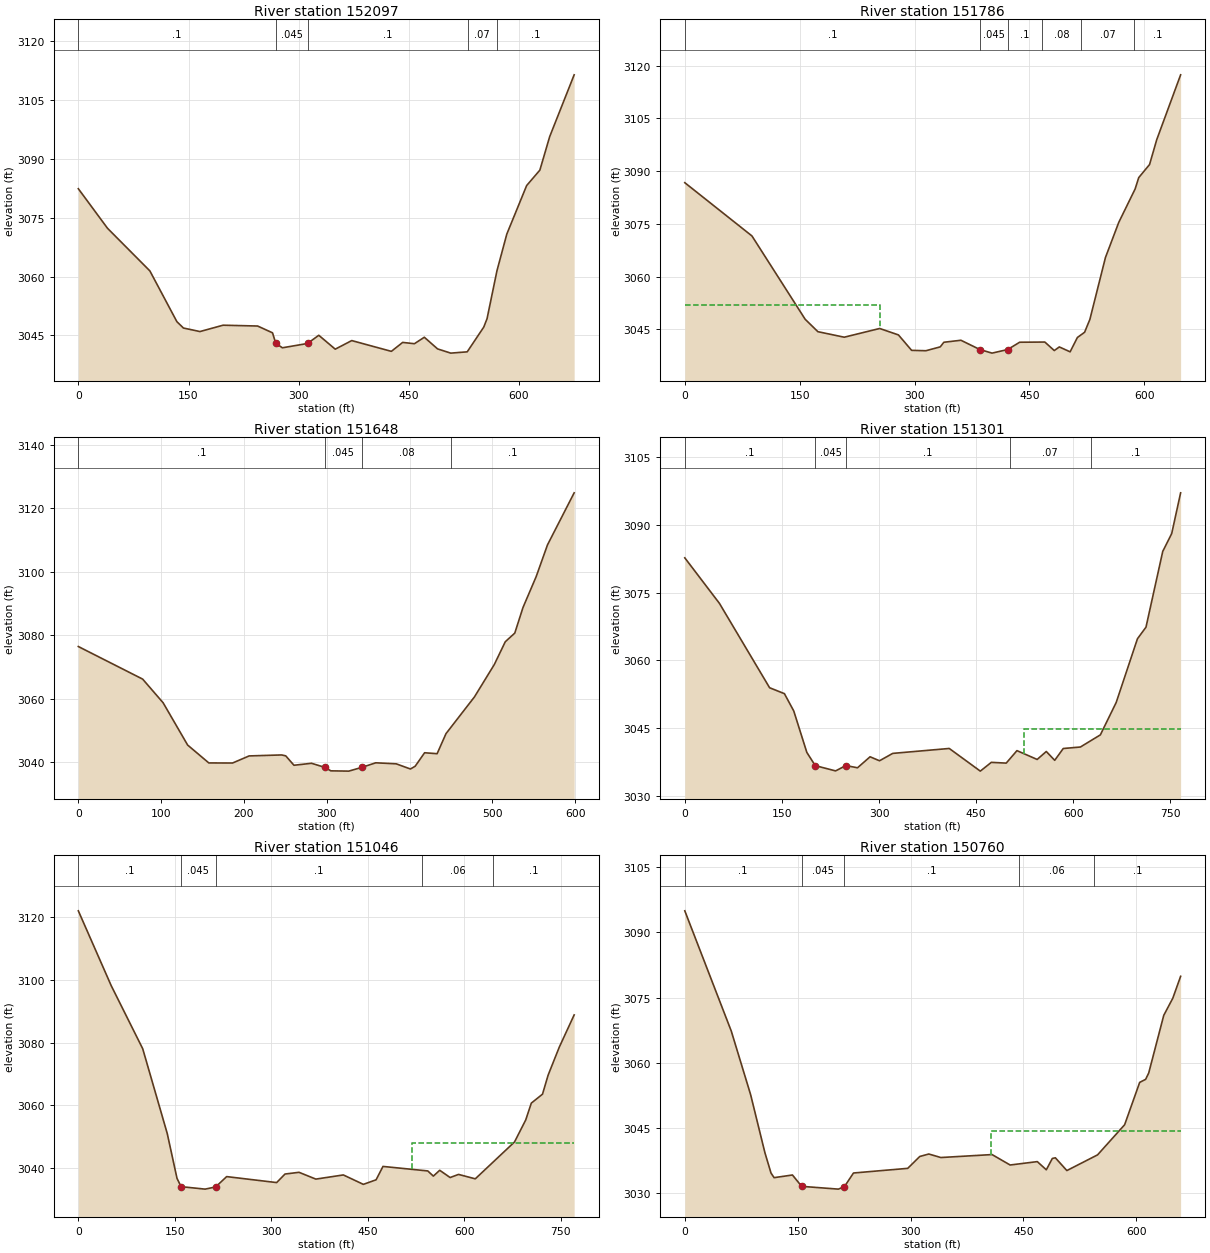
Type RM Length L Ch R = 1 ,152097  ,311,311,311
XS GIS Cut Line= 2
2344064.74076411640622.2699006222344665.74045211640314.862014228
#Sta/Elev= 30
       0  3082.4    39.8  3072.3    97.4 3061.45   134.2  3048.5   143.1 3046.88
   165.6 3045.98   197.1  3047.6   244.1 3047.39   264.4 3045.66   268.9 3042.95
   277.9 3041.84  312.04 3042.94   327.4 3045.03   349.8 3041.49   372.3 3043.68
   426.2 3040.93   441.6 3043.21   457.6 3042.88   471.1 3044.53   489.1 3041.56
   507.1 3040.48   529.5 3040.81     552 3047.11   556.5 3049.26     570 3061.49
   583.4 3070.83   610.4  3083.2   628.4 3087.14   641.8 3095.69   675.1 3111.44
#Mann= 5 ,-1,0
       0      .1       0   268.9    .045       0  312.04      .1       0
     530     .07       0     570      .1       0
Bank Sta=268.9,312.04
XS Rating Curve= 0 ,0
Exp/Cntr(USF)=0,0
Exp/Cntr=0.3,0.1

Type RM Length L Ch R = 1 ,151786  ,138.1,138.1,138.1
XS GIS Cut Line= 3
2344136.49550422640923.2159216472344410.05205073640763.172399351
2344690.59835187640588.410715234
#Sta/Elev= 30
       0 3086.72    87.7 3071.57   157.2 3047.87   173.8 3044.34   208.2 3042.77
   254.5 3045.25     279 3043.42   296.2 3039.03   314.8 3038.92   333.6 3040.02
   338.3 3041.33   360.6  3041.9   385.4 3039.26   401.2 3038.24   421.6 3039.26
   437.3 3041.34   470.2 3041.39   482.5 3038.97   489.1    3040   503.2 3038.61
   512.7 3042.69   522.1 3044.17     529 3047.83   549.3 3065.41   566.7 3075.42
   588.1 3084.94   592.8 3088.17   606.9 3091.87   616.3 3098.95   647.5  3117.4
#Mann= 6 ,-1,0
       0      .1       0   385.4    .045       0   421.6      .1       0
  466.93     .08       0  516.93     .07       0  586.93      .1       0
#XS Ineff= 2 , 0
          254.83 3052.04
Permanent Ineff=
       F       F
Bank Sta=385.4,421.6
XS Rating Curve= 0 ,0
Exp/Cntr=0.3,0.1

Type RM Length L Ch R = 1 ,151648  ,346.6,346.6,346.6
XS GIS Cut Line= 2
2344273.28426775641034.3552425782344758.22884359640683.081287001
#Sta/Elev= 30
       0  3076.4    77.7 3066.13   102.4 3058.68     132 3045.36   157.6 3039.72
   186.2 3039.69   206.3 3041.93   245.6 3042.24   250.5 3041.95   260.4 3038.99
   281.6 3039.61   297.9 3038.31   304.9 3037.23   326.6 3037.14  342.19 3038.31
   359.2 3039.76   383.9 3039.44   401.1 3037.81   406.8 3038.68   418.2 3042.93
   433.3 3042.63     444 3048.94   478.4 3060.53   502.4 3070.74   515.6  3077.9
   527.1 3080.63     537 3088.69   552.9 3098.41   566.6 3108.43   598.8 3124.83
#Mann= 4 ,-1,0
       0      .1       0   297.9    .045       0  342.19     .08       0
     450      .1       0
Bank Sta=297.9,342.19
XS Rating Curve= 0 ,0
Exp/Cntr(USF)=0,0
Exp/Cntr=0.3,0.1

Type RM Length L Ch R = 1 ,151301  ,255.3,255.3,255.3
XS GIS Cut Line= 4
 2344340.0837758641259.0998346852344597.42812217641082.704571091
2344784.18832363640909.3124313242344867.73361849640728.643169562
#Sta/Elev= 30
       0 3082.66    53.5  3072.6     131 3053.95   153.9 3052.64   168.3 3048.82
   188.5 3039.66   201.5 3036.74   232.9 3035.57   248.9 3036.75   266.8 3036.26
   286.2 3038.69   300.8 3037.81   321.2 3039.44   408.5 3040.53   456.5 3035.52
   473.5 3037.46   496.5 3037.29   513.1 3040.05   544.3  3038.1   558.4 3039.86
   571.4 3037.91   584.6 3040.52   611.1 3040.85   641.9 3043.53   666.4  3050.7
   699.2 3064.77   712.4 3067.34   738.3 3084.09   752.1 3088.01   765.9 3097.03
#Mann= 5 ,-1,0
       0      .1       0   201.5    .045       0   248.9      .1       0
     502     .07       0  626.84      .1       0
#XS Ineff= 2 , 0
                          524.53         3044.84
Permanent Ineff=
       F       F
Bank Sta=201.5,248.9
XS Rating Curve= 0 ,0
Exp/Cntr=0.3,0.1

Type RM Length L Ch R = 1 ,151046  ,285.8,285.8,285.8
XS GIS Cut Line= 3
2344686.73060484641463.3446750522344745.79436728641164.917243766
2344929.20289276640735.927811292
#Sta/Elev= 30
       0 3122.11    51.1 3098.22   100.1 3078.06   138.2    3051   153.4 3036.67
   159.7 3034.01   197.1 3033.22   213.5 3033.92   230.6 3037.22   308.3 3035.31
   321.3 3038.04   343.1 3038.59   369.2 3036.42     412 3037.75   443.1 3034.74
   462.9  3036.2   473.6 3040.47   543.2 3039.03   551.9 3037.38   561.8 3039.24
     578 3036.92     591 3037.92   617.1 3036.51   678.1 3048.29   695.5 3055.31
   704.2 3060.69   721.6 3063.55   730.3 3069.61   747.7 3078.58   770.8 3088.86
#Mann= 5 ,-1,0
       0      .1       0   159.7    .045       0   213.5      .1       0
  534.22     .06       0  644.22      .1       0
#XS Ineff= 2 , 0
                          519.16         3047.89
Permanent Ineff=
       F       F
Bank Sta=159.7,213.5
XS Rating Curve= 0 ,0
Exp/Cntr(USF)=0,0
Exp/Cntr=0.3,0.1

Type RM Length L Ch R = 1 ,150760  ,265.5,265.5,265.5
XS GIS Cut Line= 3
2345029.12107635641389.9486625372344990.73795261641179.332438916
2345010.05396261640734.873216956
#Sta/Elev= 30
       0 3094.98    61.8  3067.3    87.5 3052.68   106.5 3039.32   114.6 3034.64
   118.7 3033.59   143.1  3034.2   155.3 3031.59   204.1 3030.95   212.2 3031.53
   224.2 3034.66   296.3 3035.73   312.3 3038.46   324.3 3039.03   340.3 3038.22
   408.4  3038.9   432.4  3036.5   468.5 3037.28   480.5  3035.4   488.5 3038.01
   492.5 3038.16   507.8 3035.22   548.6 3038.83   584.6 3045.77   604.6 3055.51
   612.5 3056.21   616.6 3057.67   636.6 3070.94   648.6 3074.87     659 3079.91
#Mann= 5 ,-1,0
       0      .1       0   155.3    .045       0   212.2      .1       0
  444.09     .06       0  544.09      .1       0
#XS Ineff= 2 , 0
                          406.39         3044.33
Permanent Ineff=
       F       F
Bank Sta=155.3,212.2
XS Rating Curve= 0 ,0
Exp/Cntr=0.3,0.1

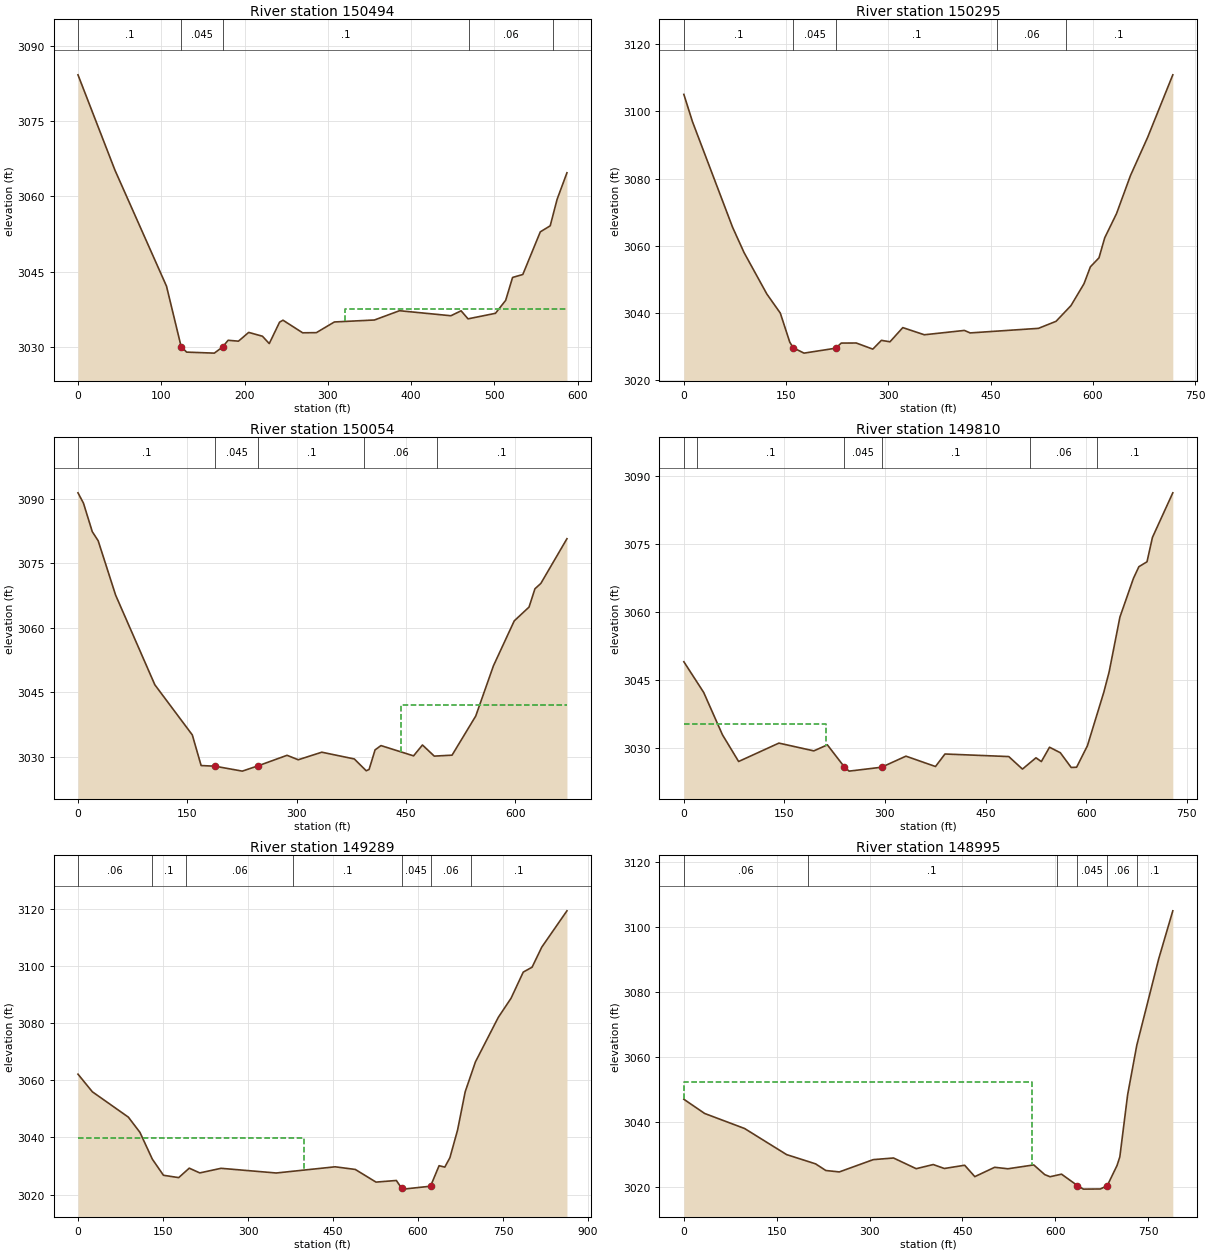
Type RM Length L Ch R = 1 ,150494  ,199.3,199.3,199.3
XS GIS Cut Line= 2
 2345282.3336518641312.5005904642345144.66301595640741.626353774
#Sta/Elev= 30
       0 3084.24    44.3 3065.28   106.3 3042.13   123.9 3030.08   130.5 3028.99
   163.7 3028.79   173.6    3030   180.3 3031.35   192.7 3031.17     205 3032.92
   221.5 3032.16   229.7 3030.69   242.1 3034.96   246.2 3035.35   269.8 3032.84
   286.3 3032.87   307.9    3035     356 3035.39   386.1 3037.24   447.8 3036.24
   460.1 3037.22   468.4 3035.62   501.3 3036.72   513.6  3039.3   521.9 3043.87
   534.2 3044.46   555.2 3052.95   567.1 3054.16   575.4 3059.45   587.2 3064.72
#Mann= 5 ,-1,0
       0      .1       0   123.9    .045       0   173.6      .1       0
     470     .06       0     570      .1       0
#XS Ineff= 2 , 0
                          320.15          3037.5
Permanent Ineff=
       F       F
Bank Sta=123.9,173.6
XS Rating Curve= 0 ,0
Exp/Cntr(USF)=0,0
Exp/Cntr=0.3,0.1

Type RM Length L Ch R = 1 ,150295  ,240.9,240.9,240.9
XS GIS Cut Line= 2
2345494.08613258 641289.228847812345275.41048566640606.030070793
#Sta/Elev= 30
       0 3105.05    12.7 3096.91    71.5 3065.53    88.3 3058.02   121.8 3045.67
   141.5 3040.01   155.4 3031.35   160.6 3029.67   176.3  3028.1   222.6 3029.56
     231 3031.09   252.9 3031.11   277.2 3029.29   289.8  3031.9   302.4 3031.47
   321.2 3035.69   352.8 3033.56   411.6 3034.85     420 3034.11   520.2 3035.47
     546 3037.56   567.9 3042.23     587 3048.73   596.4 3053.77     609 3056.44
   617.4 3062.39   634.7 3069.58   655.2 3080.92   680.4 3092.29   717.3 3110.87
#Mann= 5 ,-1,0
       0      .1       0   160.6    .045       0   222.6      .1       0
     460     .06       0     560      .1       0
Bank Sta=160.6,222.6
XS Rating Curve= 0 ,0
Exp/Cntr=0.3,0.1

Type RM Length L Ch R = 1 ,150054  ,244.3,244.3,244.3
XS GIS Cut Line= 3
2345695.34555938641244.5830767742345649.45534742640904.995508326
 2345592.5514846640581.928416179
#Sta/Elev= 30
       0 3091.37     7.5 3088.97    19.6 3082.34    27.7 3080.22    51.6  3067.6
   105.4 3046.75   156.8 3035.09   168.9 3027.97   188.13027.808   225.4 3026.67
   247.6 3027.94   286.8 3030.35   302.1 3029.31   334.4 3031.07     379  3029.5
   395.4 3026.75   399.3 3027.06   407.5 3031.61   415.6 3032.61   460.3 3030.22
   472.5 3032.75   488.7 3030.16   513.1 3030.38   545.6 3039.48   569.9 3051.17
   598.4  3061.6   618.7 3064.81   626.8 3069.06   634.9 3070.31   670.7  3080.7
#Mann= 5 ,-1,0
       0      .1       0   188.1    .045       0   247.6      .1       0
  392.67     .06       0  492.67      .1       0
#XS Ineff= 2 , 0
                          442.79         3041.94
Permanent Ineff=
       F       F
Bank Sta=188.1,247.6
XS Rating Curve= 0 ,0
Exp/Cntr(USF)=0,0
Exp/Cntr=0.3,0.1

Type RM Length L Ch R = 1 ,149810  ,520.6,520.6,520.6
XS GIS Cut Line= 3
2345929.38071409 641266.71457695     2345918.516641080.512682495
2345841.67961377640543.139967261
#Sta/Elev= 30
       0 3049.01    29.6 3042.22    57.6 3032.85    81.7 3026.94   141.8 3031.01
   193.9 3029.29   214.1 3030.62   239.53025.728   246.5 3024.81   294.9 3025.67
   331.3 3028.12   375.4 3025.83   389.5  3028.6   484.7 3028.03   505.1 3025.26
   525.3 3027.76   533.3 3026.92   545.5  3030.1   561.6 3028.88   577.8 3025.62
   585.9 3025.67     602 3030.42   626.4 3042.23   634.4 3046.75   650.5 3058.89
   670.7 3067.47   678.8 3070.04   690.9 3071.12     699 3076.51   729.4 3086.38
#Mann= 6 ,-1,0
       0     .06       0      20      .1       0   239.5    .045       0
   294.9      .1       0  516.52     .06       0  616.52      .1       0
#XS Ineff= 2 , 0
          211.65 3035.13
Permanent Ineff=
       F       F
Bank Sta=239.5,294.9
XS Rating Curve= 0 ,0
Exp/Cntr=0.3,0.1

Type RM Length L Ch R = 1 ,149289  ,293.8,293.8,293.8
XS GIS Cut Line= 3
2345919.26148039641358.0761860382346176.37325968640924.347332252
2346340.28371593640605.493749055
#Sta/Elev= 30
       0 3062.16    25.3    3056    88.9 3047.11   109.3 3041.78   131.2 3032.39
   150.8 3026.75   177.7 3025.93   196.3 3029.24   214.9 3027.58   252.4 3029.19
   349.8 3027.55   453.8 3029.72   489.3 3028.79   525.8 3024.36   561.7 3024.93
   570.83022.268   573.8  3021.9     6223022.917   637.1 3030.11   647.2 3029.61
   656.2 3032.91   669.7 3042.58   683.2 3056.02   701.2 3066.45   741.6 3082.07
   764.1 3088.76   785.6 3097.91   801.2 3099.63   818.3 3106.66   862.7 3119.37
#Mann= 7 ,-1,0
       0     .06       0     130      .1       0     190     .06       0
     380      .1       0   570.8    .045       0     622     .06       0
  694.21      .1       0
#XS Ineff= 2 , 0
          398.53 3039.72
Permanent Ineff=
       F       F
Bank Sta=570.8,622
XS Rating Curve= 0 ,0
Exp/Cntr=0.3,0.1

Type RM Length L Ch R = 1 ,148995  ,237.3,237.3,237.3
XS GIS Cut Line= 3
2345981.26908516641428.8501916732346323.91877524641061.745506803
2346580.49373737640931.281950342
#Sta/Elev= 30
       0 3046.95    33.6 3042.57    98.1 3037.94     166  3029.9   212.9 3027.04
   229.4    3025   251.2 3024.56     306 3028.35   338.8 3028.85   375.4 3025.56
   402.9 3026.83   420.9 3025.62   453.7 3026.62   470.1 3023.11   502.2 3025.99
   523.6 3025.53   565.3 3026.72   583.2 3023.72   591.7 3023.08   610.2 3023.87
   635.8 3020.37   645.6 3019.26     673 3019.31   684.1 3020.33   699.9 3026.54
   704.4  3029.2     717 3048.32   731.8 3063.58   767.2  3090.2     790    3105
#Mann= 6 ,-1,0
       0     .06       0     200      .1       0  602.17     .06       0
   635.8    .045       0   684.1     .06       0  732.17      .1       0
#XS Ineff= 2 , 0
          562.13 3052.16
Permanent Ineff=
       F       F
Bank Sta=635.8,684.1
XS Rating Curve= 0 ,0
Exp/Cntr(USF)=0,0
Exp/Cntr=0.3,0.1

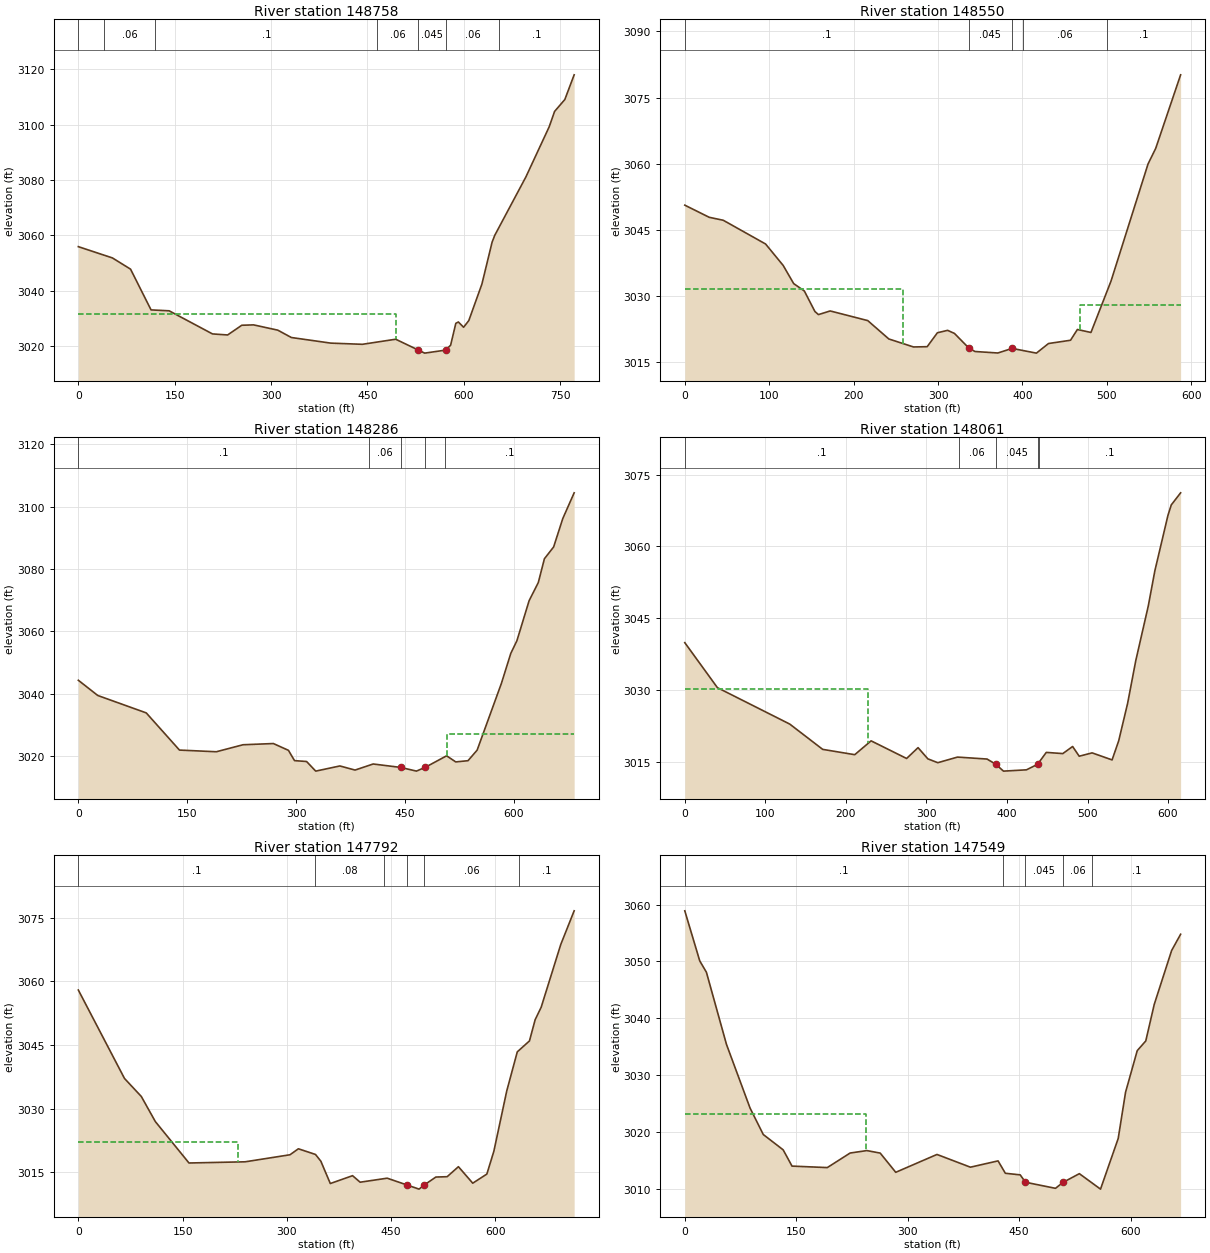
Type RM Length L Ch R = 1 ,148758  ,208.3,208.3,208.3
XS GIS Cut Line= 3
2346015.21188778641468.2477034682346375.73519671641242.351406899
2346718.48652098641192.830037097
#Sta/Elev= 30
       0 3055.96    53.1 3051.89    81.3 3047.84   113.2 3033.15   141.4 3032.82
   208.8 3024.49   232.4 3024.11   254.4 3027.61   272.8 3027.75   310.5 3025.84
   331.6 3023.19   392.9 3021.17   442.1 3020.74     494 3022.57529.09523018.681
   539.1 3017.56   571.7 3018.65   579.5 3020.41   587.6 3028.31   591.6 3028.79
   599.7 3026.89   607.8 3029.29   628.2 3042.46   644.1 3057.61   648.2 3060.04
   696.7 3081.12     733 3099.22   741.3 3104.71   757.3 3109.03   771.8 3117.93
#Mann= 7 ,-1,0
       0      .1       0      40     .06       0     120      .1       0
  465.45     .06       0529.0952    .045       0   571.7     .06       0
  655.45      .1       0
#XS Ineff= 2 , 0
          494.29 3031.51
Permanent Ineff=
       F       F
Bank Sta=529.0952,571.7
XS Rating Curve= 0 ,0
Exp/Cntr=0.3,0.1

Type RM Length L Ch R = 1 ,148550  ,264.2,264.2,264.2
XS GIS Cut Line= 3
2346124.49884716641519.7092009632346383.31964257641442.613644883
2346697.20869232641396.723432931
#Sta/Elev= 30
       0 3050.59    28.9 3047.84    45.6 3047.16    95.7 3041.78   116.5 3036.92
     129 3032.79   141.6 3031.12   154.1 3026.47   158.3 3025.76   172.2 3026.59
   216.7  3024.4   241.7 3020.23   270.9 3018.42   287.1 3018.48   299.2 3021.64
   311.3 3022.19   319.4 3021.49   336.33018.202   343.7 3017.39   370.8 3017.05
   387.7 3018.09   416.5 3017.02   430.8  3019.2   456.9 3019.94     465 3022.38
   481.1 3021.71   504.9 3033.39   548.7 3059.93   557.8 3063.48   587.3 3080.16
#Mann= 5 ,-1,0
       0      .1       0   336.3    .045       0   387.7      .1       0
  400.06     .06       0  500.06      .1       0
#XS Ineff= 2 , 0
          258.72 3031.61  468.06         3027.89
Permanent Ineff=
       F       F
Bank Sta=336.3,387.7
XS Rating Curve= 0 ,0
Exp/Cntr(USF)=0,0
Exp/Cntr=0.3,0.1

Type RM Length L Ch R = 1 ,148286  ,224.9,224.9,224.9
XS GIS Cut Line= 3
2346122.45909538641779.8197138622346511.38893349  641664.7482044
2346775.04746471641577.345510837
#Sta/Elev= 30
       0 3044.26    26.8 3039.37    93.6 3033.78   139.4 3021.84   190.2  3021.3
     227 3023.55   268.8 3023.94   289.6 3021.76     298 3018.45   314.6 3018.17
   327.2 3015.08   360.5 3016.74   381.4 3015.42   406.4 3017.37   444.4 3016.27
     466 3015.09   478.1 3016.29   507.6    3020   520.2 3018.04   537.1 3018.43
   549.7 3021.83   583.1 3043.24   596.1 3052.91   604.5 3056.96   621.3  3069.8
     634 3075.65   642.4 3083.28   655.1 3087.06   667.7 3096.17   683.4 3104.45
#Mann= 5 ,-1,0
       0      .1       0     400     .06       0   444.4    .045       0
   478.1     .06       0   505.6      .1       0
#XS Ineff= 2 , 0
                          508.48         3026.98
Permanent Ineff=
       F       F
Bank Sta=444.4,478.1
XS Rating Curve= 0 ,0
Exp/Cntr=0.3,0.1

Type RM Length L Ch R = 1 ,148061  ,268.6,268.6,268.6
XS GIS Cut Line= 2
2346172.52455918641950.6924457522346775.52194423 641826.78887348
#Sta/Elev= 30
       0 3039.91    40.5 3030.52   130.3 3022.92   171.2 3017.64     211 3016.53
   231.3 3019.42   275.4 3015.74   289.6    3018   301.8 3015.66   314.1 3014.86
   338.6 3016.03   375.3 3015.62   385.83014.567   395.7  3013.1   424.2 3013.37
     438 3014.52   448.8 3017.01   469.3 3016.76   481.5 3018.24   489.7 3016.21
   505.7 3016.91   530.5 3015.44   538.7 3019.42   549.8 3027.25   559.9 3036.15
   575.4 3047.53   583.6  3054.9   599.9  3066.5     604 3068.66   615.6 3071.18
#Mann= 5 ,-1,0
       0      .1       0     340     .06       0   385.8    .045       0
     438     .06       0     440      .1       0
#XS Ineff= 2 , 0
          227.85 3030.21
Permanent Ineff=
       F       F
Bank Sta=385.8,438
XS Rating Curve= 0 ,0
Exp/Cntr(USF)=0,0
Exp/Cntr=0.3,0.1

Type RM Length L Ch R = 1 ,147792  ,243.3,243.3,243.3
XS GIS Cut Line= 3
2346174.37643371642179.1085499192346713.13239935      642106.409
2346879.04811945642070.832216045
#Sta/Elev= 30
       0 3057.97    66.4 3037.13    90.6 3032.88   110.8 3026.96   159.2  3017.2
     240 3017.48   304.5 3019.14   316.6 3020.55   341.2 3019.21   348.9 3017.62
   362.5 3012.36   394.5 3014.21   405.4 3012.67   444.3 3013.62   472.8 3012.02
   490.2 3011.04   497.6 3012.01   514.4 3013.89   530.6 3013.97   546.8 3016.33
   567.4 3012.44   587.7 3014.59   597.8 3019.98   616.3 3034.17   631.5  3043.4
     649 3045.97   657.2 3050.98   665.8 3053.89     694 3068.69   713.3 3076.64
#Mann= 6 ,-1,0
       0      .1       0     340     .08       0     440     .06       0
   472.8    .045       0   497.6     .06       0  633.64      .1       0
#XS Ineff= 2 , 0
          230.19 3022.22
Permanent Ineff=
       F       F
Bank Sta=472.8,497.6
XS Rating Curve= 0 ,0
Exp/Cntr=0.3,0.1

Type RM Length L Ch R = 1 ,147549  ,254.6,254.6,254.6
XS GIS Cut Line= 3
2346326.27376559  642553.50098222346689.72424426642366.819599977
2346897.88224568642213.179170359
#Sta/Elev= 30
       0 3058.91    20.1 3050.11    29.1  3048.1    56.1 3035.41    87.8 3024.22
   105.6 3019.56   132.4 3016.86   144.3    3014   191.8 3013.74   222.5  3016.3
     245 3016.73     263 3016.29   283.9 3012.91   339.4 3016.05   384.4 3013.81
   421.6 3014.92   431.4 3012.74   451.4 3012.46   458.5 3011.16   498.9 3010.09
   508.8 3011.12     531 3012.67   559.5 3009.95   583.3 3018.86   593.2    3027
   608.9 3034.31   620.4 3036.02   631.8 3042.45   655.2 3051.93   667.3 3054.79
#Mann= 5 ,-1,0
       0      .1       0  428.59     .06       0   458.5    .045       0
   508.8     .06       0  548.59      .1       0
#XS Ineff= 2 , 0
          243.75 3023.22
Permanent Ineff=
       F       F
Bank Sta=458.5,508.8
XS Rating Curve= 0 ,0
Exp/Cntr(USF)=0,0
Exp/Cntr=0.3,0.1

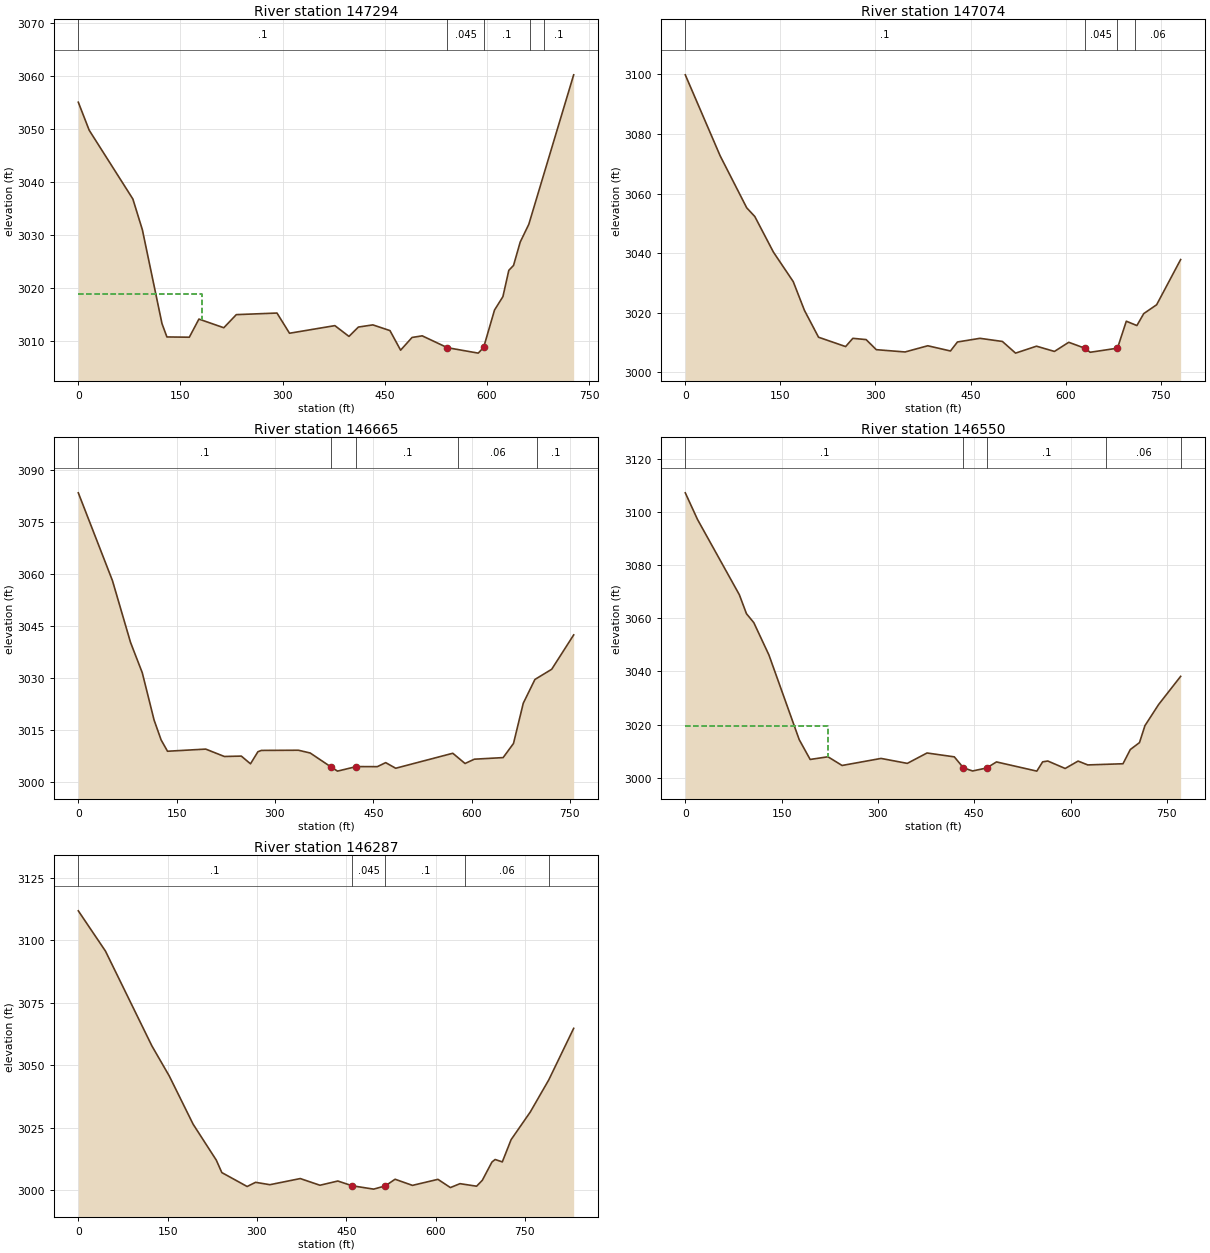
Type RM Length L Ch R = 1 ,147294  ,220.3,220.3,220.3
XS GIS Cut Line= 3
2346442.26059355642800.5867217722346836.82959355642577.490462092
2347048.33520566642403.302219338
#Sta/Elev= 30
       0 3055.09      16 3049.79    80.1 3036.79    94.1 3030.95   122.9  3013.2
   130.1  3010.7     163 3010.65   177.1 3014.08   213.6 3012.44     232 3014.92
   291.7 3015.22   310.1  3011.4   376.7 3012.84   397.4  3010.8   411.2 3012.57
   432.5 3012.98   457.6  3011.9   473.2  3008.2     490  3010.6   504.9 3010.91
   541.9 3008.67   587.2 3007.64   595.1 3008.72   611.1 3015.79   623.4 3018.32
   632.1  3023.3     639 3024.22   648.8 3028.64   661.4 3031.99   727.3 3060.27
#Mann= 5 ,-1,0
       0      .1       0   541.9    .045       0   595.1      .1       0
  663.27     .06       0  683.27      .1       0
#XS Ineff= 2 , 0
          181.35 3018.73
Permanent Ineff=
       F       F
Bank Sta=541.9,595.1
XS Rating Curve= 0 ,0
Exp/Cntr=0.3,0.1

Type RM Length L Ch R = 1 ,147074  ,409.4,409.4,409.4
XS GIS Cut Line= 3
2346561.21921501643101.6034716982346920.83778894642814.609959284
2347149.56557087642588.986642997
#Sta/Elev= 30
       0 3099.87      55 3072.68    96.9 3055.23   109.7  3052.3     139 3040.37
   170.3 3030.45     188 3020.79   210.2 3011.79   252.9 3008.65   264.3 3011.42
   285.3 3010.99   301.3 3007.61   346.7 3006.84   382.5 3008.92   418.3 3007.17
   429.3 3010.19   464.8 3011.42   500.2 3010.37     521 3006.45     554 3008.78
   582.3 3007.02   604.9 3010.09630.36773008.092   638.7 3006.74  681.74 3008.11
   695.7 3017.16   712.4 3015.71   723.2 3019.72   743.5 3022.68   781.4 3037.86
#Mann= 4 ,-1,0
       0      .1       0630.3677    .045       0  681.74      .1       0
   710.1     .06       0
#XS Ineff= 2 , 0
          182.05  3017.2
Permanent Ineff=
       F       F
Bank Sta=630.3677,681.74
XS Rating Curve= 0 ,0
Exp/Cntr(USF)=0,0
Exp/Cntr=0.3,0.1

Type RM Length L Ch R = 1 ,146665  ,114.8,114.8,114.8
XS GIS Cut Line= 2
2346745.87712732  643236.04563862347336.20969589642764.306491119
#Sta/Elev= 30
       0 3083.38    52.1 3058.07    79.7 3040.25    97.6 3031.52   115.6 3017.89
   126.3 3012.18   136.1  3008.9   194.4 3009.52   222.8 3007.39   248.7  3007.5
   262.7 3005.28     274 3008.76   279.4 3009.14   335.8 3009.19   353.7  3008.4
     385 3004.44   395.4 3003.17  424.07 3004.48   456.2 3004.46   468.9 3005.62
   484.2    3004   571.3 3008.32     590 3005.37   604.2 3006.61   648.1 3007.07
   663.9 3011.14   678.8 3022.73   696.6 3029.59   722.2 3032.53   755.7 3042.43
#Mann= 5 ,-1,0
       0      .1       0     385    .045       0  424.07      .1       0
     580     .06       0     700      .1       0
Bank Sta=385,424.07
XS Rating Curve= 0 ,0
Exp/Cntr=0.3,0.1

Type RM Length L Ch R = 1 ,146550  ,262.4,262.4,262.4
XS GIS Cut Line= 3
2346798.61211392643366.6045029452347028.06317368643150.002702529
2347391.51365235642874.661430813
#Sta/Elev= 30
       0 3107.35    19.1 3097.28    84.2 3068.93    95.3 3061.77   106.7 3058.42
   130.3  3046.2   177.5 3014.26   194.5 3006.82   222.2 3007.83   244.2 3004.55
   304.9 3007.21   345.8 3005.34   376.5 3009.26     419  3007.8   433.3 3003.63
   447.5 3002.48   469.3  3003.6   484.7 3005.89   547.5 3002.42   556.6 3005.92
   564.6 3006.23   591.7 3003.42   611.8 3006.21   626.8 3004.76   681.7  3005.2
   693.1 3010.56   707.4 3013.17   715.9 3019.57   737.2 3027.53   771.5 3038.15
#Mann= 5 ,-1,0
       0      .1       0   433.3    .045       0   469.3      .1       0
  655.54     .06       0  771.51      .1       0
#XS Ineff= 2 , 0
          222.82 3019.55
Permanent Ineff=
       F       F
Bank Sta=433.3,469.3
XS Rating Curve= 0 ,0
Exp/Cntr(USF)=0,0
Exp/Cntr=0.3,0.1

Type RM Length L Ch R = 1 ,146287  ,262,262,262
XS GIS Cut Line= 2
2347001.82220072643607.1152080122347556.00531363 642986.78741487
#Sta/Elev= 30
       0 3111.73    45.6 3095.64   123.6 3057.74   152.8 3045.71   192.8 3026.47
   231.7 3012.12     241 3007.14   283.5 3001.58   297.7 3003.25   321.7  3002.3
   372.7 3004.75   405.8 3002.08   435.8 3003.77   459.8 3001.87     496 3000.53
   515.8 3001.86   531.9 3004.48   561.1 3002.03   603.9 3004.44   624.8 3001.15
   640.9 3002.71   668.8  3001.7   678.4 3004.06   694.5 3011.33   699.9 3012.37
     712 3011.41   726.7 3020.28   758.9 3031.33     790 3044.19   831.8 3064.77
#Mann= 5 ,-1,0
       0      .1       0   459.8    .045       0   515.8      .1       0
     650     .06       0     790      .1       0
Bank Sta=459.8,515.8
XS Rating Curve= 0 ,0
Exp/Cntr=0.3,0.1