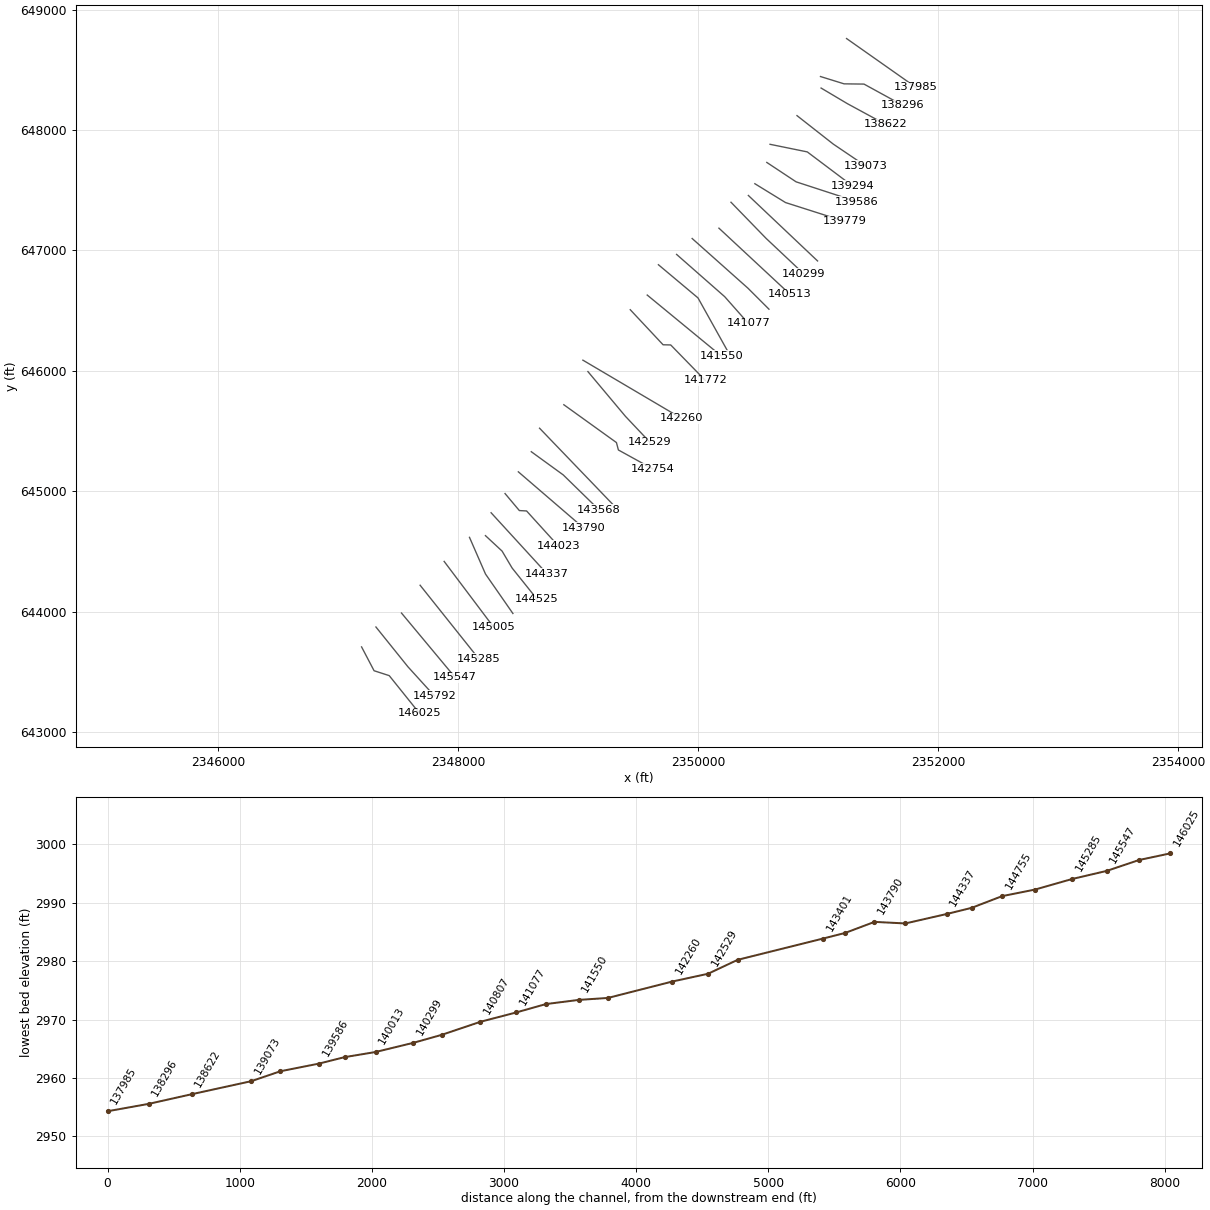
HEC-RAS study LAURELFK.prj: LAURELFK

--- LAURELFK.g01 (geometry) --- (continued)

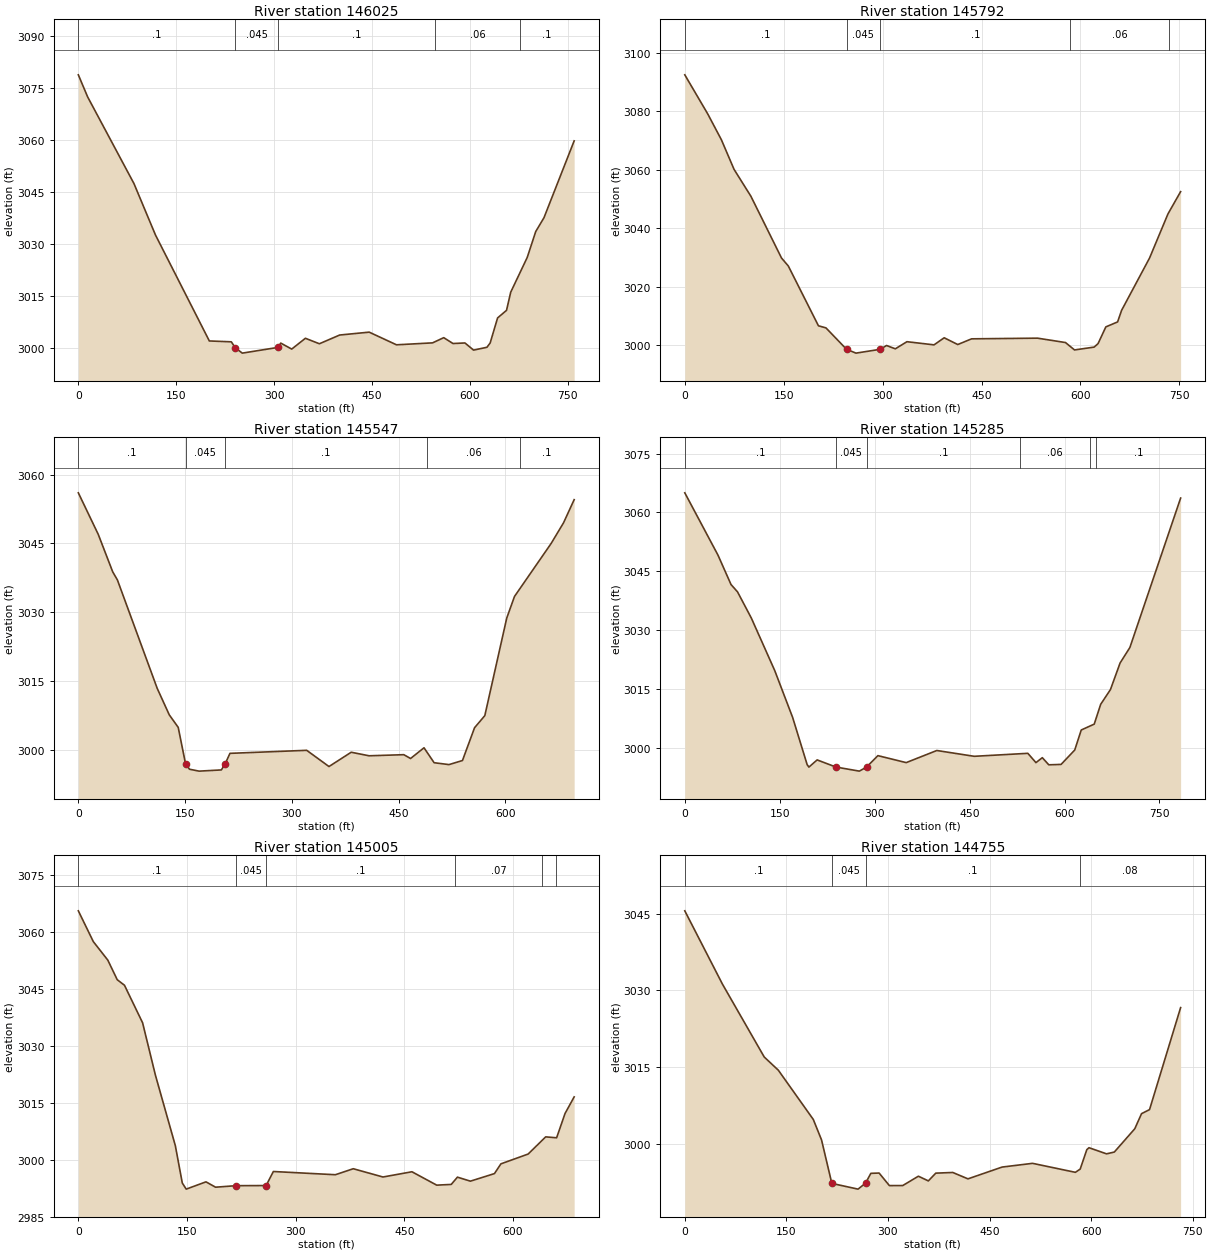
Type RM Length L Ch R = 1 ,146025  ,233.5,233.5,233.5
XS GIS Cut Line= 4
2347193.77544986643705.8353573552347297.79326362643507.997554715
2347424.24629211643467.206255201 2347677.1523491643153.113248948
#Sta/Elev= 30
       0 3078.66    14.3 3072.28    85.2 3047.31   118.2 3032.46   200.7 3001.91
   234.4 3001.66   240.4 2999.94   251.2  2998.4   305.9 3000.05   310.1 3001.29
   326.9 2999.57   347.9 3002.68   369.3  3001.1   400.4 3003.62   445.6 3004.45
   487.4  3000.8   542.7 3001.36   559.8 3002.86     574 3001.17   592.3 3001.33
   605.5 2999.27     626 3000.09   630.9 3001.32   642.3 3008.55     656 3010.74
   662.4 3015.97   687.7 3025.99   700.7 3033.45   713.4 3037.47   759.6 3059.61
#Mann= 5 ,-1,0
       0      .1       0   240.4    .045       0   305.9      .1       0
  546.39     .06       0  676.39      .1       0
Bank Sta=240.4,305.9
XS Rating Curve= 0 ,0
Exp/Cntr(USF)=0,0
Exp/Cntr=0.3,0.1

Type RM Length L Ch R = 1 ,145792  ,244.5,244.5,244.5
XS GIS Cut Line= 3
2347313.31015859643871.3171989332347580.05352956643540.807684596
2347800.58985663643298.924470437
#Sta/Elev= 30
       0 3092.52    34.8 3079.14    55.5  3070.3    74.7 3060.17   100.3 3050.95
   146.7 3029.82     157  3027.1   202.7 3006.63   214.1 3005.92   245.3 2998.59
   259.6 2997.28   296.5 2998.59     306 2999.89   319.3 2998.75   336.9 3001.19
     378 3000.11   393.4 3002.53     414 3000.22     435 3002.17     535  3002.4
   577.4  3000.9   591.1 2998.37   620.8 2999.34   626.8 3000.54   638.6 3006.26
   656.4 3007.96   662.5 3011.93   704.9 3029.83   732.8 3044.92     752 3052.54
#Mann= 5 ,-1,0
       0      .1       0   245.3    .045       0   296.5      .1       0
  584.72     .06       0  734.72      .1       0
Bank Sta=245.3,296.5
XS Rating Curve= 0 ,0
Exp/Cntr=0.3,0.1

Type RM Length L Ch R = 1 ,145547  ,262.6,262.6,262.6
XS GIS Cut Line= 2
 2347526.2245409643987.2953239972347972.88927057643452.929300372
#Sta/Elev= 30
       0 3056.01      28 3046.96    48.3 3038.81    54.9 3037.04   110.8 3013.44
   127.8 3007.66   140.3 3004.95   150.6 2997.03   156.2 2995.83   169.6 2995.42
   200.9 2995.68   206.1 2996.95     213 2999.29   320.8 2999.95   352.1 2996.42
   383.3 2999.53   408.4 2998.76   457.2    2999   466.7 2998.17   485.6  3000.5
   499.8 2997.25   520.7 2996.84   539.6 2997.73   556.6 3004.87     571  3007.5
   601.8 3028.74   612.7 3033.45   664.2 3044.99   681.6 3049.49   696.5 3054.52
#Mann= 5 ,-1,0
       0      .1       0   150.6    .045       0   206.1      .1       0
     490     .06       0     620      .1       0
Bank Sta=150.6,206.1
XS Rating Curve= 0 ,0
Exp/Cntr(USF)=0,0
Exp/Cntr=0.3,0.1

Type RM Length L Ch R = 1 ,145285  ,279.5,279.5,279.5
XS GIS Cut Line= 2
2347681.49766564644218.1930966772348170.99581946643606.611132977
#Sta/Elev= 30
       0 3065.01    52.5  3049.1      73 3041.63    83.3 3039.75   105.1 3033.08
   142.1 3019.68   170.4 3007.72   193.3  2995.7   196.1 2995.06   209.1 2996.89
   238.8 2995.07   275.8 2994.03   287.2 2995.07   305.1 2997.98   349.8  2996.2
   398.2 2999.29   457.3 2997.81     542 2998.57   554.8  2996.2   564.9 2997.46
   575.1 2995.64   594.5 2995.74   616.1 2999.41   626.4 3004.52   646.9 3006.02
   657.1 3011.07   672.5 3014.82   687.8 3021.62   703.2 3025.55   783.4 3063.67
#Mann= 6 ,-1,0
       0      .1       0   238.8    .045       0   287.2      .1       0
     530     .06       0     640     .07       0     650      .1       0
Bank Sta=238.8,287.2
XS Rating Curve= 0 ,0
Exp/Cntr=0.3,0.1

Type RM Length L Ch R = 1 ,145005  ,250.2,250.2,250.2
XS GIS Cut Line= 2
2347882.00817016644415.9979345462348294.45353191643869.847757727
#Sta/Elev= 30
       0 3065.67    20.7 3057.54    40.7 3052.66    53.7 3047.49    63.7 3046.03
    88.7 3036.13   106.4 3022.31   133.9  3003.7   143.5 2993.85   148.9 2992.23
   176.2 2994.15   189.4 2992.74   217.7 2993.14   259.2 2993.17   269.2 2996.88
   354.8 2996.03   379.5 2997.61   420.5 2995.43   460.5 2996.81   494.7 2993.28
   514.7 2993.47   523.3 2995.39   541.2 2994.33   574.4 2996.33   583.3  2998.9
   620.9 3001.49   645.1 3006.02   660.2 3005.78   671.8 3012.18   684.4 3016.57
#Mann= 6 ,-1,0
       0      .1       0   217.7    .045       0   259.2      .1       0
     520     .07       0     640     .08       0     660      .1       0
Bank Sta=217.7,259.2
XS Rating Curve= 0 ,0
Exp/Cntr(USF)=0,0
Exp/Cntr=0.3,0.1

Type RM Length L Ch R = 1 ,144755  ,229.9,229.9,229.9
XS GIS Cut Line= 3
2348093.11872564644615.9933691462348226.60116456644311.107877832
2348454.87364586 643983.54973565
#Sta/Elev= 30
       0  3045.6    55.5 3031.27   117.3 3016.97   138.1 3014.39   189.7 3004.75
   201.9 3000.74   217.1 2992.22   255.8  2991.1   266.9 2992.27   274.7 2994.19
   286.9 2994.25   302.1 2991.79   321.8  2991.8   344.9 2993.63   359.6 2992.71
   370.6 2994.23   395.7 2994.36   418.1 2993.11   468.5 2995.42   513.5 2996.15
   576.7 2994.39   583.8 2995.02   593.6 2998.83   596.8 2999.21   622.7 2998.01
   634.2 2998.36   664.4 3002.92   674.4 3005.88   686.2 3006.67   732.1 3026.65
#Mann= 4 ,-1,0
       0      .1       0   217.1    .045       0   266.9      .1       0
  582.83     .08       0
Bank Sta=217.1,266.9
XS Rating Curve= 0 ,0
Exp/Cntr=0.3,0.1

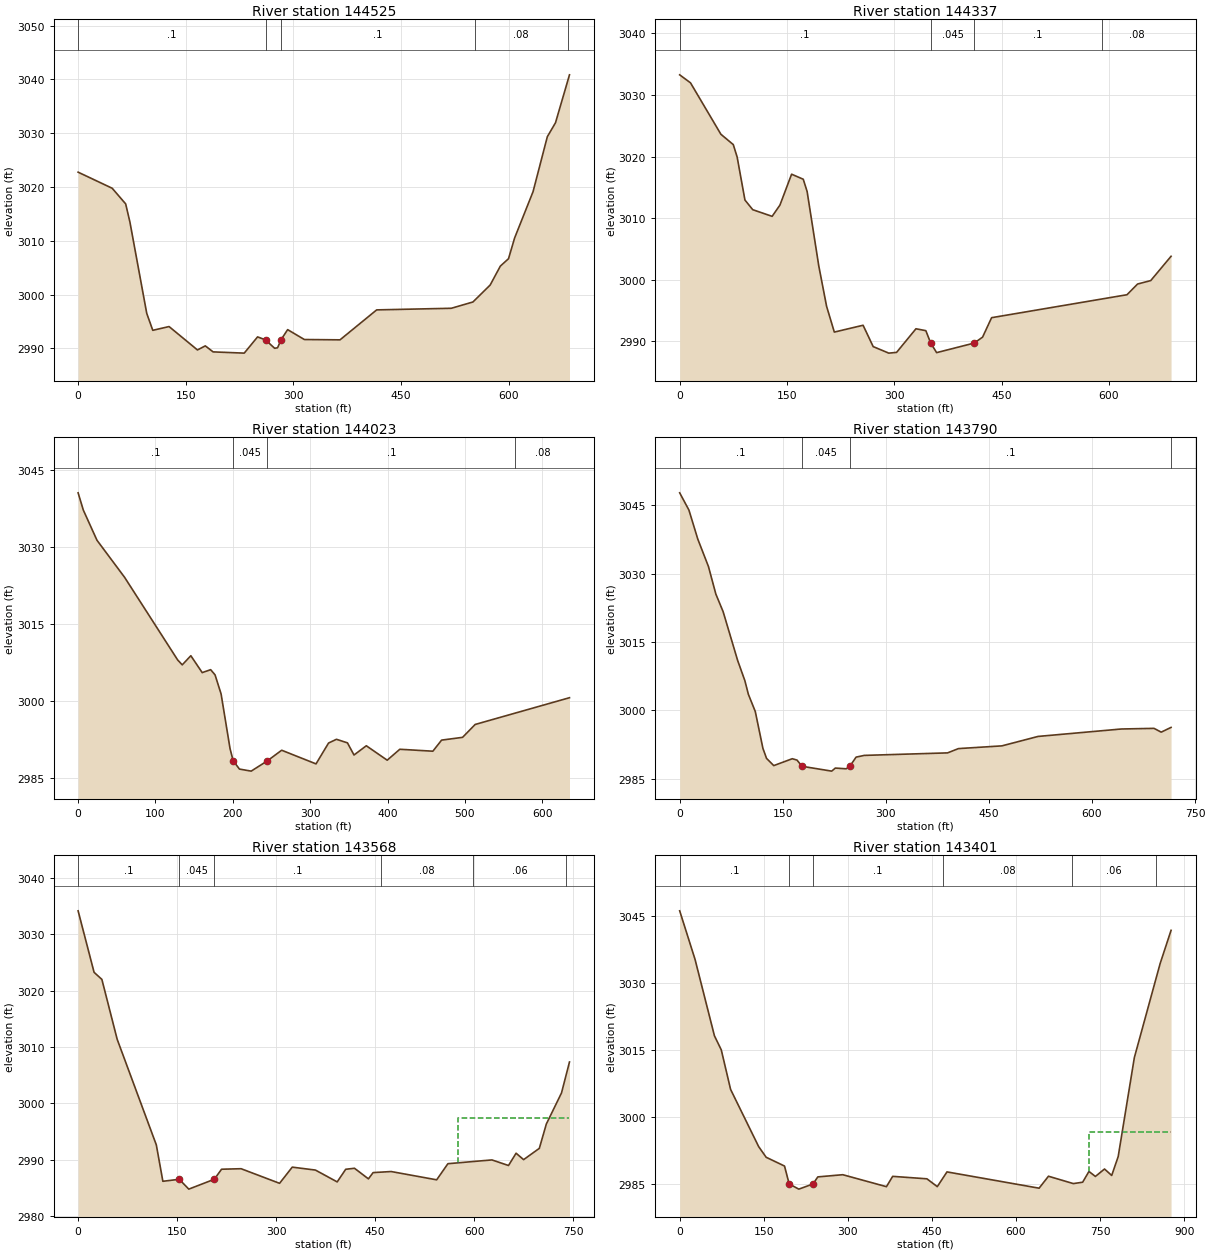
Type RM Length L Ch R = 1 ,144525  ,188.4,188.4,188.4
XS GIS Cut Line= 4
2348226.11023066 644630.243339532348364.80064901644501.750746063
2348448.42281301644361.0207627412348656.45844053644101.996010831
#Sta/Elev= 30
       0 3022.75    47.5 3019.76    66.3 3016.85    72.2 3013.49    95.7 2996.48
   104.1 2993.34   126.8 2994.04   166.4 2989.69   177.3 2990.45   188.2 2989.33
   231.6  2989.1   250.2 2992.12   261.3 2991.56     274    2990   278.1  2990.1
   282.8 2991.57   292.1 2993.47   315.4 2991.63   365.1 2991.57   416.2 2997.14
   520.3 2997.44   550.4 2998.61   574.4 3001.76   588.6 3005.28     600 3006.66
   608.5 3010.51   634.2 3019.12   654.1 3029.34   665.5 3031.94     685 3040.85
#Mann= 5 ,-1,0
       0      .1       0   261.3    .045       0   282.8      .1       0
  552.76     .08       0  682.76      .1       0
Bank Sta=261.3,282.8
XS Rating Curve= 0 ,0
Exp/Cntr(USF)=0,0
Exp/Cntr=0.3,0.1

Type RM Length L Ch R = 1 ,144337  ,313.6,313.6,313.6
XS GIS Cut Line= 2
2348273.20782837644820.3329959352348737.83645011644314.707731101
#Sta/Elev= 30
       0 3033.28    15.1 3031.98    57.6 3023.62    74.9 3021.94    80.3 3019.92
    91.2 3012.93   102.1 3011.36   129.2 3010.28   140.1 3012.11   156.4 3017.13
   172.7 3016.31   178.1 3014.31   194.4 3002.21   205.3 2995.66   216.1 2991.47
   256.3 2992.58   270.4 2989.11   292.2 2988.05   303.1 2988.17   330.2 2992.01
     344  2991.7  350.71  2989.7   359.1 2988.13   411.7 2989.69   423.3 2990.65
   435.9 2993.81   625.1 2997.54   639.9 2999.28   658.3 2999.84   686.7 3003.79
#Mann= 4 ,-1,0
       0      .1       0  350.71    .045       0   411.7      .1       0
     590     .08       0
Bank Sta=350.71,411.7
XS Rating Curve= 0 ,0
Exp/Cntr(USF)=0,0
Exp/Cntr=0.3,0.1

Type RM Length L Ch R = 1 ,144023  ,233.5,233.5,233.5
XS GIS Cut Line= 4
2348389.42302552644979.8008965982348508.55892762644838.553726199
2348568.87987249644835.2376214662348831.52794901644547.067800045
#Sta/Elev= 30
       0 3040.64     6.7 3037.29    24.4  3031.4    60.1 3024.18   128.7 3008.08
   134.6 3007.13   145.7 3008.91   160.4 3005.62   171.3 3006.19     177 3005.18
   184.8 3001.47   196.4 2990.79   200.4 2988.46   208.5 2986.83   223.7 2986.43
   244.5 2988.42   263.1  2990.5   307.5 2987.84   323.7  2991.9   333.9 2992.63
   348.1 2991.94   356.6 2989.57   372.5 2991.37   399.5 2988.56   415.8 2990.69
   458.5 2990.31   469.8 2992.47   496.9 2993.01   513.2 2995.52   635.1 3000.73
#Mann= 4 ,-1,0
       0      .1       0   200.4    .045       0   244.5      .1       0
  565.19     .08       0
Bank Sta=200.4,244.5
XS Rating Curve= 0 ,0
Exp/Cntr(USF)=0,0
Exp/Cntr=0.3,0.1

Type RM Length L Ch R = 1 ,143790  ,221.7,221.7,221.7
XS GIS Cut Line= 2
2348500.22753871645160.269027379     2349043.059      644694.868
#Sta/Elev= 30
       0 3047.74    13.5 3043.94    26.3 3037.61    41.9 3031.56    52.6 3025.54
    63.2 3021.68    84.4 3010.95    94.8 3006.56     100 3003.53     110 2999.78
   121.1  2991.7   126.4 2989.49   136.9 2987.91   163.8 2989.42   170.7 2989.12
     178 2987.76   221.2  2986.7   226.5 2987.37   242.3 2987.21   247.6 2987.77
   256.7 2989.77   268.6 2990.15   389.8  2990.7   405.6 2991.64   468.9 2992.24
   521.5 2994.31   642.7 2995.94   690.2 2996.08   700.7 2995.25     715 2996.29
#Mann= 4 ,-1,0
       0      .1       0     178    .045       0   247.6      .1       0
  715.03     .06       0
Bank Sta=178,247.6
XS Rating Curve= 0 ,0
Exp/Cntr=0.3,0.1

Type RM Length L Ch R = 1 ,143568  ,166.8,166.8,166.8
XS GIS Cut Line= 3
 2348608.1776487645327.3841877342348874.49192709645134.640592994
2349172.35451436644844.699684752
#Sta/Elev= 30
       0 3034.17    24.2 3023.26      36 3022.01    59.2 3011.38   118.5 2992.65
   128.4  2986.2153.19992986.553   167.7 2984.81206.39982986.563   217.3 2988.34
   246.9 2988.43   305.2 2985.84   324.4 2988.71   359.5 2988.19   392.5 2986.09
   405.4 2988.33   418.7 2988.51   439.8 2986.63   446.9 2987.74   474.2 2987.93
   543.2 2986.46   560.2 2989.32   626.9 2989.99     652    2989   663.5 2991.18
   674.9 2990.04   698.7 2992.04   709.3 2996.35   732.3 3001.87   744.4 3007.36
#Mann= 6 ,-1,0
       0      .1       0153.1999    .045       0206.3998      .1       0
  458.75     .08       0  598.75     .06       0  738.75      .1       0
#XS Ineff= 2 , 0
                          574.79         2997.49
Permanent Ineff=
       F       F
Bank Sta=153.1999,206.3998
XS Rating Curve= 0 ,0
Exp/Cntr(USF)=0,0
Exp/Cntr=0.3,0.1

Type RM Length L Ch R = 1 ,143401  ,646.6,646.6,646.6
XS GIS Cut Line= 2
2348677.13166149645522.5729544472349285.70181696644891.738944141
#Sta/Elev= 30
       0 3046.19    27.4 3035.31      62 3018.19    74.2 3015.04    90.8 3006.19
   140.9 2993.37   154.2 2990.99     187 2989.02  195.29 2985.01   212.5 2983.85
   237.9 2985.01   246.4 2986.59   290.9 2987.08   368.8  2984.4   379.9 2986.71
     441 2986.16   459.5 2984.41   476.8 2987.71   641.1 2984.06   657.8 2986.74
   702.2 2985.09   718.8  2985.4     730 2987.81   741.5 2986.69   757.8 2988.36
   770.6 2986.91   782.2 2991.15     811 3013.31     857 3034.38   876.5 3041.82
#Mann= 6 ,-1,0
       0      .1       0  195.29    .045       0   237.9      .1       0
     470     .08       0     700     .06       0     850      .1       0
#XS Ineff= 2 , 0
                          730.92         2996.62
Permanent Ineff=
       F       F
Bank Sta=195.29,237.9
XS Rating Curve= 0 ,0
Exp/Cntr=0.3,0.1

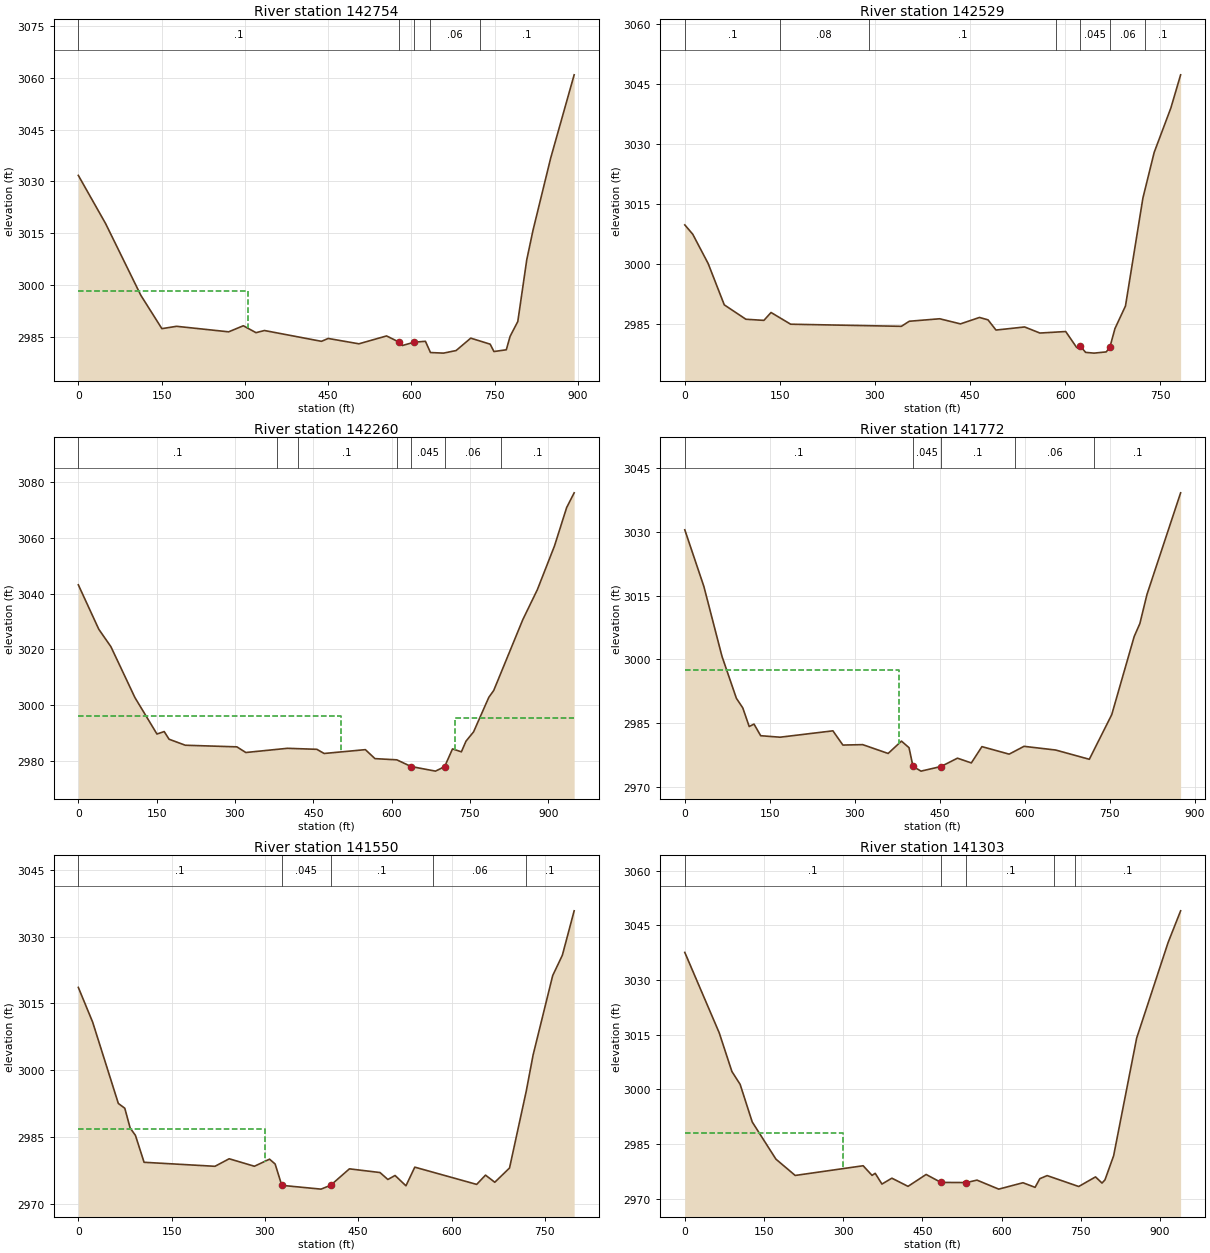
Type RM Length L Ch R = 1 ,142754  ,225.2,225.2,225.2
XS GIS Cut Line= 4
2348879.42323344  645717.62543122349317.86303019645403.396364393
2349334.17855878645341.7567944022349619.93869628645184.859166806
#Sta/Elev= 30
       0  3031.7    49.2 3017.72   112.5 2996.99   150.5  2987.3     177 2987.98
   270.8 2986.38   297.2 2988.14     320 2986.14   335.3 2986.76   437.9 2983.63
   450.1 2984.46   505.4 2982.91   555.2 2985.19   577.9 2983.39   583.7 2982.42
     605 2983.38   625.2 2983.64   634.3 2980.38   657.8 2980.21   680.5 2980.96
   706.8 2984.55   741.8 2982.81   748.6 2980.67   770.9 2981.18   777.7 2985.07
   791.6 2989.37   807.7 3007.23     819 3015.81   850.8 3036.71   893.1 3060.84
#Mann= 5 ,-1,0
       0      .1       0   577.9    .045       0     605      .1       0
  633.18     .06       0  723.18      .1       0
#XS Ineff= 2 , 0
          305.37 2998.14
Permanent Ineff=
       F       F
Bank Sta=577.9,605
XS Rating Curve= 0 ,0
Exp/Cntr=0.3,0.1

Type RM Length L Ch R = 1 ,142529  ,269,269,269
XS GIS Cut Line= 3
2349080.14964627645992.9572510042349392.88294254645621.303188771
 2349596.8394401645406.015774672
#Sta/Elev= 30
       0 3009.88    12.5 3007.56    36.8 3000.24    62.3 2989.89    96.4 2986.29
   124.8 2986.01   136.1 2987.98     167 2985.05   341.7 2984.52   354.2 2985.79
   402.2 2986.41   434.9 2985.13     465 2986.74   478.4 2986.14     491 2983.59
   536.2 2984.36   560.3 2982.84     601 2983.22   618.3 2979.22   624.3 2979.49
   632.4 2978.01   645.7 2977.82     665 2978.13   670.8 2979.37   678.7 2983.96
   695.3 2989.61   722.8  3016.6   740.6 3028.02   766.9 3039.11   782.3  3047.4
#Mann= 7 ,-1,0
       0      .1       0     150     .08       0     290      .1       0
  585.73     .06       0   624.3    .045       0   670.8     .06       0
  725.73      .1       0
Bank Sta=624.3,670.8
XS Rating Curve= 0 ,0
Exp/Cntr(USF)=0,0
Exp/Cntr=0.3,0.1

Type RM Length L Ch R = 1 ,142260  ,487.9,487.9,487.9
XS GIS Cut Line= 2
2349038.38498525646087.8246481342349856.97516369645606.325751217
#Sta/Elev= 30
       0 3043.13    39.2 3027.24    62.4    3021   108.4 3002.81   150.6 2989.77
   164.5 2990.65   173.8 2987.91   204.9 2985.76   303.7 2985.18   320.8 2983.16
   400.6 2984.66   456.9  2984.3   470.8 2982.81   549.8 2984.18   568.2 2980.97
     610 2980.54   637.3 2978.15   684.1  2976.5   701.6  2978.1   716.7 2984.45
   733.7  2983.4   742.5  2987.2   757.1 2990.56   786.3 3002.92   795.6 3005.33
   851.3 3030.66   879.2 3041.39     912 3057.02   935.3 3070.75   949.7 3076.03
#Mann= 7 ,-1,0
       0      .1       0     380     .08       0     420      .1       0
     610     .06       0   637.3    .045       0   701.6     .06       0
     810      .1       0
#XS Ineff= 2 , 0
          503.67 2996.33  721.31         2995.43
Permanent Ineff=
       F       F
Bank Sta=637.3,701.6
XS Rating Curve= 0 ,0
Exp/Cntr=0.3,0.1

Type RM Length L Ch R = 1 ,141772  ,222.1,222.1,222.1
XS GIS Cut Line= 4
2349433.10127863646506.8476449422349706.57194249646215.737255342
2349770.34449842646214.218861154 2350058.4989675645919.452501405
#Sta/Elev= 30
       0 3030.53    33.7 3017.18    65.6 3000.75    91.1 2990.84   102.4 2988.58
   113.7  2984.2   122.2 2984.77     134 2982.03   168.1 2981.68   261.5 2983.18
   279.1 2979.83   314.1 2979.93     359 2977.85   382.5 2980.76   395.9 2979.21
   402.9  2974.8     417 2973.69452.37922974.779   481.4 2976.74   505.9 2975.62
   524.6 2979.46   572.7 2977.69   598.9 2979.53   654.8 2978.66   714.2 2976.48
   753.8    2987   793.4 3005.39   803.4 3008.43     816 3015.31   875.4 3039.24
#Mann= 5 ,-1,0
       0      .1       0   402.9    .045       0452.3792      .1       0
   583.2     .06       0   723.2      .1       0
#XS Ineff= 2 , 0
          377.61 2997.44
Permanent Ineff=
       F       F
Bank Sta=402.9,452.3792
XS Rating Curve= 0 ,0
Exp/Cntr=0.3,0.1

Type RM Length L Ch R = 1 ,141550  ,247.7,247.7,247.7
XS GIS Cut Line= 2
2349574.42380967646628.6813539082350190.82566899646123.322476603
#Sta/Elev= 30
       0 3018.59      23 3010.82    64.3 2992.57    74.7 2991.49    83.3 2987.06
    91.8 2985.41   105.7 2979.37   219.7 2978.47   242.5 2980.16   283.1 2978.48
   307.4 2980.07   316.4 2978.98   327.12974.197   390.2 2973.35   405.7 2974.22
   435.8  2977.9     485 2977.07   497.6 2975.51   509.2 2976.41   526.7  2974.1
   540.9 2978.28   640.4 2974.41   654.6 2976.49   669.5 2974.89   693.2 2978.09
     720 2995.27   731.1 3003.44   762.6 3021.25   778.1  3025.8   797.1 3035.77
#Mann= 5 ,-1,0
       0      .1       0   327.1    .045       0   405.7      .1       0
     570     .06       0     720      .1       0
#XS Ineff= 2 , 0
          299.33 2986.89
Permanent Ineff=
       F       F
Bank Sta=327.1,405.7
XS Rating Curve= 0 ,0
Exp/Cntr(USF)=0,0
Exp/Cntr=0.3,0.1

Type RM Length L Ch R = 1 ,141303  ,225.3,225.3,225.3
XS GIS Cut Line= 3
     2349667.723      646880.5842349997.58870049646605.037644197
2350246.10535024 646160.50295483
#Sta/Elev= 30
       0 3037.55    65.2  3015.5    89.2  3004.9   104.8 3001.37   127.7 2991.06
   172.6 2980.86   209.1 2976.39   337.8 2979.05   354.7  2976.4   360.6 2976.98
   373.4 2974.03   392.2 2975.64   422.8  2973.4   457.1 2976.66   485.1 2974.48
   533.5 2974.44   553.4 2975.11   594.6 2972.64   640.5 2974.39   663.4 2973.13
   672.5 2975.51   686.3 2976.35   746.1 2973.36   777.9 2975.99   790.2  2974.3
   795.8 2975.18   812.2 2981.78   855.8 3014.04   915.4 3040.27   939.1 3048.95
#Mann= 5 ,-1,0
       0      .1       0   485.1    .045       0   533.5      .1       0
  699.81     .06       0  739.81      .1       0
#XS Ineff= 2 , 0
          300.34 2988.04
Permanent Ineff=
       F       F
Bank Sta=485.1,533.5
XS Rating Curve= 0 ,0
Exp/Cntr=0.3,0.1

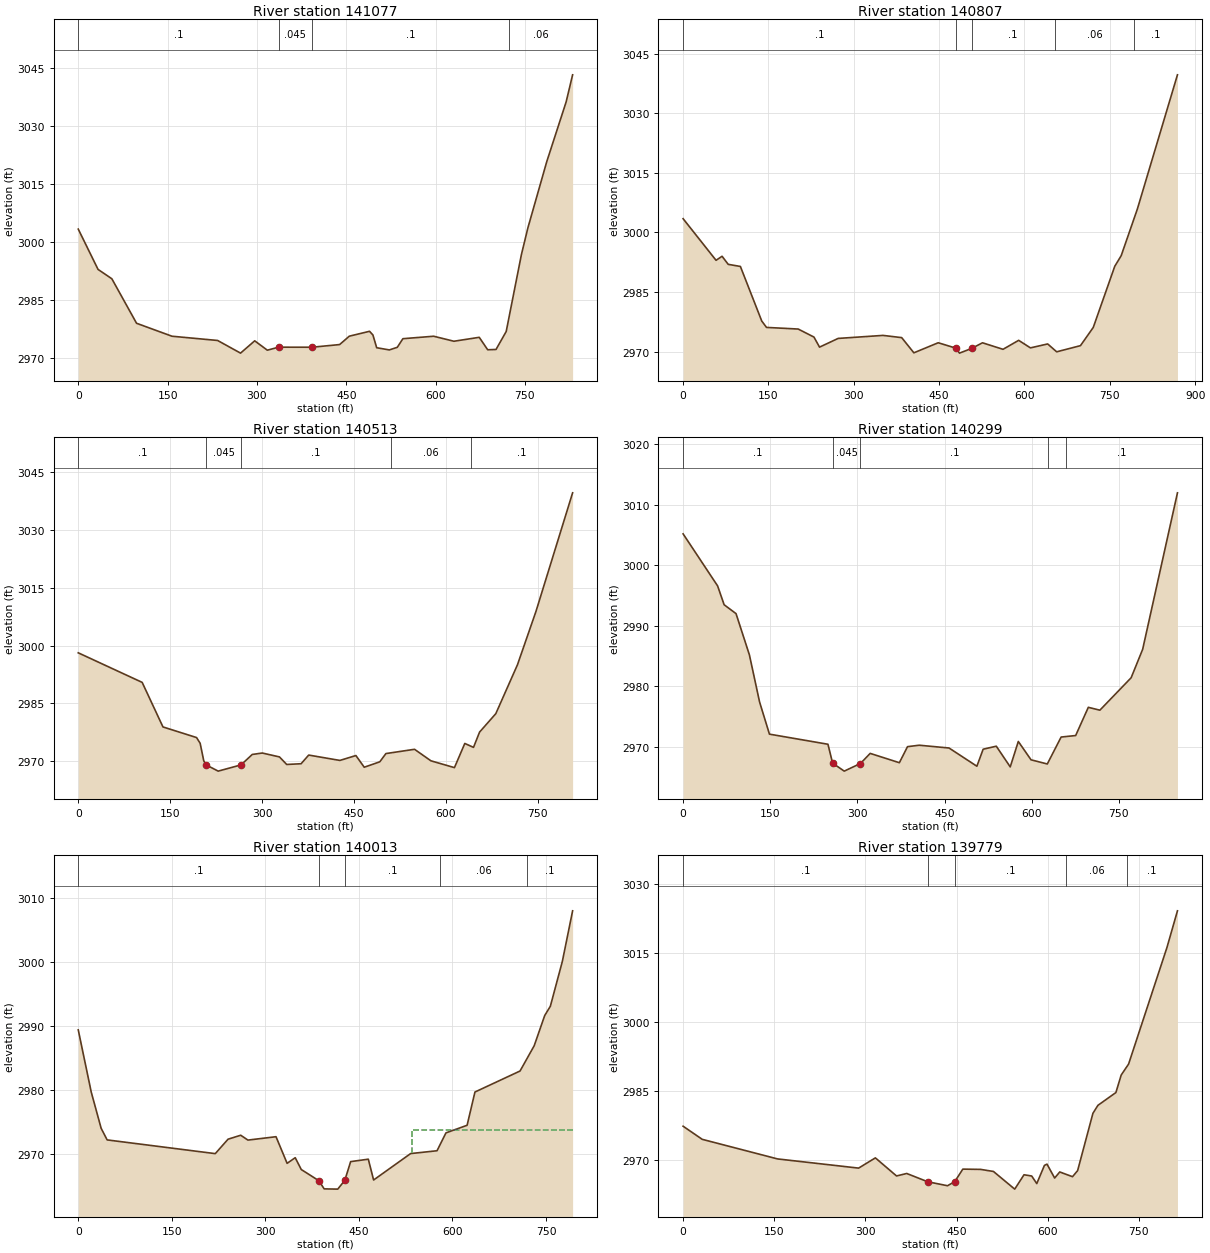
Type RM Length L Ch R = 1 ,141077  ,269.9,269.9,269.9
XS GIS Cut Line= 3
2349819.17160675646966.3426665472350220.28605197 646615.08425407
2350417.44399962646392.998290053
#Sta/Elev= 30
       0 3003.35    33.2 2992.91    56.4 2990.48    97.9 2978.94   157.4 2975.58
     234 2974.48   272.5  2971.2   296.3 2974.39   317.5 2971.96   336.3 2972.74
   392.7 2972.73   438.9 2973.42   455.1 2975.59   489.1 2976.86   494.8  2975.9
   501.1  2972.6   522.4 2972.03   535.7 2972.71   545.1 2974.94   596.8 2975.58
   630.8 2974.28   673.3  2975.3   687.5 2972.07   701.5 2972.15   718.6 2976.81
   744.1 2996.73     755 3003.67   786.6  3020.8   819.2 3036.31   830.1 3043.35
#Mann= 4 ,-1,0
       0      .1       0   336.3    .045       0   392.7      .1       0
  723.17     .06       0
Bank Sta=336.3,392.7
XS Rating Curve= 0 ,0
Exp/Cntr(USF)=0,0
Exp/Cntr=0.3,0.1

Type RM Length L Ch R = 1 ,140807  ,294,294,294
XS GIS Cut Line= 3
2349948.85276596647098.4946170182350414.63751556646685.016484442
2350589.02958428      646511.471
#Sta/Elev= 30
       0 3003.44    57.9 2992.97    68.5 2993.98    79.3 2991.95   100.7 2991.42
   138.2  2977.7   146.6 2976.08   202.3 2975.67     230 2973.65   239.8 2971.12
   272.5 2973.31   351.4 2974.07   384.2 2973.51   405.6 2969.69   448.4 2972.22
   479.3 2970.87   485.8 2969.61   507.6 2970.82   526.2 2972.21   562.3 2970.57
   589.8 2972.83   610.5 2970.93   640.8 2971.92   656.6 2969.94   698.4 2971.49
   720.9 2976.07   758.7 2991.46     770 2994.13   798.4 3005.86   868.9 3039.64
#Mann= 5 ,-1,0
       0      .1       0   479.3    .045       0   507.6      .1       0
  652.83     .06       0  792.83      .1       0
Bank Sta=479.3,507.6
XS Rating Curve= 0 ,0
Exp/Cntr=0.3,0.1

Type RM Length L Ch R = 1 ,140513  ,214,214,214
XS GIS Cut Line= 2
2350172.02577702647184.3970970262350763.49961997  646635.9807369
#Sta/Elev= 30
       0  2998.1   104.3 2990.42   138.2 2978.85     193 2976.09   198.9  2974.6
   204.8 2970.03     209 2968.96   228.3 2967.37   265.6 2968.99   283.9  2971.7
   300.2 2972.07   328.3 2971.06   340.1  2969.1   363.6 2969.29     376 2971.54
   426.9 2970.15     453 2971.42   466.6 2968.38     492 2969.79     502 2971.93
   548.7 2973.04   575.4 2970.05   613.8 2968.28   630.7 2974.56   644.9 2973.54
   654.8 2977.51   681.3  2982.3   716.6 2994.99   746.8 3008.85   806.6 3039.66
#Mann= 5 ,-1,0
       0      .1       0     209    .045       0   265.6      .1       0
     510     .06       0     640      .1       0
Bank Sta=209,265.6
XS Rating Curve= 0 ,0
Exp/Cntr(USF)=0,0
Exp/Cntr=0.3,0.1

Type RM Length L Ch R = 1 ,140299  ,286,286,286
XS GIS Cut Line= 3
 2350272.5507987647399.7202012982350564.85388217647099.861934523
2350879.91331588646804.190499189
#Sta/Elev= 30
       0 3005.21    59.4 2996.61    70.6  2993.5    91.1 2992.03   114.1 2985.22
   131.6 2977.44   148.6 2972.12   249.3 2970.45   257.3 2967.33   277.3 2966.01
   305.2 2967.27     322 2968.94   372.2  2967.4   386.2 2970.05   406.3 2970.29
   457.7 2969.83   505.6 2966.82   516.4 2969.63     539 2970.13     563 2966.71
   576.9 2970.91   598.8 2967.88   626.8 2967.19   650.6 2971.64   675.6 2971.89
   697.4 2976.55   717.3 2976.08   771.1 2981.44   790.9 2986.13   850.8 3011.99
#Mann= 5 ,-1,0
       0      .1       0   257.3    .045       0   305.2      .1       0
  628.76     .06       0  658.76      .1       0
Bank Sta=257.3,305.2
XS Rating Curve= 0 ,0
Exp/Cntr=0.3,0.1

Type RM Length L Ch R = 1 ,140013  ,234.4,234.4,234.4
XS GIS Cut Line= 2
2350417.47128638647455.9149399792350994.08903876646912.030946467
#Sta/Elev= 30
       0 2989.38    20.8 2979.65    36.7 2973.97    46.3 2972.15   219.7    2970
   240.2 2972.26   260.5 2972.88   272.1 2972.12   317.1 2972.65   334.9 2968.48
   347.9 2969.36   357.6 2967.51   385.8 2965.76   394.3 2964.48   416.1 2964.44
   427.42965.813   436.8 2968.75   465.1 2969.13   473.6 2965.87     533 2970.01
   575.3 2970.45   589.6 2973.25   623.5 2974.44   636.1 2979.65   708.4 2982.94
   731.1  2986.9     748 2991.64     757 2993.08   776.3 3000.13   792.7 3008.03
#Mann= 5 ,-1,0
       0      .1       0   385.8    .045       0   427.4      .1       0
     580     .06       0     720      .1       0
#XS Ineff= 2 , 0
                          534.67         2973.69
Permanent Ineff=
       F       F
Bank Sta=385.8,427.4
XS Rating Curve= 0 ,0
Exp/Cntr(USF)=0,0
Exp/Cntr=0.3,0.1

Type RM Length L Ch R = 1 ,139779  ,193,193,193
XS GIS Cut Line= 3
2350471.52878233647553.6135515412350727.38246807647396.993765964
2351216.72933387647241.415016369
#Sta/Elev= 30
       0 2977.27    31.5 2974.41   155.5 2970.14   288.8 2968.14   316.4 2970.37
   351.2 2966.43     368 2966.97   402.4 2965.17   435.1  2964.3     447 2965.19
   460.3 2967.92   489.7 2967.86   510.7 2967.41   545.7 2963.56     561 2966.69
   573.6 2966.42     582 2964.77   594.6 2968.73   598.8 2969.01   611.4 2965.98
   619.8  2967.3   640.8 2966.27   649.2 2967.59   674.4 2980.08   682.6 2981.82
   712.2 2984.61   720.9 2988.42   733.1 2990.82   796.1 3016.17   813.5 3024.21
#Mann= 5 ,-1,0
       0      .1       0   402.4    .045       0     447      .1       0
  629.98     .06       0  729.98      .1       0
Bank Sta=402.4,447
XS Rating Curve= 0 ,0
Exp/Cntr=0.3,0.1

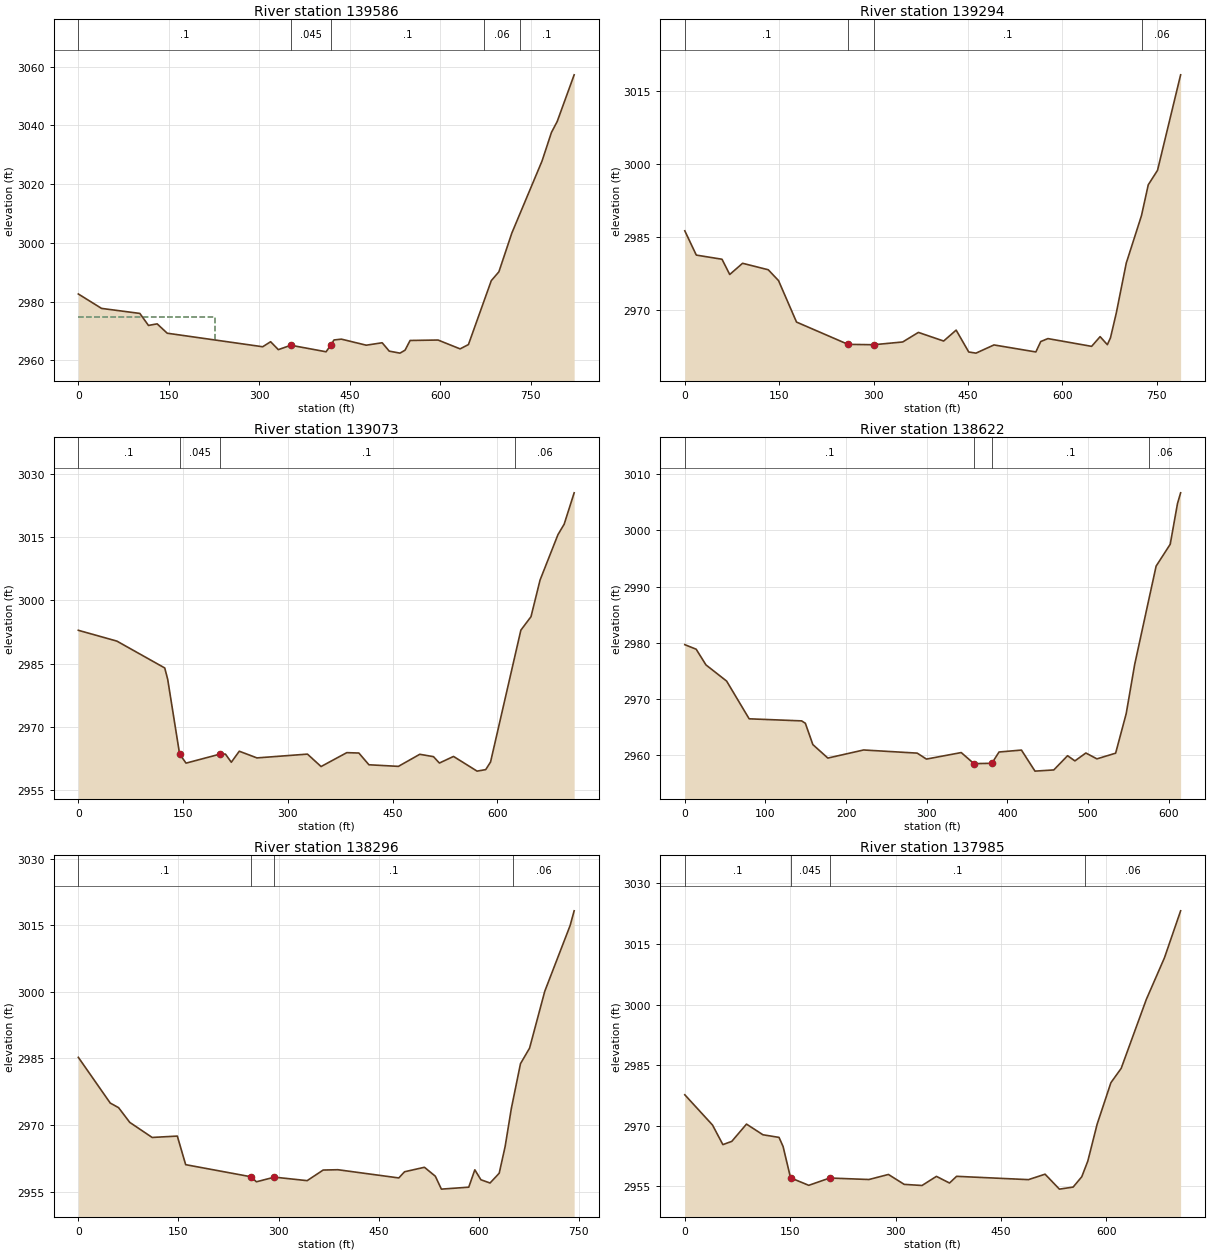
Type RM Length L Ch R = 1 ,139586  ,292.2,292.2,292.2
XS GIS Cut Line= 3
2350571.06815492647730.3749181872350815.31235571647569.224105294
  2351318.908646 647405.55531095
#Sta/Elev= 30
       0  2982.6    38.5 2977.69     102 2975.98   116.3 2971.89   130.7 2972.43
   147.4 2969.24   305.7 2964.63   318.8 2966.34   331.6 2963.65   352.4 2965.14
   410.8 2962.92   418.5 2965.17   423.9 2966.94   436.2 2967.22   477.4 2965.16
   503.8 2965.99   515.5 2963.14   533.3 2962.46   541.7 2963.46   550.1 2966.77
   596.4 2966.92     633 2963.91   646.8 2965.37   684.7 2987.14   697.3 2990.15
   718.7 3003.31   768.8 3027.86   784.5 3037.64     794 3041.34   822.1 3057.23
#Mann= 5 ,-1,0
       0      .1       0   352.4    .045       0   418.5      .1       0
  672.62     .06       0  732.62      .1       0
#XS Ineff= 2 , 0
          226.68 2974.82
Permanent Ineff=
       F       F
Bank Sta=352.4,418.5
XS Rating Curve= 0 ,0
Exp/Cntr(USF)=0,0
Exp/Cntr=0.3,0.1

Type RM Length L Ch R = 1 ,139294  ,221,221,221
XS GIS Cut Line= 3
2350598.22367293647880.9570286732350908.44351488647817.934430086
2351285.32983826647535.141385962
#Sta/Elev= 30
       0 2986.24    18.3 2981.26    59.1 2980.41    71.4 2977.28    91.8 2979.58
   132.6 2978.25   148.9 2976.03   177.5 2967.52259.2981 2962.95300.1978 2962.87
   346.2 2963.44   371.1  2965.4   411.2 2963.63   431.1 2965.87   451.1 2961.38
   462.6 2961.15   491.2 2962.83   557.7 2961.39   565.5 2963.53   576.9 2964.13
   646.3 2962.54   659.8 2964.53   671.3 2962.88   676.3 2964.31   685.5 2969.38
   701.3  2979.6   725.5 2989.35   736.3 2995.68     751 2998.65   787.7 3018.24
#Mann= 4 ,-1,0
       0      .1       0259.2981    .045       0300.1978      .1       0
  726.56     .06       0
Bank Sta=259.2981,300.1978
XS Rating Curve= 0 ,0
Exp/Cntr=0.3,0.1

Type RM Length L Ch R = 1 ,139073  ,450.8,450.8,450.8
XS GIS Cut Line= 3
2350822.71268247648119.1876665822351125.58808136647882.394172906
2351395.42252764647700.668933574
#Sta/Elev= 30
       0 2992.91    55.2 2990.34   123.7 2983.96   127.9 2981.29     145  2963.5
   154.2 2961.35   202.52963.478   210.5 2963.51     219 2961.56   230.4 2964.18
   255.7 2962.59     328 2963.49   347.5 2960.54   384.3 2963.84   401.6 2963.75
     416 2960.96   458.2 2960.58   488.8 2963.45   508.4 2962.89   516.9 2961.37
   537.1 2962.94   570.8 2959.45   583.2 2959.81   590.1 2961.61   633.5 2992.94
     648 2996.14     661 3004.85   686.6 3015.63   695.5 3018.12   709.8 3025.57
#Mann= 4 ,-1,0
       0      .1       0     145    .045       0   202.5      .1       0
  624.45     .06       0
Bank Sta=145,202.5
XS Rating Curve= 0 ,0
Exp/Cntr(USF)=0,0
Exp/Cntr=0.3,0.1

Type RM Length L Ch R = 1 ,138622  ,325.5,325.5,325.5
XS GIS Cut Line= 3
2351023.48729081648348.3402056552351243.76030819648218.012003709
2351559.48496642648047.300415245
#Sta/Elev= 30
       0  2979.7    14.1 2978.89    26.2 2976.11    51.9 2973.22    79.8 2966.52
   144.9 2966.15   149.5 2965.73   158.8 2961.94   177.4 2959.54   221.8 2960.98
   288.2 2960.42   299.7 2959.36   342.8 2960.52   358.6 2958.55   380.8 2958.61
   389.7 2960.62   417.5 2960.96   434.3 2957.22   457.6 2957.43   474.7 2959.96
   483.8 2959.04   497.4 2960.44   511.1  2959.4   534.3 2960.41   547.4 2967.43
   557.9 2976.16   584.5 2993.66     602 2997.55     611 3004.77   614.9 3006.69
#Mann= 4 ,-1,0
       0      .1       0   358.6    .045       0   380.8      .1       0
  575.94     .06       0
Bank Sta=358.6,380.8
XS Rating Curve= 0 ,0
Exp/Cntr(USF)=0,0
Exp/Cntr=0.3,0.1

Type RM Length L Ch R = 1 ,138296  ,311,311,311
XS GIS Cut Line= 4
 2351018.5268952648444.0091845732351214.87043704648383.301549025
2351381.11046629648381.2246084782351706.81350917648203.411918171
#Sta/Elev= 30
       0 2985.26    47.8 2974.96    60.3 2973.92    77.1  2970.6   110.6 2967.21
   148.3 2967.52   160.8 2961.08   258.8 2958.35   266.8 2957.22   293.8 2958.27
   342.8 2957.48   366.8 2959.87   388.9 2959.94   480.1 2958.09   488.7 2959.48
   518.5 2960.49   534.8 2958.48   543.9 2955.57   584.9 2956.01     594 2959.92
   603.1 2957.68   616.8 2956.95   630.5 2959.15   639.4 2965.17   648.7 2973.74
   662.4 2983.83     676 2987.33   698.8 3000.15   736.7 3014.92   742.8 3018.26
#Mann= 4 ,-1,0
       0      .1       0   258.8    .045       0   293.8      .1       0
  651.77     .06       0
Bank Sta=258.8,293.8
XS Rating Curve= 0 ,0
Exp/Cntr=0.3,0.1

Type RM Length L Ch R = 1 ,137985  ,495.6,495.6,495.6
XS GIS Cut Line= 2
2351235.76227369648759.6095152622351813.41219297648354.439115663
#Sta/Elev= 30
       0 2977.67    39.4 2970.19    54.2 2965.33    66.9 2966.14    87.8 2970.41
   111.2 2967.77   134.1 2967.12   139.9 2964.85   150.5 2957.11   176.4 2955.25
   206.2 2957.06     262 2956.69   289.8 2957.94   312.2 2955.49   337.6 2955.21
   358.1 2957.47   376.7 2955.82   386.8 2957.48   489.1 2956.66   512.7 2958.01
   533.1 2954.31   552.6 2954.81   564.9 2957.37   573.5 2961.24   586.8  2970.4
   606.4 2980.67     621 2984.21   656.8 3001.29   682.6 3011.59   705.6 3023.22
#Mann= 4 ,-1,0
       0      .1       0   150.5    .045       0   206.2      .1       0
     570     .06       0
Bank Sta=150.5,206.2
XS Rating Curve= 0 ,0
Exp/Cntr(USF)=0,0
Exp/Cntr=0.3,0.1