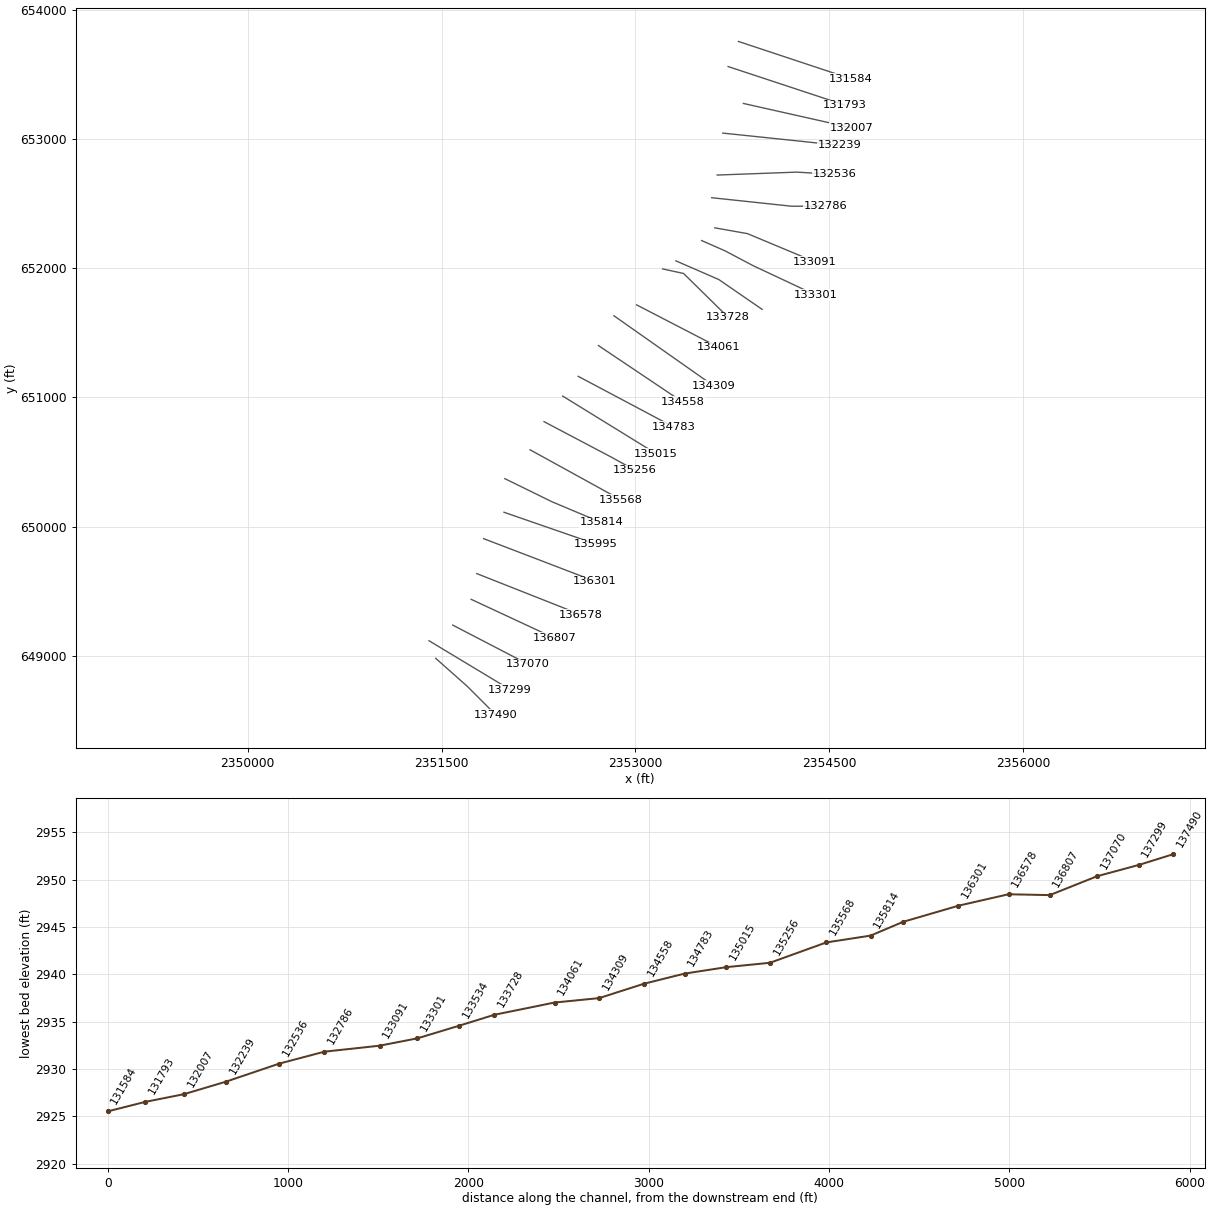
HEC-RAS study LAURELFK.prj: LAURELFK

--- LAURELFK.g01 (geometry) --- (continued)

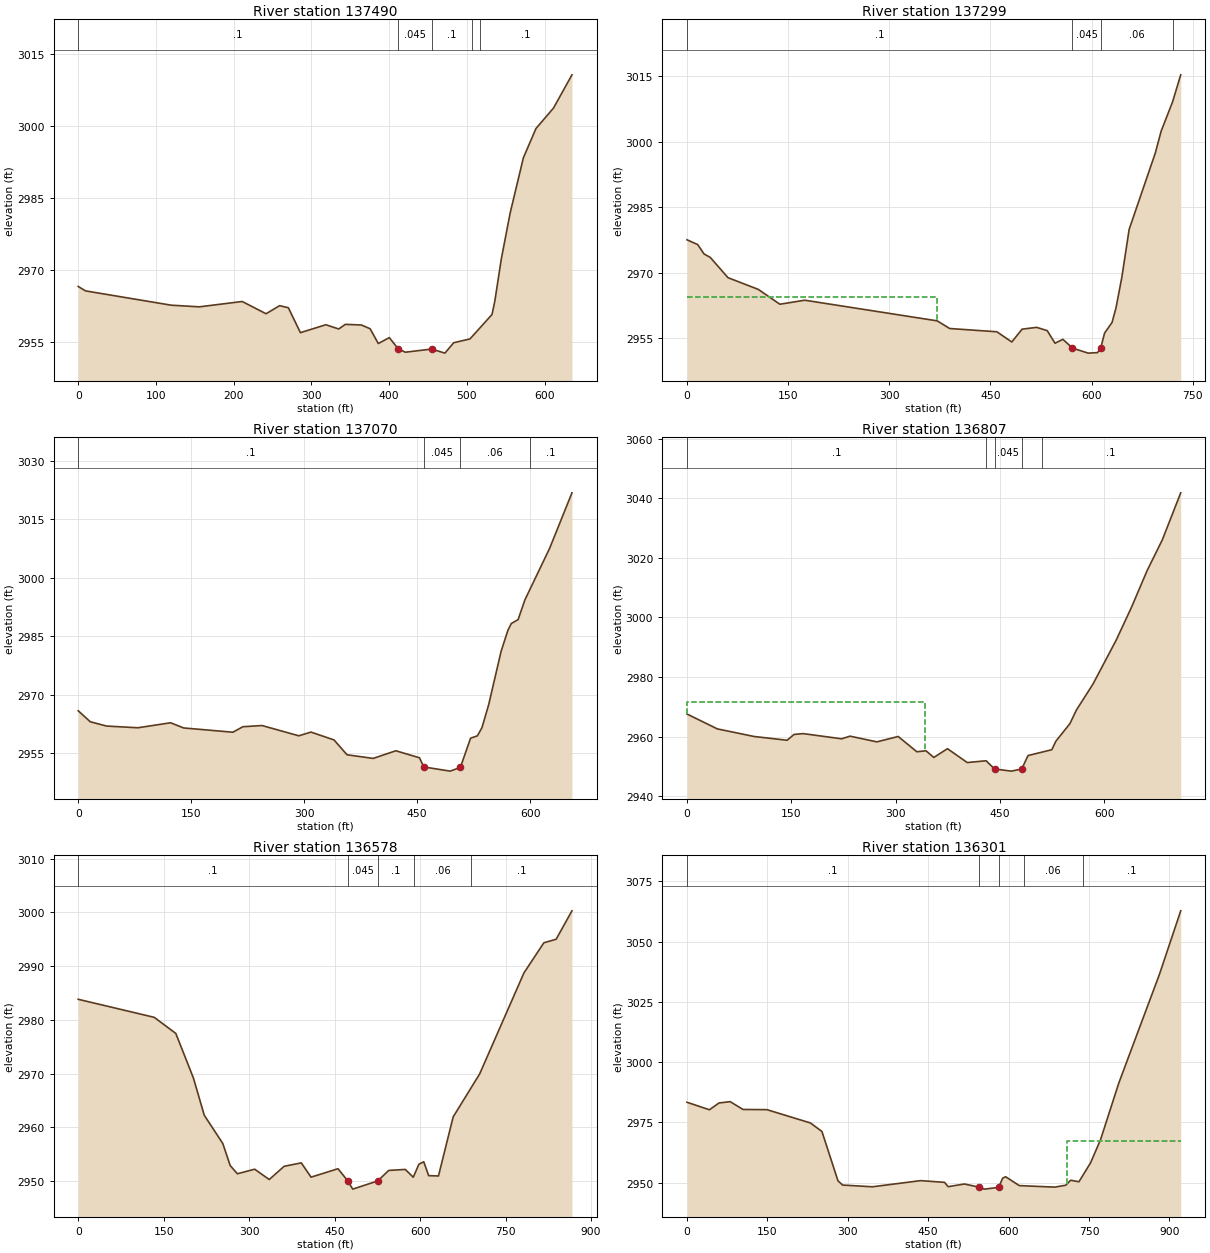
Type RM Length L Ch R = 1 ,137490  ,190.3,190.3,190.3
XS GIS Cut Line= 3
2351454.34721047648980.6170986932351698.48313805648764.015298277
2351916.92054695648545.577889382
#Sta/Elev= 30
       0 2966.57     9.4 2965.65   119.7 2962.67   155.9 2962.33     211 2963.44
   241.7 2960.89   259.1 2962.57   270.4 2962.14   285.9 2956.95   318.6  2958.6
   335.2 2957.72   343.7 2958.68   364.3 2958.55   375.6 2957.77   386.1 2954.69
   400.3 2955.92   411.6 2953.61   420.9 2952.88   454.8 2953.54   471.8 2952.69
   483.1 2954.85   504.1 2955.65   532.4 2960.73     536 2963.47   544.5  2972.4
   555.8 2981.88   572.8 2993.37     589 2999.46   611.6 3003.73   635.3 3010.64
#Mann= 5 ,-1,0
       0      .1       0   411.6    .045       0   454.8      .1       0
  506.37     .06       0  516.37      .1       0
Bank Sta=411.6,454.8
XS Rating Curve= 0 ,0
Exp/Cntr(USF)=0,0
Exp/Cntr=0.3,0.1

Type RM Length L Ch R = 1 ,137299  ,229.3,229.3,229.3
XS GIS Cut Line= 2
2351402.51295254649116.5405313412352029.71704034 648738.93182974
#Sta/Elev= 30
       0 2977.52    15.9 2976.42    25.3 2974.27    34.6 2973.47    60.8 2968.84
   105.7 2966.16   137.7 2962.76   174.7 2963.68     371 2958.95   389.5  2957.2
   459.5 2956.45   481.6 2954.11   496.9 2957.05   518.4 2957.46   534.1 2956.72
   545.7 2953.83   557.4 2954.72   571.6 2952.71   594.9 2951.56   608.9 2951.68
   613.6  2952.8   619.2 2956.16   630.3 2958.59   636.1 2961.91   644.8 2968.94
   655.6 2979.89   694.4 2997.39   703.1 3002.41     720 3009.11   732.1  3015.3
#Mann= 4 ,-1,0
       0      .1       0   571.6    .045       0   613.6     .06       0
     720      .1       0
#XS Ineff= 2 , 0
          371.28 2964.42
Permanent Ineff=
       F       F
Bank Sta=571.6,613.6
XS Rating Curve= 0 ,0
Exp/Cntr=0.3,0.1

Type RM Length L Ch R = 1 ,137070  ,263,263,263
XS GIS Cut Line= 2
2351585.94447506649237.7155947932352167.59819035 648935.55782062
#Sta/Elev= 30
       0 2965.86      16 2963.04    37.6 2961.94    79.2  2961.5   122.6 2962.78
     140 2961.45   205.4 2960.36   218.6 2961.77   244.1 2962.07   292.8 2959.44
     309 2960.39   339.6 2958.38   356.9 2954.57   391.6 2953.64   421.7  2955.6
     453 2953.81   458.9 2951.45   493.8 2950.38   507.4 2951.34   520.9 2958.83
   529.9 2959.42     536 2961.53   544.9 2967.39   561.4 2981.08   570.5 2986.52
     575 2988.24     584 2989.24     593 2994.28   625.9 3007.54   655.5 3021.75
#Mann= 4 ,-1,0
       0      .1       0   458.9    .045       0   507.4     .06       0
     600      .1       0
Bank Sta=458.9,507.4
XS Rating Curve= 0 ,0
Exp/Cntr(USF)=0,0
Exp/Cntr=0.3,0.1

Type RM Length L Ch R = 1 ,136807  ,228.8,228.8,228.8
XS GIS Cut Line= 2
2351728.64072846649437.0071998582352372.14258722649137.435784956
#Sta/Elev= 30
       0 2967.55    43.6 2962.56    96.6    2960     144 2958.74   153.9  2960.7
   167.1 2960.97   222.3 2959.23   234.4 2960.12     273  2958.2   303.6 2960.01
   330.4 2954.89   343.6  2955.2   354.8 2952.97   374.5 2955.91   402.9 2951.26
     430 2951.86   442.1 2949.11   466.2 2948.38   481.2 2949.09   490.3 2953.61
   524.5 2955.57   530.3 2958.42   550.5 2964.33   559.8 2968.88   583.6 2977.58
   617.2 2992.43   639.3 3003.52   661.3 3015.59   683.4 3026.05   709.8 3041.79
#Mann= 5 ,-1,0
       0      .1       0     430     .06       0   442.1    .045       0
   481.2     .06       0     510      .1       0
#XS Ineff= 2 , 0
          342.28 2971.42
Permanent Ineff=
       F       F
Bank Sta=442.1,481.2
XS Rating Curve= 0 ,0
Exp/Cntr=0.3,0.1

Type RM Length L Ch R = 1 ,136578  ,277.8,277.8,277.8
XS GIS Cut Line= 2
2351772.11660128649636.161117831 2352578.0548802649317.623607589
#Sta/Elev= 30
       0 2983.83   133.4 2980.47   171.3 2977.47   202.2 2969.16   221.2 2962.24
   253.8 2956.96   266.7 2952.87   279.3 2951.33   309.7 2952.18   335.3 2950.26
   361.4 2952.72   391.5 2953.36   408.7  2950.7     456 2952.27   473.2 2949.99
   481.8 2948.47   525.72949.996   544.9 2951.95     574 2952.14   588.1 2950.69
   597.9 2953.11   606.5 2953.56   615.1 2950.98   632.3 2950.92   658.1 2961.92
   704.6 2969.93   782.3 2988.74   817.3 2994.36   838.8 2995.01   866.6 3000.31
#Mann= 5 ,-1,0
       0      .1       0   473.2    .045       0   525.7      .1       0
     590     .06       0     690      .1       0
Bank Sta=473.2,525.7
XS Rating Curve= 0 ,0
Exp/Cntr(USF)=0,0
Exp/Cntr=0.3,0.1

Type RM Length L Ch R = 1 ,136301  ,306,306,306
XS GIS Cut Line= 3
2351824.99247044 649906.472543012352215.78465592649757.138629029
2352685.23685663649576.914529562
#Sta/Elev= 30
       0 2983.33    41.9 2980.21    59.7 2983.03    80.5 2983.59   104.5 2980.34
   149.1 2980.26   230.4 2974.73   251.8 2971.19   281.7 2950.71   290.3 2948.95
     346 2948.23   435.9 2950.79   480.5 2950.08   487.3 2948.28   517.7 2949.39
   545.6 2948.05   554.8 2947.26   581.6 2947.98   588.9 2951.77   594.4 2952.41
   620.1 2948.72   686.1 2948.09   706.6 2948.88   715.8 2950.95   731.3 2950.33
     753 2958.19   771.6  2967.8   805.6 2991.27   881.5 3036.45   921.2 3062.82
#Mann= 5 ,-1,0
       0      .1       0   545.6    .045       0   581.6      .1       0
  628.35     .06       0  738.35      .1       0
#XS Ineff= 2 , 0
                          709.73         2967.42
Permanent Ineff=
       F       F
Bank Sta=545.6,581.6
XS Rating Curve= 0 ,0
Exp/Cntr=0.3,0.1

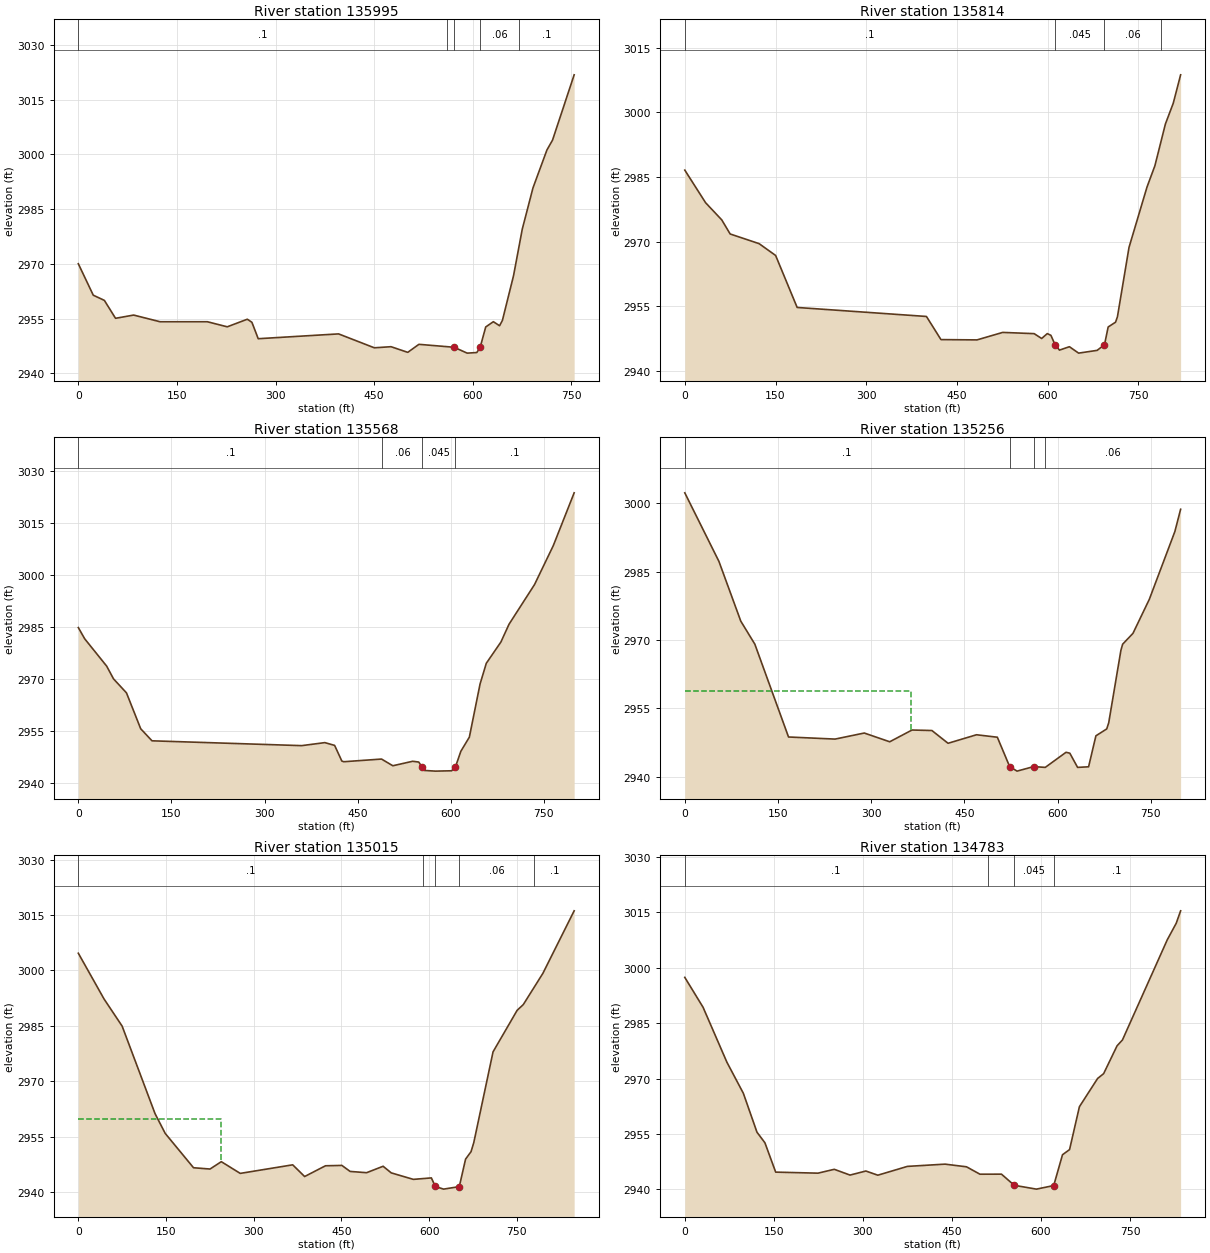
Type RM Length L Ch R = 1 ,135995  ,181.1,181.1,181.1
XS GIS Cut Line= 2
2351982.72409196650110.7006566492352695.31284272649863.938474407
#Sta/Elev= 30
       0 2970.05    22.7 2961.44    39.6 2960.01    56.6  2955.1    84.1 2955.99
   124.3 2954.16   196.3 2954.16   226.5 2952.77     257 2954.85     264 2954.01
   273.6 2949.51   395.8 2950.83   450.2 2947.02   475.6 2947.32     501 2945.77
     518 2947.97   571.4 2947.17   591.4 2945.56     606 2945.72   611.1 2947.12
   619.6 2952.73   631.2 2954.17   640.7 2953.06     645 2954.54   661.9 2966.78
   675.2 2979.54   691.5 2990.85   712.7 3001.23   721.2 3003.92   754.1 3021.82
#Mann= 5 ,-1,0
       0      .1       0     560     .06       0   571.4    .045       0
   611.1     .06       0     670      .1       0
Bank Sta=571.4,611.1
XS Rating Curve= 0 ,0
Exp/Cntr(USF)=0,0
Exp/Cntr=0.3,0.1

Type RM Length L Ch R = 1 ,135814  ,245.1,245.1,245.1
XS GIS Cut Line= 3
2351989.30875539650370.7185008892352355.76961202650191.209229384
  2352735.358983650031.536200711
#Sta/Elev= 30
       0 2986.58    34.4 2979.01    61.1 2975.03      75 2971.76   122.9 2969.51
   150.2 2966.77   185.8  2954.7   399.6 2952.61   423.6 2947.24   483.2 2947.17
   525.7 2948.91   577.7 2948.62   590.1  2947.5   599.4 2948.63   605.4 2948.23
   612.5 2945.99   619.6  2944.8     636 2945.59   651.2  2944.1   681.8 2944.74
     694 2946.04   700.1 2950.17   712.3 2951.28   715.4 2952.53   734.6 2968.66
   764.3 2982.65   777.4 2987.61   794.7 2997.27   807.7  3002.1   819.9  3008.7
#Mann= 4 ,-1,0
       0      .1       0   612.5    .045       0     694     .06       0
  788.07      .1       0
Bank Sta=612.5,694
XS Rating Curve= 0 ,0
Exp/Cntr=0.3,0.1

Type RM Length L Ch R = 1 ,135568  ,312.8,312.8,312.8
XS GIS Cut Line= 2
2352184.16260807650594.1530953272352884.16145158650208.901933255
#Sta/Elev= 30
       0 2984.77    10.3 2981.53    45.7 2973.65    56.7 2969.99    77.6 2965.94
   100.5  2955.6   118.7 2952.12     360 2950.73   397.2  2951.6     413  2950.8
   424.6  2946.3   427.7 2946.09   488.6 2946.86   506.8 2944.93   538.8 2946.22
   548.5    2946   554.4 2944.45   557.3 2943.58   575.3 2943.38   601.5 2943.48
   607.4 2944.43   616.4  2949.1   630.1 2953.17   647.4 2968.52   657.4 2974.47
     681 2980.62     694 2985.72   735.1 2997.16   765.3 3008.37     799 3023.63
#Mann= 4 ,-1,0
       0      .1       0     490     .06       0   554.4    .045       0
   607.4      .1       0
Bank Sta=554.4,607.4
XS Rating Curve= 0 ,0
Exp/Cntr(USF)=0,0
Exp/Cntr=0.3,0.1

Type RM Length L Ch R = 1 ,135256  ,241,241,241
XS GIS Cut Line= 3
2352292.50539964650811.7277589472352812.74281451 650537.40154301
2352996.30166937 650436.12437275
#Sta/Elev= 30
       0  3002.3    54.9 2987.26    90.1 2974.14   112.7 2969.09   166.9 2948.72
   241.8 2948.26   288.8 2949.59   329.7 2947.67   365.6 2950.25   397.6 2950.14
   423.6 2947.34   469.4 2949.21   502.9 2948.67   522.7 2942.23   534.6 2941.23
   561.2 2942.22     580 2942.05   613.4 2945.36   619.5 2945.17     632 2942.05
   649.7 2942.18   661.5 2948.98   678.9 2950.49   682.1 2951.83   701.7 2967.73
   704.5 2969.08   721.1 2971.46   747.4 2978.92   788.5 2993.79   797.8 2998.69
#Mann= 4 ,-1,0
       0      .1       0   522.7    .045       0   561.2      .1       0
     580     .06       0
#XS Ineff= 2 , 0
           363.6 2958.91
Permanent Ineff=
       F       F
Bank Sta=522.7,561.2
XS Rating Curve= 0 ,0
Exp/Cntr=0.3,0.1

Type RM Length L Ch R = 1 ,135015  ,231.5,231.5,231.5
XS GIS Cut Line= 2
2352436.44521167651009.9098314582353158.26656109650565.066441702
#Sta/Elev= 30
       0 3004.64    43.9 2992.27    74.9 2984.91   131.2  2961.2   148.6 2955.85
     197 2946.56   225.2 2946.21   244.5  2948.2   276.9 2945.03   366.6 2947.35
     387 2944.18   422.6 2947.09   450.7 2947.19   464.8 2945.56     493 2945.22
   521.2 2946.96   535.1 2945.17   572.9 2943.41   603.7 2943.81   610.5 2941.49
   624.6 2940.77   651.5 2941.45   662.2 2948.89   671.6 2950.92   676.3  2953.4
   709.2 2977.94   750.4 2989.18   760.9 2990.73   794.3 2999.16   847.9 3016.12
#Mann= 5 ,-1,0
       0      .1       0     590     .06       0   610.5    .045       0
   651.5     .06       0     780      .1       0
#XS Ineff= 2 , 0
          243.29 2959.79
Permanent Ineff=
       F       F
Bank Sta=610.5,651.5
XS Rating Curve= 0 ,0
Exp/Cntr(USF)=0,0
Exp/Cntr=0.3,0.1

Type RM Length L Ch R = 1 ,134783  ,225.3,225.3,225.3
XS GIS Cut Line= 2
2352556.96756791651162.3977823332353294.71670211650770.703615396
#Sta/Elev= 30
       0 2997.38    30.8 2989.29    70.8 2974.48    98.7    2966   121.6 2955.49
     135 2952.63   153.1 2944.69   224.4 2944.41   251.8 2945.45   278.4 2943.89
     305 2944.99   325.2 2943.86     375 2946.24   438.4 2946.85   474.6 2946.13
   497.2 2944.13   533.5 2944.14   555.1 2941.12   592.4 2940.09   621.5 2941.06
   636.3 2949.39   648.2 2950.79   664.8 2962.39   695.5 2970.04   705.6 2971.33
   728.2 2978.86   737.3 2980.45   812.9 3007.58   827.9 3012.03   835.3 3015.39
#Mann= 4 ,-1,0
       0      .1       0     510     .06       0   555.1    .045       0
   621.5      .1       0
Bank Sta=555.1,621.5
XS Rating Curve= 0 ,0
Exp/Cntr=0.3,0.1

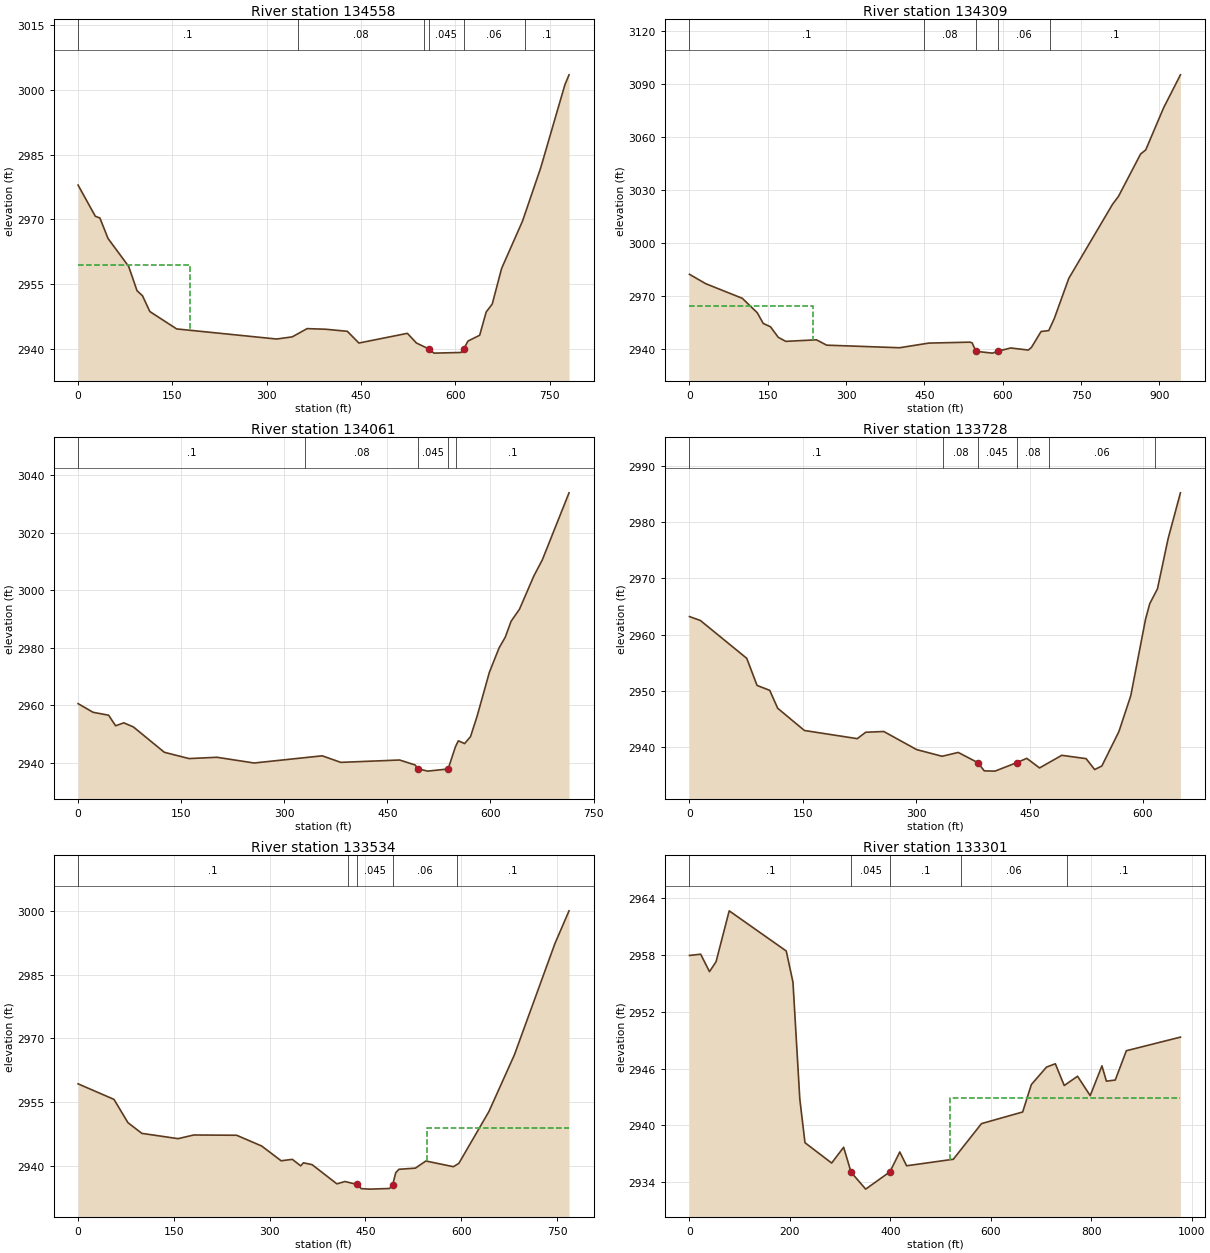
Type RM Length L Ch R = 1 ,134558  ,248.7,248.7,248.7
XS GIS Cut Line= 2
2352713.45836823651400.5300434742353361.58679384650965.422848664
#Sta/Elev= 30
       0 2977.97    27.4 2970.75    34.7 2970.34    47.6  2965.6    80.4 2959.13
    93.7  2953.5   102.4 2952.32   114.1 2948.66   156.7 2944.63   315.7 2942.29
   340.5 2942.79   364.1  2944.7   393.5 2944.56   428.1 2944.08   446.5 2941.36
   523.6 2943.61     538 2941.36   557.3 2940.02   565.8 2939.02   608.8 2939.17
   613.3 2940.03   619.9 2941.81   638.5 2943.16   648.9 2948.56   658.5  2950.4
   673.4 2958.65   706.7 2969.65   735.6 2981.99     774 3001.22   780.6 3003.53
#Mann= 6 ,-1,0
       0      .1       0     350     .08       0     550      .1       0
   557.3    .045       0   613.3     .06       0     710      .1       0
#XS Ineff= 2 , 0
          178.52 2959.53
Permanent Ineff=
       F       F
Bank Sta=557.3,613.3
XS Rating Curve= 0 ,0
Exp/Cntr(USF)=0,0
Exp/Cntr=0.3,0.1

Type RM Length L Ch R = 1 ,134309  ,247.7,247.7,247.7
XS GIS Cut Line= 2
2352833.18011783 651631.036949272353602.59119643651090.172035983
#Sta/Elev= 30
       0 2982.11    31.1  2976.8   101.1 2968.54   129.8 2960.38   141.3 2954.31
   155.2  2952.4     170 2946.47   184.4 2944.16   243.2 2945.03   262.8 2942.01
   402.6 2940.55   458.4 2943.18   537.5 2943.71   541.5 2943.28   548.82938.519
   580.5  2937.5   590.4 2938.55   615.3 2940.41   649.1 2939.24   655.2 2940.78
   673.5 2949.74   688.2 2950.26   698.8 2957.03   726.6 2979.79   810.4 3021.72
   821.8 3026.22   864.2  3050.2     874 3052.51   908.2  3076.3   940.5 3095.01
#Mann= 5 ,-1,0
       0      .1       0     450     .08       0   548.8    .045       0
   590.4     .06       0     690      .1       0
#XS Ineff= 2 , 0
          236.86 2964.32
Permanent Ineff=
       F       F
Bank Sta=548.8,590.4
XS Rating Curve= 0 ,0
Exp/Cntr=0.3,0.1

Type RM Length L Ch R = 1 ,134061  ,332.9,332.9,332.9
XS GIS Cut Line= 2
2353008.72333225651715.3149592542353643.02803969 651386.94499817
#Sta/Elev= 30
       0 2960.52    21.9  2957.5    44.4  2956.5    54.6 2952.82    66.5 2953.84
    80.5 2952.41   125.5 2943.59   161.5  2941.4   202.1 2941.85   256.1 2939.86
   355.2 2942.36   382.2 2940.08   467.8  2940.9   490.3 2939.18   494.8 2937.83
   508.7 2937.03   538.4 2937.78   548.9 2945.43   553.2 2947.58   562.4 2946.63
     571 2949.06   580.4 2956.02   598.4 2971.43   612.5 2979.91   621.5 2983.65
     630  2989.2   642.2  2993.4     663 3004.91   675.5 3010.61   714.3 3033.91
#Mann= 5 ,-1,0
       0      .1       0     330     .08       0   494.8    .045       0
   538.4     .06       0     550      .1       0
Bank Sta=494.8,538.4
XS Rating Curve= 0 ,0
Exp/Cntr(USF)=0,0
Exp/Cntr=0.3,0.1

Type RM Length L Ch R = 1 ,133728  ,194.7,194.7,194.7
XS GIS Cut Line= 3
2353210.11619542651993.531872632  2353371.975514651958.304076974
2353717.16556255651619.098773405
#Sta/Elev= 30
       0  2963.2    14.4 2962.51    75.8 2955.78    89.4 2950.97   106.2 2950.09
   116.7 2946.91   152.1 2942.96     222 2941.51   233.2 2942.65   257.1 2942.78
   300.5 2939.57   334.2 2938.38   355.6 2939.06   381.6 2937.24     390 2935.79
   404.2 2935.74  433.22 2937.26   446.3 2938.01   463.2 2936.31   492.6 2938.55
   524.8 2937.96   536.1 2936.02   545.6 2936.65   568.2 2942.77   583.9 2949.14
   603.4 2962.71     609  2965.5   619.2 2968.13   633.3 2977.05   649.6 2985.19
#Mann= 6 ,-1,0
       0      .1       0  335.65     .08       0   381.6    .045       0
  433.22     .08       0  475.65     .06       0  615.65      .1       0
Bank Sta=381.6,433.22
XS Rating Curve= 0 ,0
Exp/Cntr=0.3,0.1

Type RM Length L Ch R = 1 ,133534  ,232.4,232.4,232.4
XS GIS Cut Line= 3
2353312.61851363652055.9223101912353645.06760466651911.113196919
2353979.55626067651680.642354667
#Sta/Elev= 30
       0 2959.33    56.2 2955.68    78.1  2950.2    99.9 2947.69   156.6 2946.45
   181.1 2947.31   248.2 2947.25   287.5 2944.72     318 2941.25   335.5 2941.59
   348.6 2940.06   352.9 2940.77   366.4 2940.35   405.3 2935.83     418 2936.38
   436.5 2935.71   443.6  2934.7   457.7 2934.59   487.8 2934.74   492.7 2935.65
   497.5 2938.46   502.4 2939.25   528.2 2939.52   544.6  2941.2   587.7 2939.86
   596.3 2940.66   643.3 2952.81   683.3 2966.16   746.7 2992.29   768.8 2999.98
#Mann= 5 ,-1,0
       0      .1       0  422.62     .06       0   436.5    .045       0
   492.7     .06       0  592.62      .1       0
#XS Ineff= 2 , 0
                          546.31         2948.91
Permanent Ineff=
       F       F
Bank Sta=436.5,492.7
XS Rating Curve= 0 ,0
Exp/Cntr(USF)=0,0
Exp/Cntr=0.3,0.1

Type RM Length L Ch R = 1 ,133301  ,210,210,210
XS GIS Cut Line= 4
2353511.72120917652212.9766608762353691.64432175  652133.9839041
2353907.70254966652019.787568443 2354393.6525483  651791.6340959
#Sta/Elev= 30
       0 2957.97    22.3  2958.1    39.8 2956.26    52.9  2957.3    79.1 2962.69
   192.7 2958.44   206.1 2955.14   219.7 2942.78     230 2938.16   283.1 2936.01
     307 2937.68   321.8 2935.04   350.9 2933.25   399.12935.078   418.8 2937.18
   432.4 2935.72   525.4 2936.41   581.5 2940.18   663.5 2941.41   680.8 2944.31
     711 2946.16   728.6 2946.51   746.3 2944.21   772.8 2945.19     798 2943.14
   821.4 2946.29   830.3 2944.67   847.9 2944.79     870 2947.89   977.7 2949.33
#Mann= 5 ,-1,0
       0      .1       0   321.8    .045       0   399.1      .1       0
  540.88     .06       0  750.88      .1       0
#XS Ineff= 2 , 0
                          518.37         2942.93
Permanent Ineff=
       F       F
Bank Sta=321.8,399.1
XS Rating Curve= 0 ,0
Exp/Cntr=0.3,0.1

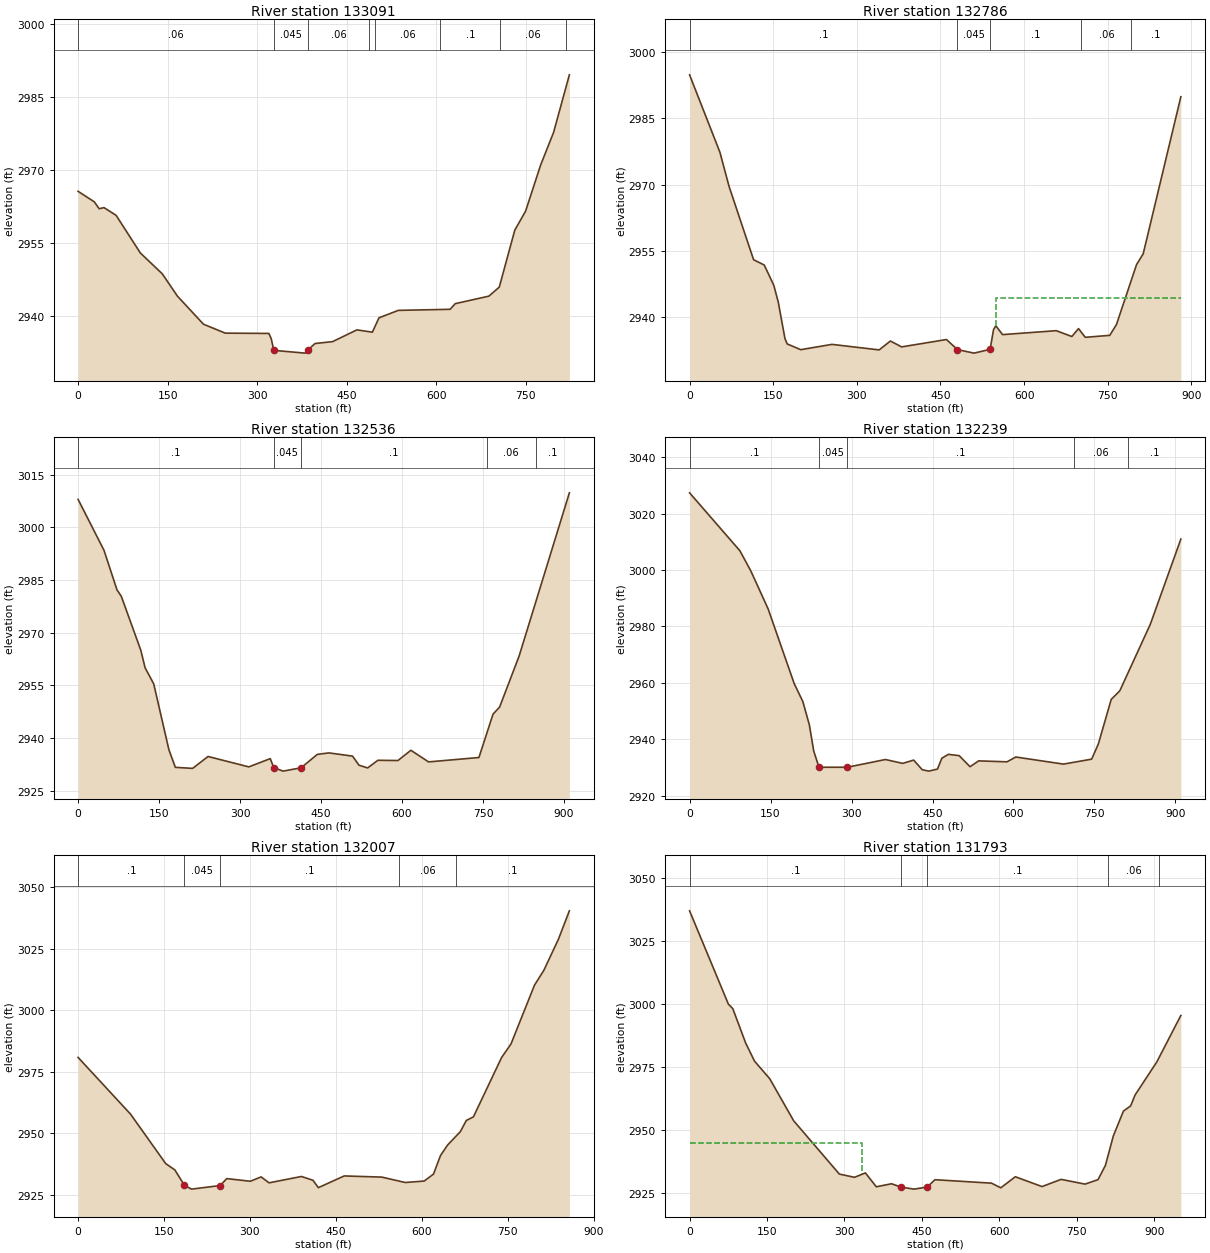
Type RM Length L Ch R = 1 ,133091  ,305.7,305.7,305.7
XS GIS Cut Line= 3
 2353613.4526378652311.3783674032353866.35869478652266.507937938
2354388.48732855652048.274485541
#Sta/Elev= 30
       0 2965.66    27.1 2963.51    35.3 2962.09    43.4 2962.32    63.7 2960.73
   104.3 2953.01   140.9 2948.75   166.4 2944.16     210  2938.4   246.5 2936.57
   319.5 2936.51   323.5 2935.42   327.82933.037   380.2 2932.47   384.8 2933.12
   396.8 2934.44   426.3 2934.83   466.9 2937.24   492.9 2936.77   503.9 2939.71
   536.3 2941.24     623 2941.46   631.7 2942.62     688 2944.16   705.4 2946.01
   731.4  2957.7   749.4 2961.57   774.7 2971.06   796.4 2977.76   822.8 2989.56
#Mann= 8 ,-1,0
       0     .06       0   327.8    .045       0   384.8     .06       0
  486.86      .1       0  496.86     .06       0  606.86      .1       0
  706.86     .06       0  816.86      .1       0
Bank Sta=327.8,384.8
XS Rating Curve= 0 ,0
Exp/Cntr(USF)=0,0
Exp/Cntr=0.3,0.1

Type RM Length L Ch R = 1 ,132786  ,250.1,250.1,250.1
XS GIS Cut Line= 3
     2353590.044      652544.3762354209.07807257      652478.453
2354467.62246371652479.580925806
#Sta/Elev= 30
       0 2994.83    54.4 2977.31    70.8 2969.57   114.8 2952.98   133.9 2951.78
     151 2947.21     159 2943.43   171.1  2935.1   175.1 2933.92   199.3 2932.62
   255.4 2933.82     340 2932.57   360.2 2934.58   380.3 2933.25   460.7 2934.92
   480.5 2932.63   510.2 2931.84     539  2932.7   545.2 2937.18   549.2 2938.04
   561.3 2936.03   657.6 2936.92   685.6  2935.6   697.6 2937.39   709.6 2935.42
   753.6 2935.86   765.6  2938.3   801.6 2951.86   813.6 2954.33   881.1 2989.87
#Mann= 5 ,-1,0
       0      .1       0   480.5    .045       0     539      .1       0
  702.53     .06       0  792.53      .1       0
#XS Ineff= 2 , 0
                          549.46         2944.42
Permanent Ineff=
       F       F
Bank Sta=480.5,539
XS Rating Curve= 0 ,0
Exp/Cntr=0.3,0.1

Type RM Length L Ch R = 1 ,132536  ,296.2,296.2,296.2
XS GIS Cut Line= 3
2353632.19201531652719.7763071132354249.09747092652742.438140176
2354541.18331928652724.812270016
#Sta/Elev= 30
       0    3008      48 2993.48      72 2982.23      80  2980.4   116.1 2965.04
   124.1 2960.02   140.1 2955.42   168.1 2936.73   180.1 2931.66   212.1 2931.36
   240.7 2934.75   316.2 2931.79   355.9 2934.14   362.42931.607   379.7 2930.58
     4132931.532   443.1 2935.35   464.6 2935.77   508.3 2934.86   520.3 2932.26
   536.3 2931.49   555.3 2933.67   592.4  2933.6   616.4 2936.52   649.1 2933.21
   742.4 2934.46   768.5 2946.81   780.7 2948.83   816.8 2963.35   909.9 3009.87
#Mann= 5 ,-1,0
       0      .1       0   362.4    .045       0     413      .1       0
  757.32     .06       0  847.32      .1       0
Bank Sta=362.4,413
XS Rating Curve= 0 ,0
Exp/Cntr(USF)=0,0
Exp/Cntr=0.3,0.1

Type RM Length L Ch R = 1 ,132239  ,232.3,232.3,232.3
XS GIS Cut Line= 3
2353675.46007257653044.3400524012354035.03848064653006.905647577
2354580.47299838652949.514204034
#Sta/Elev= 30
       0 3027.43    93.2 3006.87   113.3 2999.77   145.5 2986.24   193.8 2959.73
   209.8 2953.36   221.9 2945.06     230 2935.76   239.7 2930.04   292.12930.045
   362.7 2932.79   394.8 2931.42   415.1 2932.59     431 2929.16   443.1 2928.67
   459.2  2929.4   467.2 2933.23   479.3 2934.63   499.4 2934.16   519.5 2930.24
   535.6 2932.31   587.9 2931.97   604.3 2933.68   692.5 2931.16   744.8 2932.92
   757.2 2938.31     781 2954.12   796.9 2957.17   853.4 2980.77     910 3011.01
#Mann= 5 ,-1,0
       0      .1       0   239.7    .045       0   292.1      .1       0
  711.52     .06       0  811.52      .1       0
Bank Sta=239.7,292.1
XS Rating Curve= 0 ,0
Exp/Cntr=0.3,0.1

Type RM Length L Ch R = 1 ,132007  ,214,214,214
XS GIS Cut Line= 2
 2353834.9503513653273.7652315242354671.59104086653085.712966441
#Sta/Elev= 30
       0 2980.89    91.5 2957.85   152.9 2937.74   168.9 2935.16   185.7 2928.86
     198 2927.35   248.12928.804   259.5 2931.63   300.5 2930.55   319.5 2932.32
   333.3 2929.91   389.8 2932.49   409.9 2930.96   419.4 2927.95   464.5 2932.71
   530.1 2932.24   571.1 2930.04     604 2930.63   620.3 2933.44   632.6 2941.02
   644.9 2945.26   667.2 2950.72   677.7 2955.28     690 2956.72   739.2 2980.84
   755.6 2986.35   796.6 3010.26     813 3016.33   838.4 3028.94   857.5 3040.49
#Mann= 5 ,-1,0
       0      .1       0   185.7    .045       0   248.1      .1       0
     560     .06       0     660      .1       0
Bank Sta=185.7,248.1
XS Rating Curve= 0 ,0
Exp/Cntr(USF)=0,0
Exp/Cntr=0.3,0.1

Type RM Length L Ch R = 1 ,131793  ,209.3,209.3,209.3
XS GIS Cut Line= 2
2353716.72695261653559.2262855452354620.42155563653260.895837369
#Sta/Elev= 30
       0 3037.05    75.2 2999.98    83.7 2998.22   108.6 2984.58   125.8 2977.36
   155.3 2970.37   201.6 2953.69   290.1 2932.52   319.6 2931.23   340.6 2932.98
   361.7 2927.47   391.2 2928.67   409.7 2927.34     435 2926.54   460.4 2927.38
   475.4 2930.28   584.9 2928.91   602.9 2927.06     631 2931.46   682.8 2927.55
   719.7 2930.42   766.1 2928.53   791.3 2930.31   805.6    2936   820.8 2947.59
   840.4 2957.51   854.5  2959.6   862.9 2963.88   905.1 2977.03   951.7  2995.5
#Mann= 5 ,-1,0
       0      .1       0   409.7    .045       0   460.4      .1       0
     810     .06       0     910      .1       0
#XS Ineff= 2 , 0
          333.89 2944.99
Permanent Ineff=
       F       F
Bank Sta=409.7,460.4
XS Rating Curve= 0 ,0
Exp/Cntr=0.3,0.1

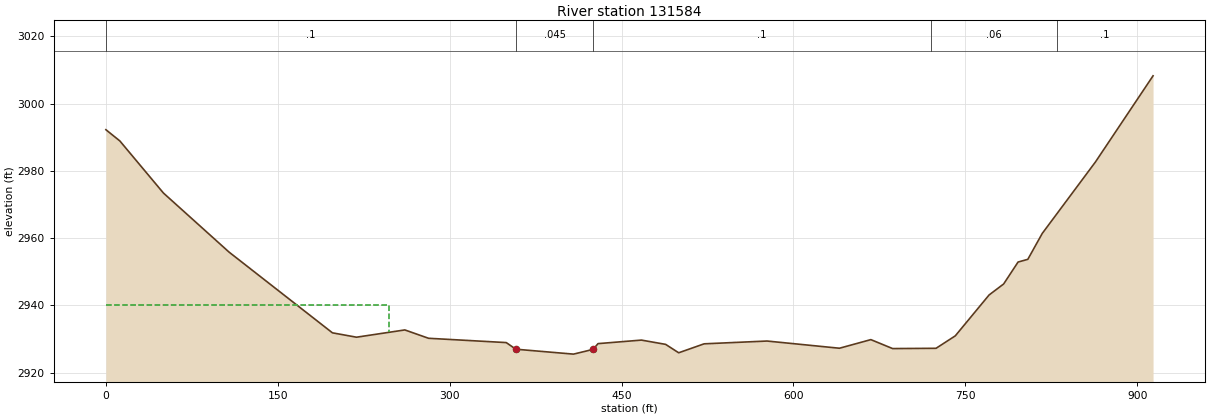
Type RM Length L Ch R = 1 ,131584  ,230.4,230.4,230.4
XS GIS Cut Line= 2
2353796.57233802653753.490397552 2354663.9154382653465.655297935
#Sta/Elev= 30
       0 2992.23    12.2 2988.88    50.2 2973.41   107.5 2955.85   197.7 2931.86
   218.7 2930.56   260.9 2932.72   281.6 2930.24   349.4 2928.96   357.8 2926.99
   408.1 2925.53   425.2 2926.94   429.5 2928.65   467.4  2929.7   488.5 2928.43
   499.9 2925.93   522.1 2928.59     577 2929.42   640.2 2927.28   667.6 2929.84
   686.6 2927.18   724.5 2927.26   741.3 2930.96   770.8 2943.11   783.5 2946.38
   796.1  2952.9   804.6  2953.7   817.2  2961.4   863.6 2982.63   913.9 3008.24
#Mann= 5 ,-1,0
       0      .1       0   357.8    .045       0   425.2      .1       0
     720     .06       0     830      .1       0
#XS Ineff= 2 , 0
          246.64 2940.21
Permanent Ineff=
       F       F
Bank Sta=357.8,425.2
XS Rating Curve= 0 ,0
Exp/Cntr(USF)=0,0
Exp/Cntr=0.3,0.1