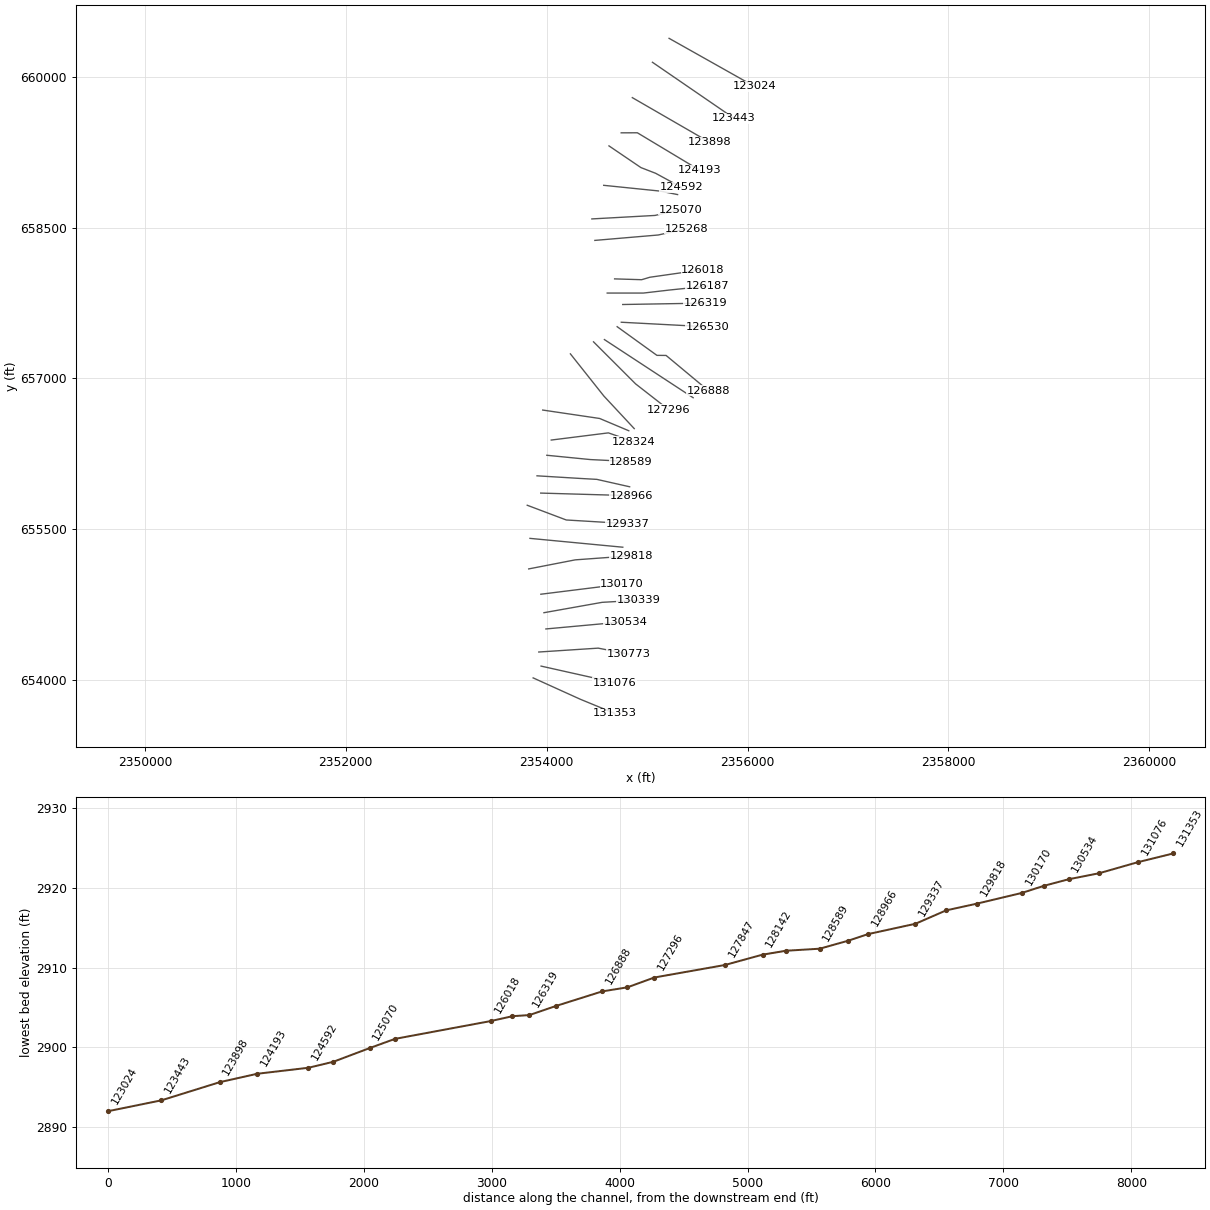
HEC-RAS study LAURELFK.prj: LAURELFK

--- LAURELFK.g01 (geometry) --- (continued)

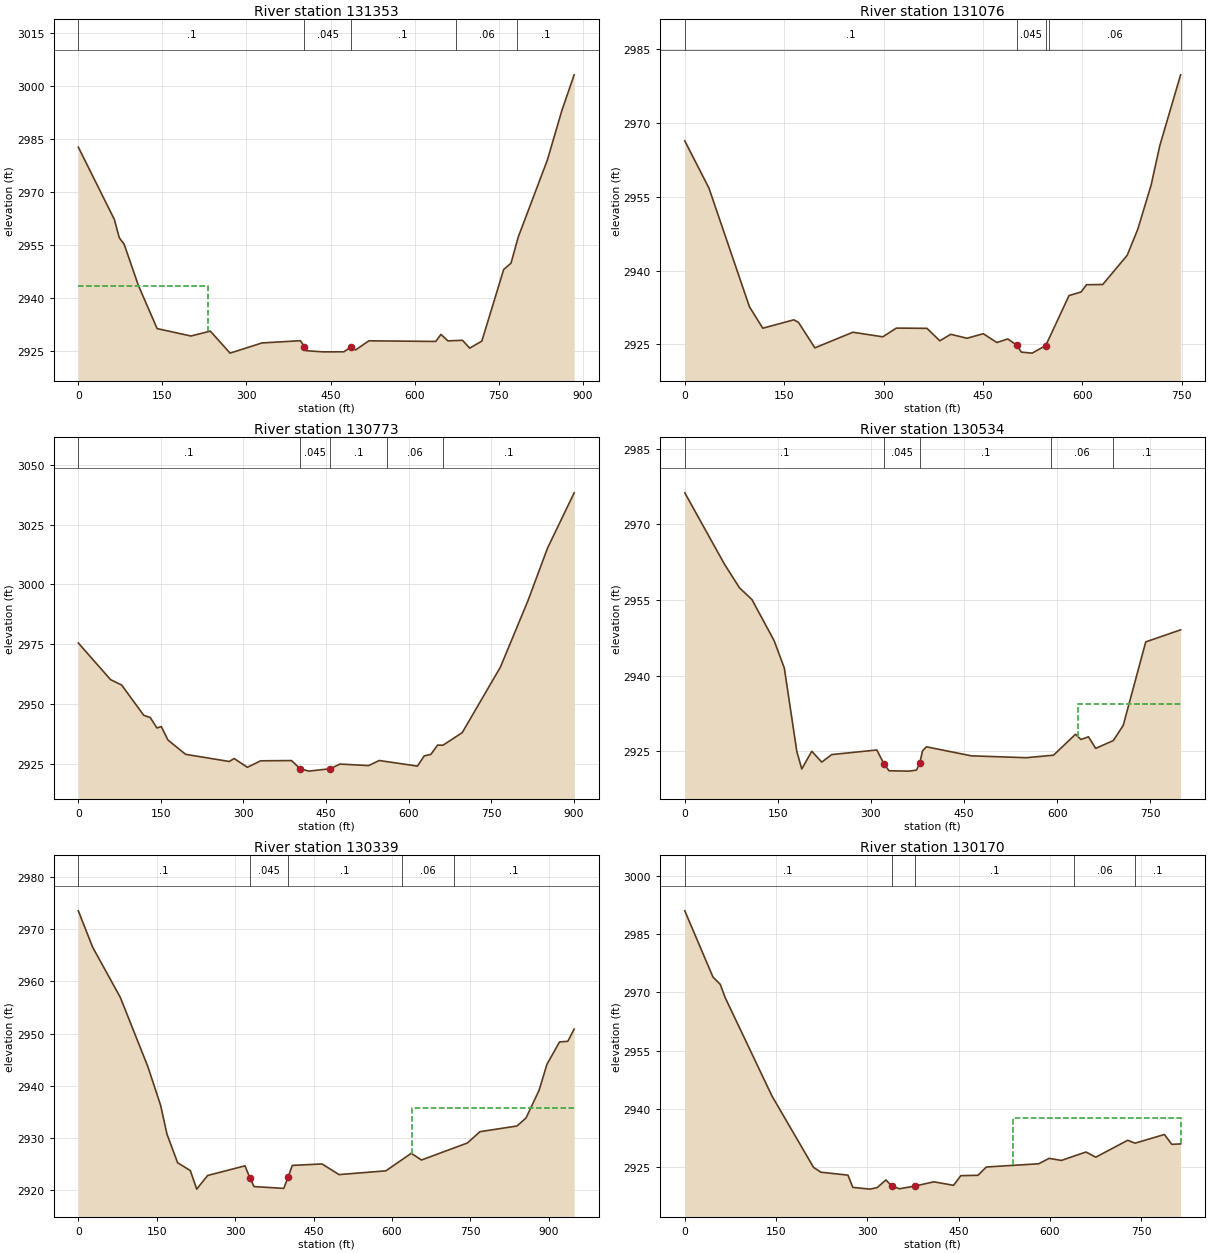
Type RM Length L Ch R = 1 ,131353  ,277.7,277.7,277.7
XS GIS Cut Line= 3
2353865.64922029654016.7386608762354333.11573454653804.788095901
2354676.40090966653663.215813759
#Sta/Elev= 30
       0 2982.71    64.3  2962.2      73 2957.07    81.8 2955.17   107.3 2943.46
   140.6 2931.29     201 2929.19   235.5 2930.58   270.7 2924.34   327.8 2927.23
   396.1 2927.86   403.5 2926.17   406.8 2925.02   436.7  2924.7   473.6 2924.71
   485.9 2926.01   494.7 2925.24   518.4 2927.83   637.7 2927.65     647 2929.65
   659.4 2927.81   685.3 2927.98   698.3 2925.75   719.9 2927.75   758.9 2948.05
   771.9 2949.81   784.8 2957.21   836.8 2979.05   862.7  2993.1   884.6  3003.2
#Mann= 5 ,-1,0
       0      .1       0   403.5    .045       0   485.9      .1       0
  673.27     .06       0  783.27      .1       0
#XS Ineff= 2 , 0
          231.77 2943.37
Permanent Ineff=
       F       F
Bank Sta=403.5,485.9
XS Rating Curve= 0 ,0
Exp/Cntr=0.3,0.1

Type RM Length L Ch R = 1 ,131076  ,302.7,302.7,302.7
XS GIS Cut Line= 2
 2353944.5980541 654134.238638782354674.81267502653970.569844436
#Sta/Elev= 30
       0 2966.31    36.5 2956.72    97.6 2932.64   117.7  2928.3   164.6    2930
   171.7 2929.46   196.3 2924.31   253.7 2927.48   298.8 2926.55   319.3 2928.32
   365.5 2928.27   384.9 2925.74   401.3 2927.06     426 2926.26   450.5 2927.18
     471 2925.39   487.4 2926.12   500.92924.875   507.9 2923.45   524.3 2923.24
   544.8 2924.78   579.9 2934.92   598.1 2935.65   606.3 2937.12   630.8 2937.17
   667.7  2943.1   683.7 2948.39   703.8 2957.34   716.9 2965.34   748.3 2979.72
#Mann= 5 ,-1,0
       0      .1       0   500.9    .045       0   544.8      .1       0
     550     .06       0  748.33      .1       0
Bank Sta=500.9,544.8
XS Rating Curve= 0 ,0
Exp/Cntr(USF)=0,0
Exp/Cntr=0.3,0.1

Type RM Length L Ch R = 1 ,130773  ,239.4,239.4,239.4
XS GIS Cut Line= 3
2353921.64795483654274.5466893672354513.05750313654313.185169562
 2354815.6327401654254.072271022
#Sta/Elev= 30
       0 2975.48    58.7 2960.11    78.7  2957.9   118.8 2945.24   130.8 2944.25
   142.8 2939.93   150.8 2940.49   162.9 2934.87   194.9 2928.88   274.4 2925.88
   283.1 2927.13   307.2 2923.46   331.2 2926.16   387.4 2926.27     403 2922.88
   418.8 2921.85   457.8 2922.85   475.5 2924.81   527.6 2924.17   546.7  2926.3
   616.2 2923.95   628.5  2928.2   640.7 2928.87   652.9 2932.76   662.5 2932.68
   697.6 2937.95     767 2965.39     817 2993.14   852.6 3015.18     901 3038.32
#Mann= 5 ,-1,0
       0      .1       0     403    .045       0   457.8      .1       0
     560     .06       0  662.67      .1       0
Bank Sta=403,457.8
XS Rating Curve= 0 ,0
Exp/Cntr=0.3,0.1

Type RM Length L Ch R = 1 ,130534  ,194.6,194.6,194.6
XS GIS Cut Line= 2
2353992.43970168654504.3819121432354788.12184034654577.403374235
#Sta/Elev= 30
       0 2976.24      64 2962.09    88.1 2957.42   108.2 2955.09     144 2946.93
   160.4 2941.51   180.5    2925   188.5 2921.52   204.6 2925.02   220.7 2922.88
   236.7 2924.37   309.5 2925.28   320.6  2922.6   329.1 2921.16   361.5 2921.09
   373.3 2921.29   378.5 2922.63   383.1 2925.11   389.4 2925.91   461.7 2924.12
     550 2923.75   594.2 2924.25   629.6 2928.39   638.4 2927.36   650.5 2927.89
   662.2  2925.6   690.6 2927.15   706.5 2930.15   742.8  2946.7     799 2949.09
#Mann= 5 ,-1,0
       0      .1       0   320.6    .045       0   378.5      .1       0
     590     .06       0     690      .1       0
#XS Ineff= 2 , 0
                          633.56         2934.47
Permanent Ineff=
       F       F
Bank Sta=320.6,378.5
XS Rating Curve= 0 ,0
Exp/Cntr(USF)=0,0
Exp/Cntr=0.3,0.1

Type RM Length L Ch R = 1 ,130339  ,169.2,169.2,169.2
XS GIS Cut Line= 3
2353973.16514505654666.2944473962354552.43881629      654769.589
2354912.18682974654789.984514336
#Sta/Elev= 30
       0 2973.52    27.4 2966.56    80.3 2956.96   133.1 2943.69   157.5 2936.28
   169.6 2930.79     190 2925.31   214.3 2923.81   226.5 2920.26   247.4 2922.87
   318.9 2924.72   328.1 2922.45   336.2 2920.75   393.1  2920.4   401.2 2922.52
   409.4  2924.8   466.3 2925.08   498.8 2923.04   588.4 2923.76   637.1 2927.12
   656.5 2925.83   744.4 2929.09   768.4 2931.25   839.2 2932.34   856.6 2933.87
   881.6 2939.18   896.6 2944.14   920.7 2948.43   936.6 2948.55   948.7 2950.89
#Mann= 5 ,-1,0
       0      .1       0   328.1    .045       0   401.2      .1       0
  618.41     .06       0  718.41      .1       0
#XS Ineff= 2 , 0
                          639.26         2935.71
Permanent Ineff=
       F       F
Bank Sta=328.1,401.2
XS Rating Curve= 0 ,0
Exp/Cntr=0.3,0.1

Type RM Length L Ch R = 1 ,130170  ,352.3,352.3,352.3
XS GIS Cut Line= 2
2353942.27665336654850.3490413242354750.54869928654951.068299381
#Sta/Elev= 30
       0 2990.95    46.3 2973.92    58.3 2972.03    66.4 2968.61     143 2943.39
   211.5 2924.97   223.6 2923.73     268 2922.98     276 2919.83   304.2 2919.38
   316.1 2919.78   330.4 2921.74   339.7 2920.21   352.6 2919.47   377.82920.159
     409 2921.26   441.5 2920.36   453.4 2922.84   481.6 2922.94   495.3 2925.07
   581.3  2925.9   598.5 2927.29   618.6 2926.76     659 2928.93   675.1 2927.59
   727.5 2931.94   739.6  2931.2   787.9 2933.43     800  2930.9   814.5 2931.01
#Mann= 5 ,-1,0
       0      .1       0   339.7    .045       0   377.8      .1       0
     640     .06       0     740      .1       0
#XS Ineff= 2 , 0
                          538.59         2937.65
Permanent Ineff=
       F       F
Bank Sta=339.7,377.8
XS Rating Curve= 0 ,0
Exp/Cntr(USF)=0,0
Exp/Cntr=0.3,0.1

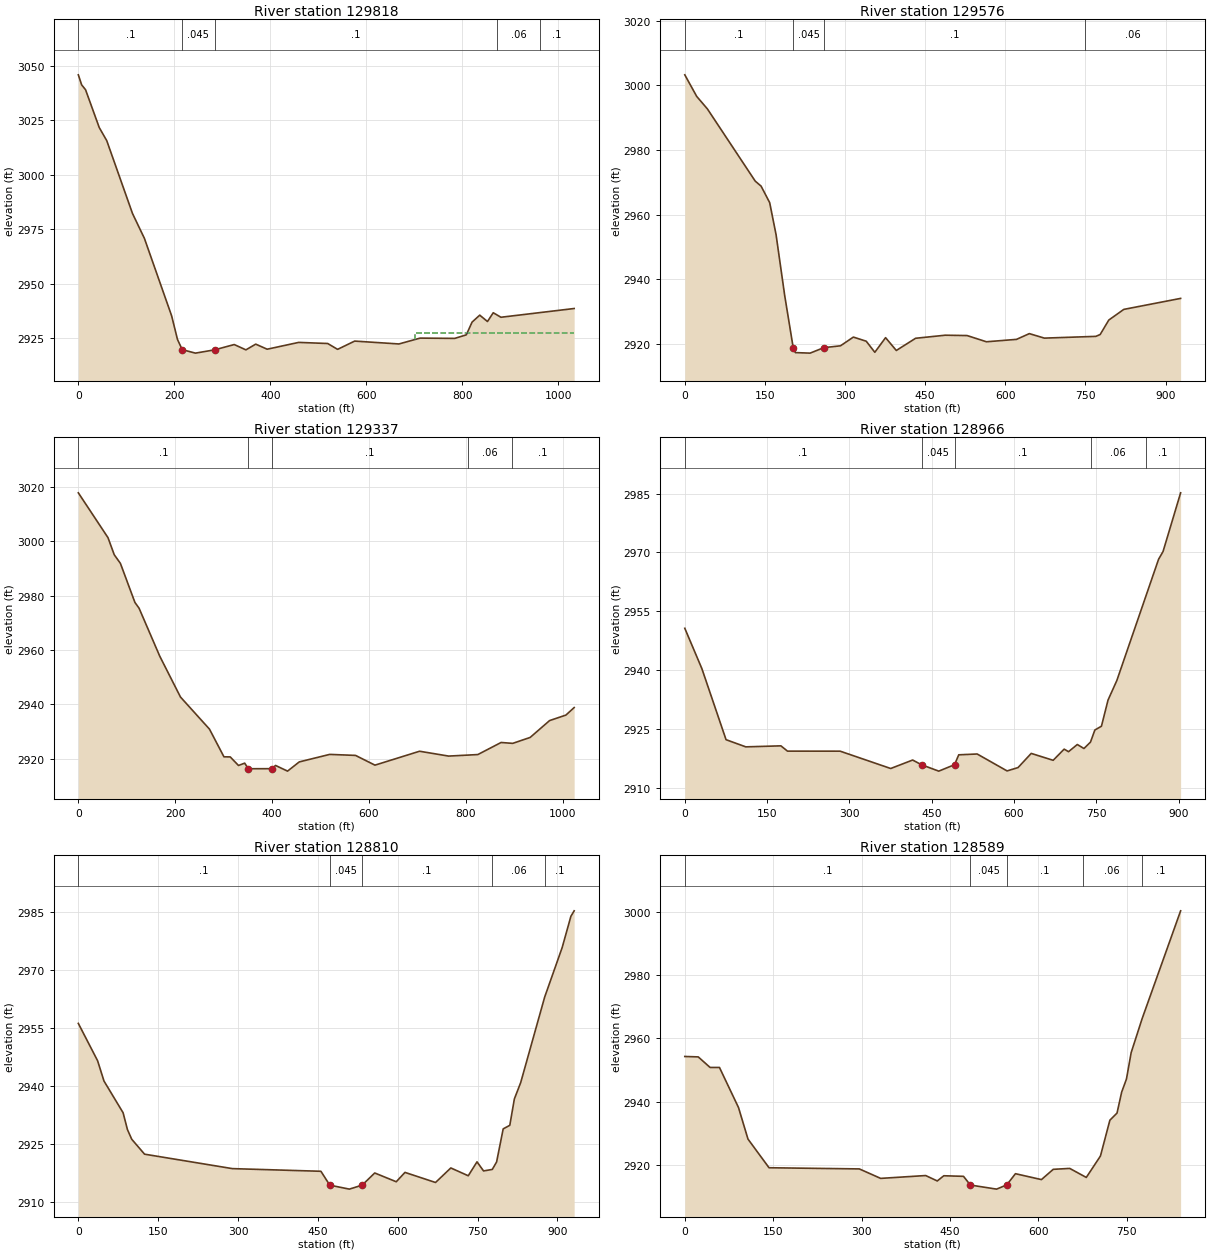
Type RM Length L Ch R = 1 ,129818  ,241.5,241.5,241.5
XS GIS Cut Line= 3
2353821.39681289655102.5242766062354284.94238627655192.804814514
2354844.27627498655233.497333874
#Sta/Elev= 30
       0  3045.9     6.9 3041.31    15.1 3039.03    43.6 3021.66    59.2 3015.66
   112.9 2982.17   137.7 2970.75   194.4 2935.17   206.6 2924.31   216.4 2919.63
     244 2918.03     284 2919.54   324.8 2921.97   349.2 2919.53   369.6 2922.16
   393.5 2919.83   459.2 2922.96   519.6 2922.45   540.2 2919.76   575.8 2923.56
     668 2922.24   712.1 2924.93   784.3  2924.8   808.4 2926.43   820.4 2932.28
   836.4 2935.48   852.5 2932.55   864.5 2936.58   880.6 2934.51  1033.1 2938.53
#Mann= 5 ,-1,0
       0      .1       0   216.4    .045       0     284      .1       0
  872.26     .06       0  962.26      .1       0
#XS Ineff= 2 , 0
                          700.48         2927.32
Permanent Ineff=
       F       F
Bank Sta=216.4,284
XS Rating Curve= 0 ,0
Exp/Cntr=0.3,0.1

Type RM Length L Ch R = 1 ,129576  ,239.5,239.5,239.5
XS GIS Cut Line= 2
2353834.00345095655406.8229420942354758.10264363655318.693591293
#Sta/Elev= 30
       0 3003.22    22.3 2996.55    42.4 2992.66   131.9 2970.35   142.8 2968.82
   158.9 2963.72   170.9 2953.78     187 2935.03   203.1 2918.73   207.1 2917.34
   234.6 2917.18   260.3 2918.87   291.5 2919.44   315.6 2922.14   339.7 2920.86
   355.8 2917.44   375.9 2921.96     396    2918   432.1 2921.77   487.7 2922.72
   528.6 2922.61   564.7 2920.69     621 2921.43   645.1 2923.21   673.2 2921.82
   769.6 2922.36   777.7 2922.94   793.8  2927.4   821.9  2930.7   928.3  2934.1
#Mann= 4 ,-1,0
       0      .1       0   203.1    .045       0   260.3      .1       0
     750     .06       0
Bank Sta=203.1,260.3
XS Rating Curve= 0 ,0
Exp/Cntr(USF)=0,0
Exp/Cntr=0.3,0.1

Type RM Length L Ch R = 1 ,129337  ,370.6,370.6,370.6
XS GIS Cut Line= 3
2353806.84655483655736.7992967772354195.22561694655590.075407304
2354802.73789636655553.661916507
#Sta/Elev= 30
       0 3017.83    61.3 3001.33    74.1 2995.08    86.9 2991.88   116.9 2977.51
   125.4 2975.41   168.2 2957.74   210.9 2942.75   270.8 2930.94   300.7 2920.76
   313.6 2920.73   330.7 2917.58   343.5 2918.43350.99972916.374398.8997  2916.4
   407.3 2917.58     432  2915.5   456.2 2918.89     519 2921.65   572.4 2921.28
   612.5  2917.7   704.6 2922.81   764.7 2921.03   824.9 2921.59   872.9 2926.03
     897 2925.71     933 2927.89   973.1 2934.09  1006.7  2936.1  1023.8 2938.87
#Mann= 5 ,-1,0
       0      .1       0350.9997    .045       0398.8997      .1       0
  805.17     .06       0  895.17      .1       0
Bank Sta=350.9997,398.8997
XS Rating Curve= 0 ,0
Exp/Cntr=0.3,0.1

Type RM Length L Ch R = 1 ,128966  ,155.7,155.7,155.7
XS GIS Cut Line= 2
2353941.05025285655858.0137074182354844.36359087655832.084777447
#Sta/Elev= 30
       0 2950.64    31.1 2940.36    75.2 2922.22   111.2 2920.39   175.2 2920.65
   187.2  2919.3   283.2 2919.29   375.3 2914.87   415.3 2917.03   431.7 2915.81
   462.9  2914.2  491.65 2915.84   499.3 2918.36   532.9 2918.57   587.4 2914.25
   607.4 2915.11   631.4 2918.72   671.4 2916.96   691.4 2919.81   699.4 2919.16
   715.4 2920.99   727.5 2919.97   739.4  2921.6   747.4 2924.69   759.4 2925.66
   771.4 2932.33   787.4  2937.3   863.5 2968.24   871.7 2970.24   903.7  2985.2
#Mann= 5 ,-1,0
       0      .1       0   431.7    .045       0  491.65      .1       0
     740     .06       0     840      .1       0
Bank Sta=431.7,491.65
XS Rating Curve= 0 ,0
Exp/Cntr(USF)=0,0
Exp/Cntr=0.3,0.1

Type RM Length L Ch R = 1 ,128810  ,221.5,221.5,221.5
XS GIS Cut Line= 4
2353904.02654019656030.0327930852354337.75611013656003.680711267
2354499.70182789655994.6277946872354826.11918539 655920.91281461
#Sta/Elev= 30
       0 2956.28    36.2 2946.61    48.2 2941.36    84.1 2933.14    92.3 2928.77
   100.3 2926.29   124.4 2922.42   289.4 2918.68   455.7 2917.99472.35672914.401
   509.1 2913.37   533.1  2914.4   556.8 2917.55   597.2 2915.28   613.6  2917.7
     671 2915.09   699.7 2918.85   732.5 2916.83   748.9 2920.44   761.2 2918.08
   777.6 2918.47   785.7  2920.4   798.1 2928.97   810.5 2929.89   819.1 2936.73
     831 2940.97     876 2963.09   908.9 2975.93   925.3 2984.02   931.4 2985.43
#Mann= 5 ,-1,0
       0      .1       0472.3567    .045       0   533.1      .1       0
  776.73     .06       0  876.73      .1       0
Bank Sta=472.3567,533.1
XS Rating Curve= 0 ,0
Exp/Cntr=0.3,0.1

Type RM Length L Ch R = 1 ,128589  ,264.4,264.4,264.4
XS GIS Cut Line= 3
2354001.51857507656234.8293462192354434.61138472656192.023661544
 2354840.0063984656171.879809933
#Sta/Elev= 30
       0 2954.25    22.8 2954.12    42.9 2950.79    58.8 2950.79    91.1 2938.14
   107.2 2928.17   142.9 2919.12   296.1 2918.75   332.3 2915.76   408.6 2916.66
   428.3 2914.95   439.4 2916.59   472.8 2916.41   484.4 2913.66   528.9 2912.37
   546.2 2913.71   560.9 2917.24     605 2915.38     625 2918.62     653 2918.91
   681.1 2916.06   705.1 2922.83   721.1 2934.13   733.2 2936.38   741.1 2943.01
   749.2 2947.12   757.2 2955.47   775.2 2965.85   775.2 2965.88   841.1 3000.24
#Mann= 5 ,-1,0
       0      .1       0   484.4    .045       0   546.2      .1       0
   675.2     .06       0   775.2      .1       0
Bank Sta=484.4,546.2
XS Rating Curve= 0 ,0
Exp/Cntr(USF)=0,0
Exp/Cntr=0.3,0.1

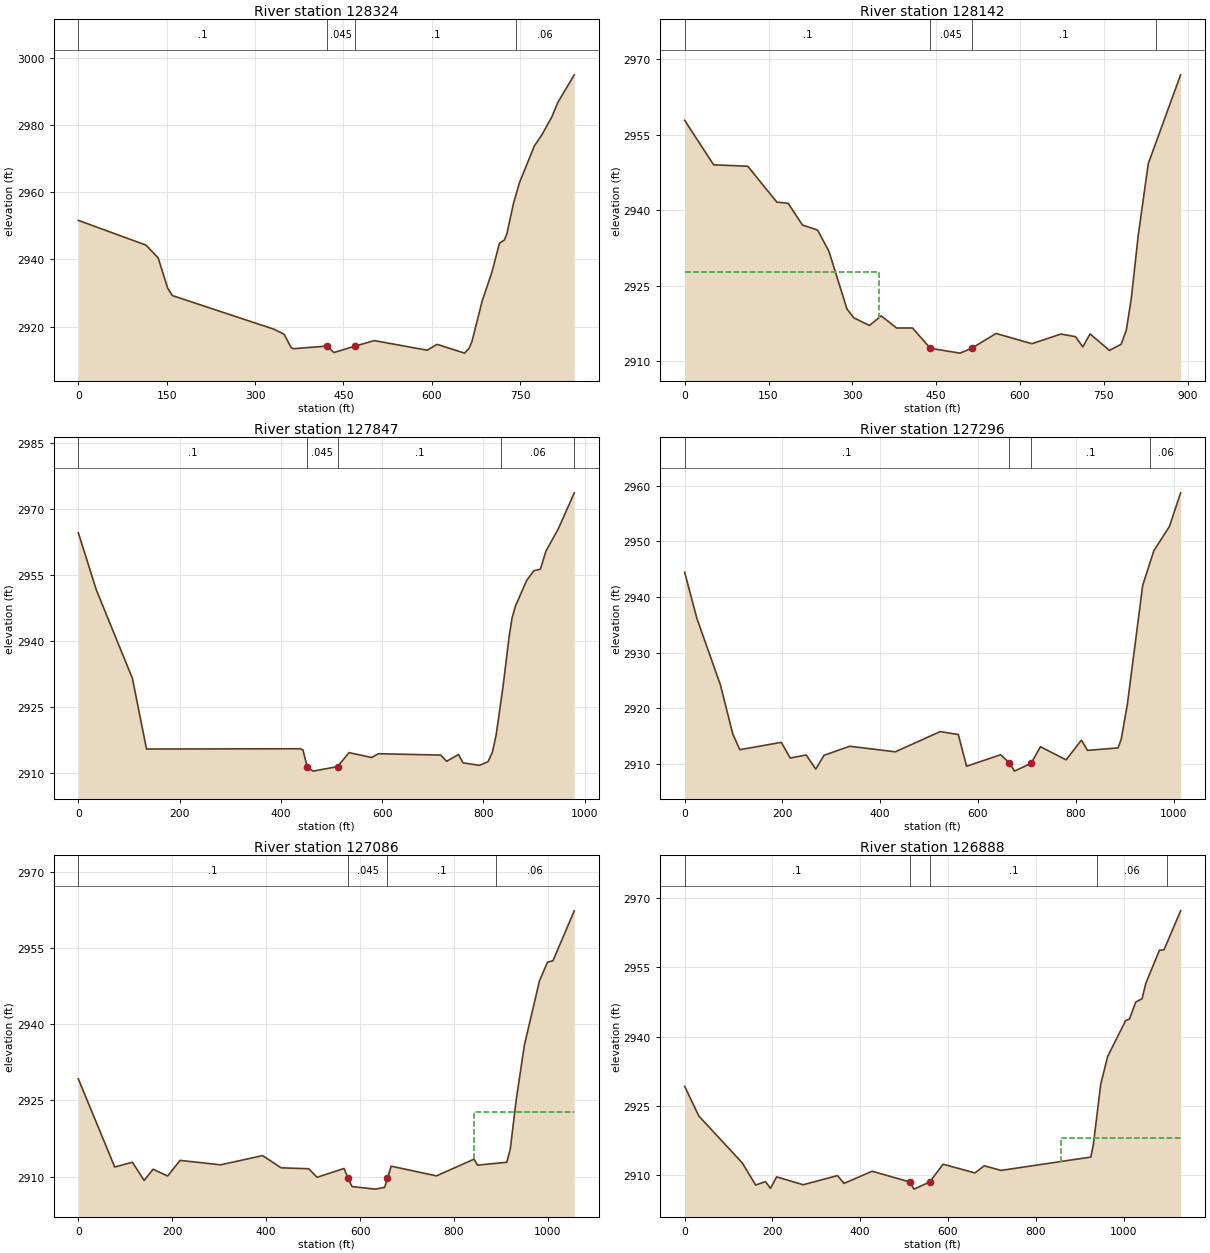
Type RM Length L Ch R = 1 ,128324  ,182.9,182.9,182.9
XS GIS Cut Line= 3
     2354045.699      656386.4252354614.49907257656457.912728495
 2354868.0519561656369.509986553
#Sta/Elev= 30
       0 2951.59     115 2944.21   135.5 2940.41   151.8 2931.38   159.7 2929.22
   331.7 2919.24   349.2 2917.73   361.3 2913.75   365.3 2913.43   421.8 2914.21
   433.9 2912.29     470 2914.21   502.4 2915.84     592 2912.98   608.9 2914.72
   655.5 2912.11   663.1  2913.5   668.2 2915.61   685.2 2927.44   702.1 2936.24
   714.8 2944.79   723.3 2945.78   727.6 2947.72   738.5 2956.55   748.7 2962.73
   774.1 2973.74   786.9 2977.05   803.8 2982.38   813.9 2986.64   841.8 2994.85
#Mann= 4 ,-1,0
       0      .1       0   421.8    .045       0     470      .1       0
  743.27     .06       0
Bank Sta=421.8,470
XS Rating Curve= 0 ,0
Exp/Cntr=0.3,0.1

Type RM Length L Ch R = 1 ,128142  ,294.6,294.6,294.6
XS GIS Cut Line= 3
 2353960.9041982656685.2912003642354527.45002477 656601.44241803
2354817.52148798 656479.06851949
#Sta/Elev= 30
       0 2957.89    51.8 2949.05   112.9 2948.77     165 2941.64   185.3 2941.39
   210.8 2937.08   237.8 2936.09   258.1 2931.88   290.4  2920.4   302.5 2918.65
   330.6 2917.12   351.7 2919.02   379.4 2916.61   407.7 2916.62   439.7 2912.58
   492.6 2911.62   513.7 2912.59   557.3 2915.53   621.3 2913.49   673.4 2915.42
   699.4 2914.89   712.4 2912.86   725.5 2915.44   760.2 2912.16   781.1 2913.38
   790.3 2916.19   799.3 2922.51   811.6 2934.97   829.6 2949.28   887.5 2966.94
#Mann= 4 ,-1,0
       0      .1       0   439.7    .045       0   513.7      .1       0
  842.72     .06       0
#XS Ineff= 2 , 0
          347.09 2927.71
Permanent Ineff=
       F       F
Bank Sta=439.7,513.7
XS Rating Curve= 0 ,0
Exp/Cntr(USF)=0,0
Exp/Cntr=0.3,0.1

Type RM Length L Ch R = 1 ,127847  ,551.1,551.1,551.1
XS GIS Cut Line= 3
2354236.47251256657244.877642476     2354569.239656825.291313625
2354871.93511291656500.259558235
#Sta/Elev= 30
       0 2964.56    35.4 2951.59   106.8 2931.44   134.7 2915.35   438.7 2915.41
   443.8 2915.11   452.3 2911.22   463.7 2910.32   512.1 2911.35   534.8 2914.53
   579.4 2913.42   592.7 2914.28     716 2913.97   727.6 2912.56   751.1 2914.11
   759.8 2912.21   792.4 2911.64   809.4 2912.47   817.9 2914.59   825.4 2918.56
   839.2 2929.77   850.9 2940.83   856.8 2945.18   863.6  2947.9   885.5 2953.68
   899.9 2955.91   912.8 2956.28   923.8 2960.41   948.1 2965.43   979.7 2973.64
#Mann= 5 ,-1,0
       0      .1       0   452.3    .045       0   512.1      .1       0
  835.52     .06       0  979.68      .1       0
Bank Sta=452.3,512.1
XS Rating Curve= 0 ,0
Exp/Cntr=0.3,0.1

Type RM Length L Ch R = 1 ,127296  ,210,210,210
XS GIS Cut Line= 3
2354466.58739964657364.9513001782354885.63707079656945.904900533
 2355218.2479561656686.339242832
#Sta/Elev= 30
       0 2944.47    24.9 2936.21    73.2 2924.21    98.4 2915.43   112.8  2912.6
   197.7 2913.92   215.9  2911.1   248.6 2911.65   268.1 2909.12   285.1 2911.59
   337.5 2913.22   430.9 2912.22   522.7 2915.85   559.7 2915.33   576.7 2909.63
   646.2 2911.69   663.82910.294   674.7 2908.75   708.9 2910.17   727.8 2913.14
   780.2 2910.77   811.5 2914.31   824.2 2912.48   886.4 2912.92   892.9 2914.44
   905.6 2920.78   936.9  2942.1   959.7 2948.34   991.6  2952.7  1014.5 2958.74
#Mann= 4 ,-1,0
       0      .1       0   663.8    .045       0   708.9      .1       0
  952.62     .06       0
Bank Sta=663.8,708.9
XS Rating Curve= 0 ,0
Exp/Cntr=0.3,0.1

Type RM Length L Ch R = 1 ,127086  ,198.4,198.4,198.4
XS GIS Cut Line= 2
2354575.04260159657387.3544473162355458.17423605656808.117994224
#Sta/Elev= 30
       0 2929.26    77.5 2911.88   115.1 2912.82   140.1 2909.24   159.2 2911.44
   190.2 2910.11   216.6 2913.19   302.8 2912.31   392.4 2914.13   431.9 2911.72
   490.6 2911.54   508.4 2909.86   565.8 2911.59   574.4 2909.66     583 2908.02
   632.8 2907.52   652.4 2907.88   658.2 2909.64   666.3 2912.05   762.5 2910.13
   842.7 2913.43     850 2912.25   912.4 2912.82   919.8 2915.41   932.6 2925.23
   949.9 2935.94     982 2948.59     999 2952.27  1010.7 2952.55  1056.1  2962.4
#Mann= 4 ,-1,0
       0      .1       0   574.4    .045       0   658.2      .1       0
     890     .06       0
#XS Ineff= 2 , 0
                          841.83         2922.69
Permanent Ineff=
       F       F
Bank Sta=574.4,658.2
XS Rating Curve= 0 ,0
Exp/Cntr(USF)=0,0
Exp/Cntr=0.3,0.1

Type RM Length L Ch R = 1 ,126888  ,357.7,357.7,357.7
XS GIS Cut Line= 4
2354701.85500025657515.7977675482355097.56288324657230.179496805
2355188.98041669657229.373887245 2355611.9943387656876.966430652
#Sta/Elev= 30
       0 2929.24    32.2 2922.83   131.1 2912.69   161.7 2907.89     184 2908.62
   195.5 2907.17   209.5 2909.65     270 2907.95   348.2 2909.93     363 2908.24
   427.1 2910.87  512.67 2908.56   522.6    2907   558.3 2908.55   588.8 2912.39
   661.4 2910.51   682.5 2912.05     721 2911.05   925.5 2913.94   931.2 2916.68
     948 2929.69   963.7 2935.69  1004.7 2943.47  1013.5 2943.81  1027.7 2947.48
  1042.2 2948.19  1050.5 2951.47  1081.7 2958.68  1092.2 2958.79    1130 2967.22
#Mann= 5 ,-1,0
       0      .1       0  512.67    .045       0   558.3      .1       0
  939.44     .06       0 1099.44      .1       0
#XS Ineff= 2 , 0
                          856.76         2918.03
Permanent Ineff=
       F       F
Bank Sta=512.67,558.3
XS Rating Curve= 0 ,0
Exp/Cntr=0.3,0.1

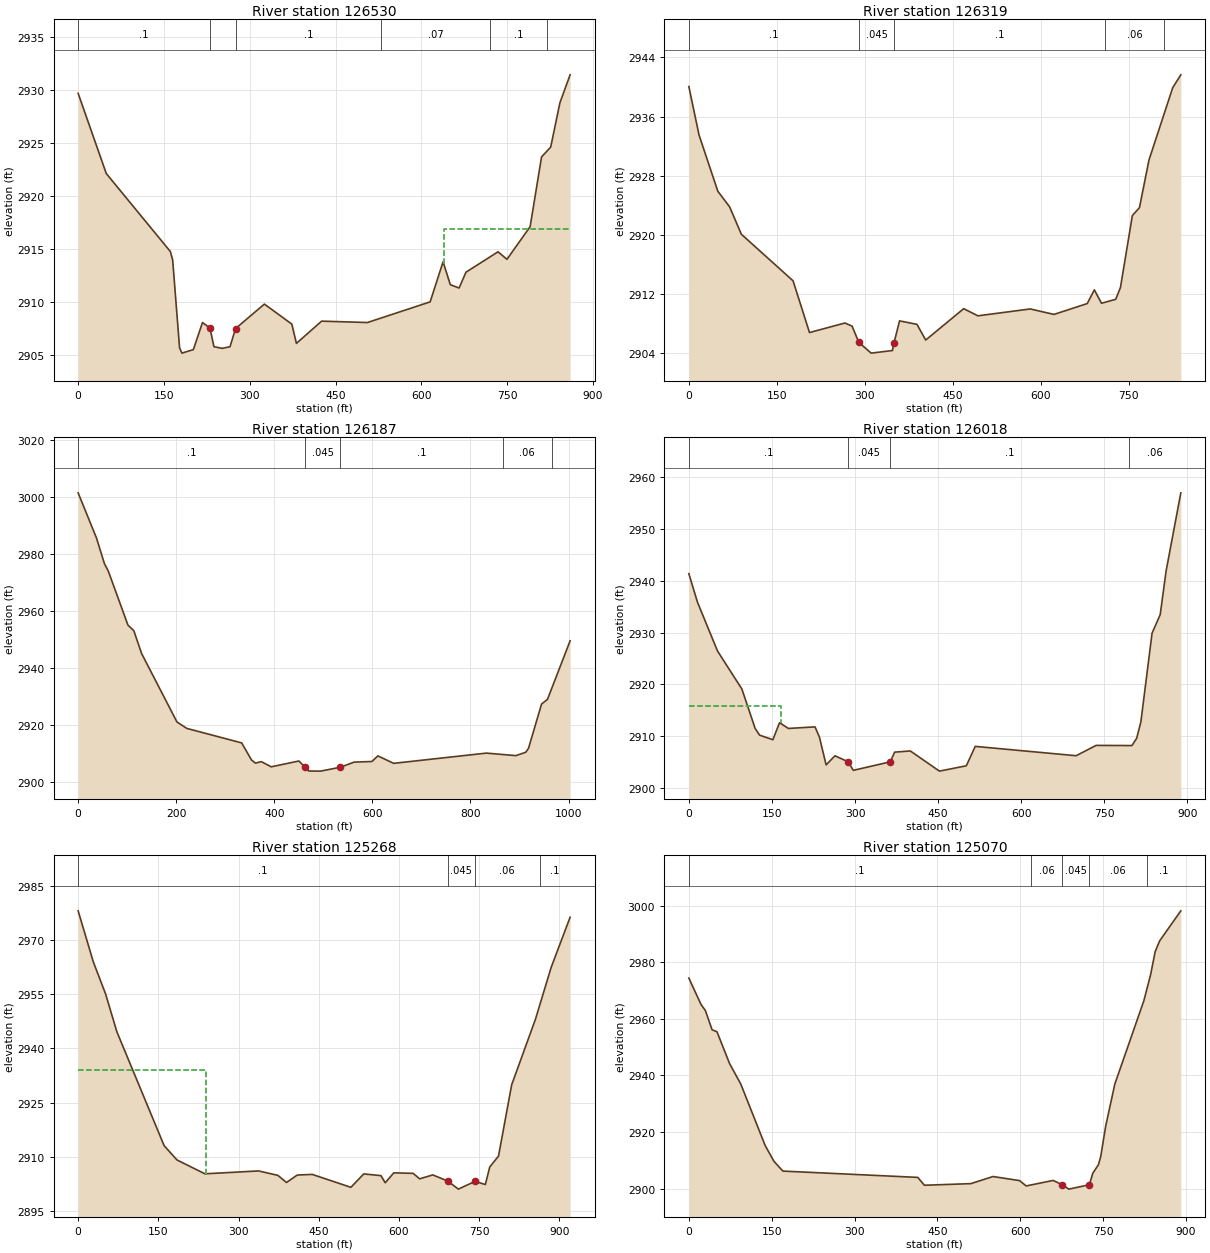
Type RM Length L Ch R = 1 ,126530  ,211.2,211.2,211.2
XS GIS Cut Line= 2
 2354743.0736657 657560.199951712355601.95713878657514.876285584
#Sta/Elev= 30
       0 2929.72    49.2 2922.15   161.3 2914.78   165.3 2913.97   177.3  2905.7
   181.4 2905.19   201.4 2905.52   217.4 2908.08   230.5 2907.56   237.4  2905.8
   251.7 2905.64   265.5 2905.79   275.22907.509   325.6 2909.82   373.6 2907.93
   381.6 2906.11   425.7 2908.21   505.8 2908.08   615.4 2910.03     638 2913.81
   650.7 2911.65     666 2911.34     678 2912.83   734.1 2914.76   749.7 2914.05
   790.2 2917.13   810.2 2923.72   826.2 2924.65   842.3 2928.84   860.1 2931.47
#Mann= 6 ,-1,0
       0      .1       0   230.5    .045       0   275.2      .1       0
     530     .07       0     720      .1       0     820     .06       0
#XS Ineff= 2 , 0
                          639.34         2916.95
Permanent Ineff=
       F       F
Bank Sta=230.5,275.2
XS Rating Curve= 0 ,0
Exp/Cntr(USF)=0,0
Exp/Cntr=0.3,0.1

Type RM Length L Ch R = 1 ,126319  ,131.9,131.9,131.9
XS GIS Cut Line= 2
2354757.33766034657736.8525245632355584.90528571657750.974092417
#Sta/Elev= 30
       0 2940.06    17.4  2933.5    49.4 2925.91    69.5  2923.8    89.5  2920.1
   177.7  2913.8   205.7 2906.81   266.1  2908.1   278.3 2907.68   289.8 2905.48
   310.8 2904.03   347.1 2904.38  349.83 2905.43   359.2 2908.39   388.9 2907.92
   403.8  2905.8   468.6 2910.04   492.7 2909.07     582    2910   622.5 2909.26
   679.2 2910.73   691.3 2912.58   703.5 2910.77   727.7  2911.3   735.8  2912.9
   756.1 2922.62   768.2 2923.69   784.4 2930.12   824.9  2939.9   838.7 2941.64
#Mann= 5 ,-1,0
       0      .1       0   289.8    .045       0  349.83      .1       0
     710     .06       0     810      .1       0
Bank Sta=289.8,349.83
XS Rating Curve= 0 ,0
Exp/Cntr=0.3,0.1

Type RM Length L Ch R = 1 ,126187  ,169.1,169.1,169.1
XS GIS Cut Line= 4
2354602.68360987657850.9965935732354963.68661056657850.996593573
2355226.79049242657881.5900682082355602.07044795657920.341802745
#Sta/Elev= 30
       0 3001.43    37.5 2985.55    53.5 2976.66    61.5    2974   101.5 2955.09
   113.5 2953.12   129.5 2945.08   201.5 2921.12   221.5 2918.87   333.5 2913.78
   353.5  2907.8   361.5  2906.7   373.6 2907.21   393.7  2905.4   450.1 2907.44
   462.2 2905.34   470.2 2903.93   494.4 2903.89   534.7 2905.25   562.8 2907.05
   599.1 2907.26   611.2 2909.23   643.4 2906.62   832.4  2910.2   892.7 2909.32
   912.8 2910.51   918.4  2911.9     945  2927.4     957 2929.03  1003.2 2949.55
#Mann= 5 ,-1,0
       0      .1       0   462.2    .045       0   534.7      .1       0
  865.88     .06       0  965.88      .1       0
Bank Sta=462.2,534.7
XS Rating Curve= 0 ,0
Exp/Cntr(USF)=0,0
Exp/Cntr=0.3,0.1

Type RM Length L Ch R = 1 ,126018  ,749.3,749.3,749.3
XS GIS Cut Line= 4
2354676.51586199657992.1344898892354945.73843878657983.976229986
 2355027.3210378658008.451009694 2355555.5683665658083.914913793
#Sta/Elev= 30
       0 2941.35    15.7 2935.82    51.7 2926.45    95.7 2919.12   119.7 2911.51
   127.7 2910.22   151.7 2909.33   163.7 2912.62   179.7 2911.51   227.8 2911.81
   235.8 2909.82   247.8 2904.48   263.8 2906.24   287.5 2905.09   296.9 2903.43
   363.5 2905.07   371.5 2906.94   399.8 2907.17   452.4 2903.28   500.9 2904.31
     517 2908.05   699.1 2906.25   735.2 2908.24   799.9 2908.21   808.5 2909.64
     816 2912.79   836.2 2929.88   850.9 2933.46   861.5 2941.84   888.1 2956.94
#Mann= 4 ,-1,0
       0      .1       0   287.5    .045       0   363.5      .1       0
  794.52     .06       0
#XS Ineff= 2 , 0
          165.63 2915.83
Permanent Ineff=
       F       F
Bank Sta=287.5,363.5
XS Rating Curve= 0 ,0
Exp/Cntr(USF)=0,0
Exp/Cntr=0.3,0.1

Type RM Length L Ch R = 1 ,125268  ,198.5,198.5,198.5
XS GIS Cut Line= 3
2354479.91827936 658375.539845452355110.52349131658429.379433912
 2355390.8486385658491.944132175
#Sta/Elev= 30
       0 2978.12    28.4 2963.97    51.2 2955.16    72.5  2944.6   160.8 2913.08
   184.9 2909.12   237.1 2905.28   337.5 2906.08   373.6 2904.85   389.7 2902.88
   409.7 2904.93   437.8 2905.12   510.1 2901.54   534.2 2905.25   566.3 2904.78
   574.3  2902.8   590.4 2905.55   626.5 2905.41   638.7 2903.89   663.3 2904.98
   691.1 2903.28   711.2 2901.04   742.2 2903.19   761.6 2902.32   769.8 2907.18
   786.2 2910.18   810.8 2929.93   855.3 2948.09   884.6 2962.43   920.1 2976.35
#Mann= 4 ,-1,0
       0      .1       0   691.1    .045       0   742.2     .06       0
   862.9      .1       0
#XS Ineff= 2 , 0
          238.26 2933.98
Permanent Ineff=
       F       F
Bank Sta=691.1,742.2
XS Rating Curve= 0 ,0
Exp/Cntr=0.3,0.1

Type RM Length L Ch R = 1 ,125070  ,283.8,283.8,283.8
XS GIS Cut Line= 3
2354450.17424319658589.5851202962355078.36025569658624.257724882
2355333.30587765658683.405109176
#Sta/Elev= 30
       0 2974.39      22 2965.09      30  2962.9    42.1 2956.12    50.9 2955.46
    73.6 2944.28    94.1 2936.96   138.2 2915.28   154.2 2909.68   170.3 2906.25
   414.6 2904.02   426.6 2901.25   510.8 2901.82   550.8 2904.33   598.9 2902.89
   610.9    2901   659.7 2902.95   676.2 2901.43   688.1 2899.88   725.4 2901.43
   731.4 2905.44   741.9 2908.57     746  2911.5   754.7 2921.96   771.4 2936.96
     824  2966.4   836.3 2975.67   844.5 2983.74   852.7 2987.55   890.9 2998.12
#Mann= 5 ,-1,0
       0      .1       0     620     .06       0   676.2    .045       0
   725.4     .06       0  829.14      .1       0
Bank Sta=676.2,725.4
XS Rating Curve= 0 ,0
Exp/Cntr(USF)=0,0
Exp/Cntr=0.3,0.1

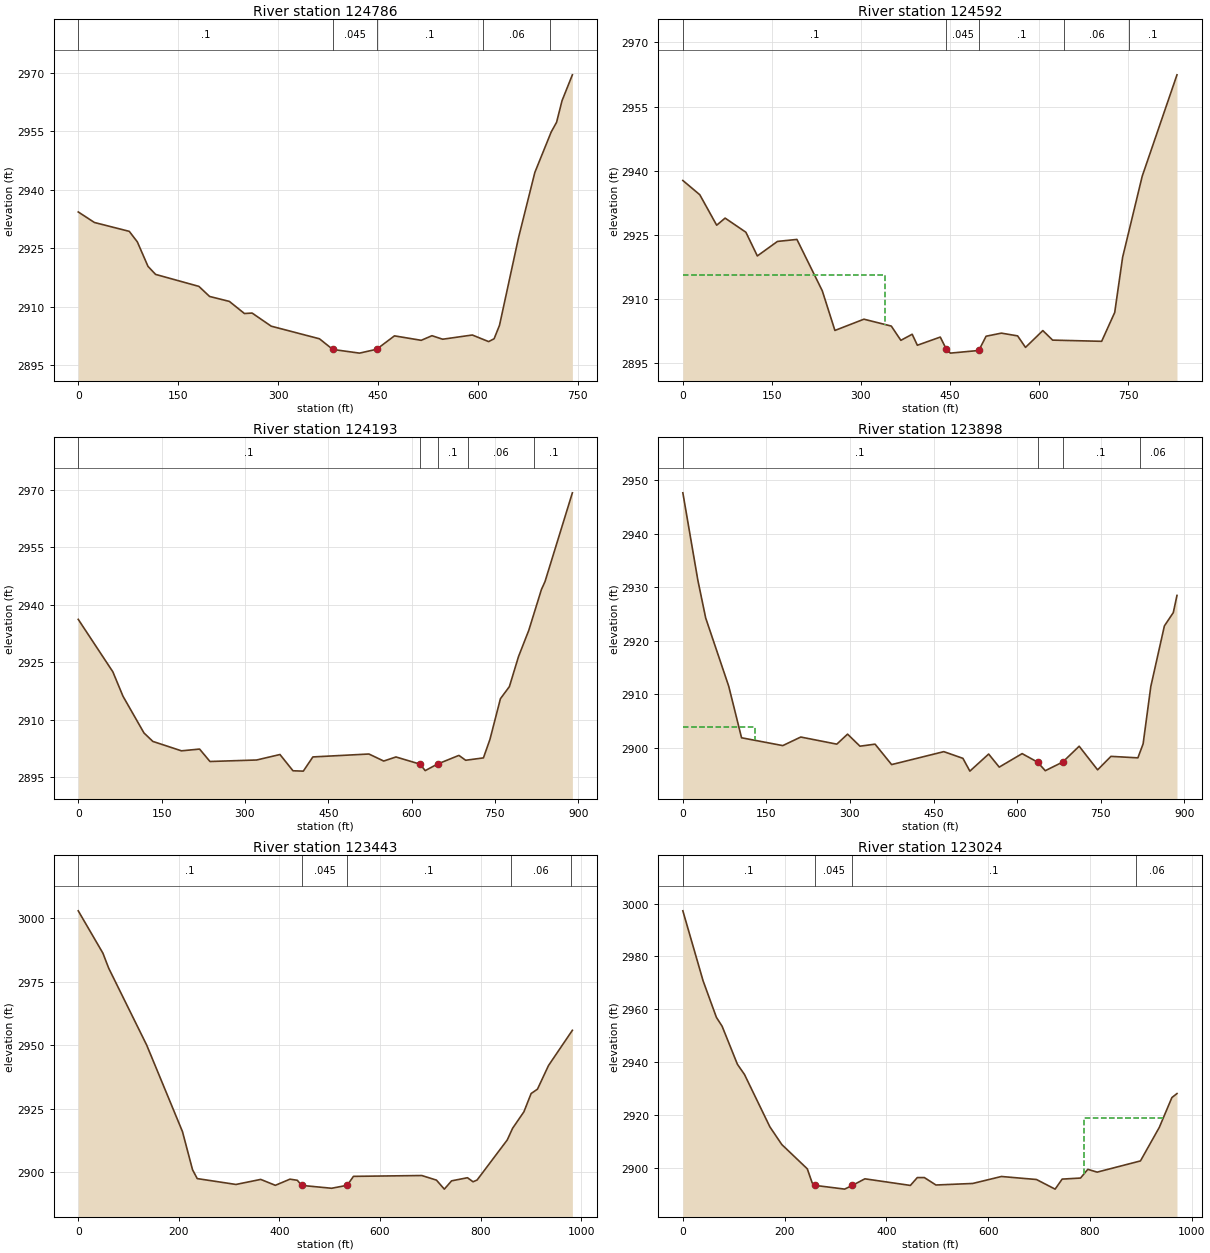
Type RM Length L Ch R = 1 ,124786  ,194.2,194.2,194.2
XS GIS Cut Line= 3
2354567.97108978658924.2998478092355132.85398499      658866.435
2355303.40311981658832.119386518
#Sta/Elev= 30
       0 2934.31    24.3 2931.61    76.6 2929.34    88.7 2926.65   104.7 2920.38
   116.1 2918.32   181.1 2915.25   197.2 2912.67   226.9  2911.4   249.5  2908.3
     261 2908.42   289.7 2905.06   362.1 2901.83   382.2  2899.1   422.3 2898.16
   447.92899.145   474.7 2902.58   514.9 2901.44     531 2902.62   547.1 2901.72
   591.6  2902.8   616.1 2901.11   624.3 2901.84   632.4 2905.28     661 2927.76
   685.5 2944.45     710 2954.78   718.1 2957.28   726.3 2962.81   741.8 2969.42
#Mann= 5 ,-1,0
       0      .1       0   382.2    .045       0   447.9      .1       0
  607.84     .06       0  707.84      .1       0
Bank Sta=382.2,447.9
XS Rating Curve= 0 ,0
Exp/Cntr=0.3,0.1

Type RM Length L Ch R = 1 ,124592  ,399,399,399
XS GIS Cut Line= 4
2354620.35093156659317.1900554962354938.52306777659100.996168076
2355085.37174601659043.8883487582355340.31736797658905.197930413
#Sta/Elev= 30
       0 2937.75    28.5 2934.43      57  2927.3    71.2 2928.96   106.2 2925.66
   125.5 2920.12   159.4 2923.51   192.2 2923.98   234.9 2911.98   256.2 2902.71
   305.1 2905.34   351.2 2903.73   367.3  2900.4   386.4 2901.82   395.1 2899.25
   433.7 2901.16   444.1 2898.28   450.7 2897.41   498.62898.033   510.9 2901.36
   536.7 2902.08     564 2901.44   577.3 2898.75   606.5 2902.68     623 2900.45
   705.6 2900.17   727.6 2906.91   740.9  2919.8   773.9 2938.74   832.5 2962.44
#Mann= 5 ,-1,0
       0      .1       0   444.1    .045       0   498.6      .1       0
  642.24     .06       0  752.24      .1       0
#XS Ineff= 2 , 0
          340.87 2915.73
Permanent Ineff=
       F       F
Bank Sta=444.1,498.6
XS Rating Curve= 0 ,0
Exp/Cntr(USF)=0,0
Exp/Cntr=0.3,0.1

Type RM Length L Ch R = 1 ,124193  ,294.6,294.6,294.6
XS GIS Cut Line= 3
2354741.91936042 659447.289988942354903.06811608659447.771266292
2355527.17490727659072.501522947
#Sta/Elev= 30
       0 2936.21    62.3 2922.54    80.6 2916.16   118.3 2906.61   134.3  2904.4
   185.8 2901.95   218.4 2902.41   237.1 2899.17   321.1 2899.56   363.1 2900.99
   386.5 2896.75   405.1 2896.66   422.3 2900.36   523.2 2901.12   549.8 2899.29
   571.9 2900.35   615.2 2898.48   624.5 2896.79  646.66 2898.51   685.2 2900.76
   697.3 2899.49   729.3 2900.11     741 2904.91   759.9 2915.53     776 2918.68
   792.5 2926.54   810.9 2933.34   833.7    2944   840.1 2946.04   889.4 2969.19
#Mann= 5 ,-1,0
       0      .1       0   615.2    .045       0  646.66      .1       0
  701.15     .06       0  821.15      .1       0
Bank Sta=615.2,646.66
XS Rating Curve= 0 ,0
Exp/Cntr=0.3,0.1

Type RM Length L Ch R = 1 ,123898  ,455.5,455.5,455.5
XS GIS Cut Line= 2
 2354852.8731806659797.9146823312355620.86306429659353.862373983
#Sta/Elev= 30
       0  2947.6    26.9 2931.29      41 2924.22    82.4 2911.45   105.4 2901.83
   179.4 2900.37   211.7 2901.97   276.4 2900.64   295.7 2902.51     318 2900.26
   345.1 2900.64   374.8 2896.82   468.5 2899.24   502.8 2897.99   515.3  2895.6
     549 2898.79     568 2896.35   609.1 2898.87   636.8 2897.28   650.7 2895.68
     682  2897.3   711.5 2900.25   744.6 2895.84   768.6 2898.36   816.9 2898.08
   826.3 2900.69   840.1  2911.4   864.5 2922.73   880.5 2925.22   887.1 2928.43
#Mann= 4 ,-1,0
       0      .1       0   636.8    .045       0     682      .1       0
     820     .06       0
#XS Ineff= 2 , 0
           128.7 2903.77
Permanent Ineff=
       F       F
Bank Sta=636.8,682
XS Rating Curve= 0 ,0
Exp/Cntr(USF)=0,0
Exp/Cntr=0.3,0.1

Type RM Length L Ch R = 1 ,123443  ,418.6,418.6,418.6
XS GIS Cut Line= 2
2355053.13765308660150.2358992842355862.96379552659593.854831073
#Sta/Elev= 30
       0 3002.97      49  2986.3    60.5 2980.39   136.1 2950.06   207.2    2916
   227.3 2900.93   236.6 2897.47   313.6 2895.16   362.8 2897.15   391.9 2894.82
     421 2897.25   435.6  2896.8  444.19 2894.79   503.9 2893.66   534.9 2894.84
   547.2 2898.35   683.1 2898.68   712.2 2896.87   727.9 2893.32   742.3 2896.58
   773.9 2897.81     785 2896.22     793  2896.9     853 2912.69   863.6 2917.28
   886.1 2923.78   900.5 2930.99   913.1 2932.71     935    2942   982.5  2955.9
#Mann= 5 ,-1,0
       0      .1       0  444.19    .045       0   534.9      .1       0
     860     .06       0     980      .1       0
Bank Sta=444.19,534.9
XS Rating Curve= 0 ,0
Exp/Cntr(USF)=0,0
Exp/Cntr=0.3,0.1

Type RM Length L Ch R = 1 ,123024  ,248.8,248.8,248.8
XS GIS Cut Line= 2
2355218.66912475660388.7696323562356064.90431761659912.114707394
#Sta/Elev= 30
       0 2997.25    39.9  2970.7      66 2956.93    77.2 2953.57   107.3 2939.17
   121.1 2935.35   171.1  2915.5   194.5 2908.82   244.6 2899.63   254.2 2894.31
     260 2893.36     318 2891.96   333.3 2893.37   357.8 2895.85   447.2 2893.35
   460.8 2896.32   474.6 2896.33   497.5 2893.51   569.7 2894.09   626.1 2896.73
     695 2895.59   731.7 2891.95   745.5 2895.74   781.6 2896.14     796 2899.44
   814.3 2898.38   899.4 2902.62   936.5 2915.33   961.2  2926.6   971.2  2928.1
#Mann= 4 ,-1,0
       0      .1       0     260    .045       0   333.3      .1       0
     890     .06       0
#XS Ineff= 1 ,-1
  788.59  947.99 2918.85
Permanent Ineff=
       F
Bank Sta=260,333.3
XS Rating Curve= 0 ,0
Exp/Cntr(USF)=0,0
Exp/Cntr=0.3,0.1