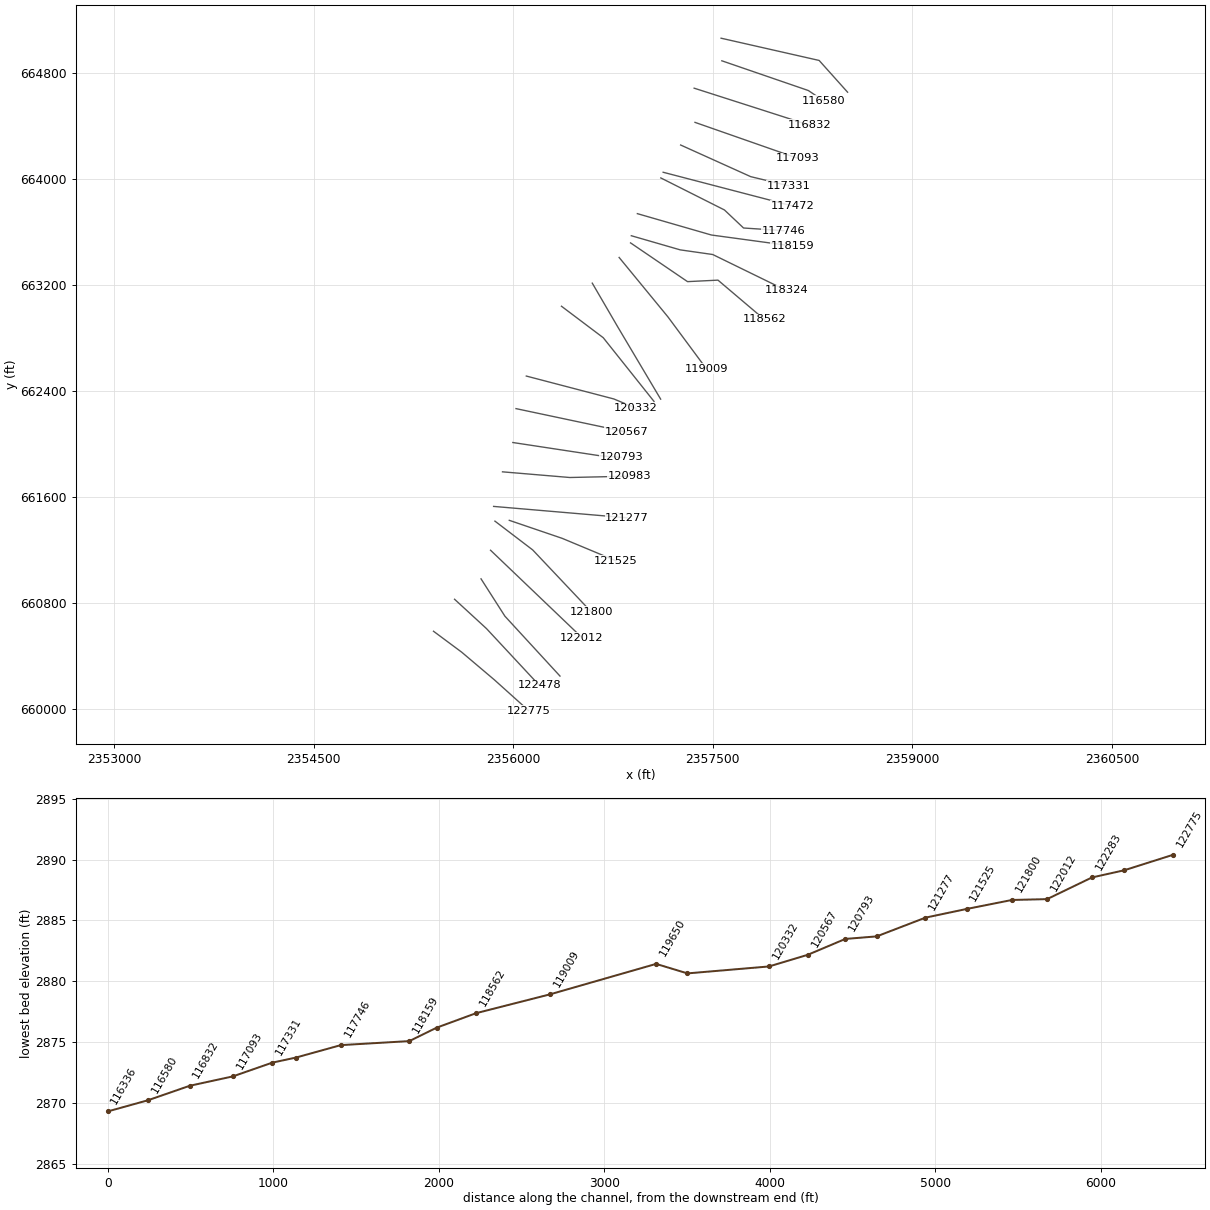
HEC-RAS study LAURELFK.prj: LAURELFK

--- LAURELFK.g01 (geometry) --- (continued)

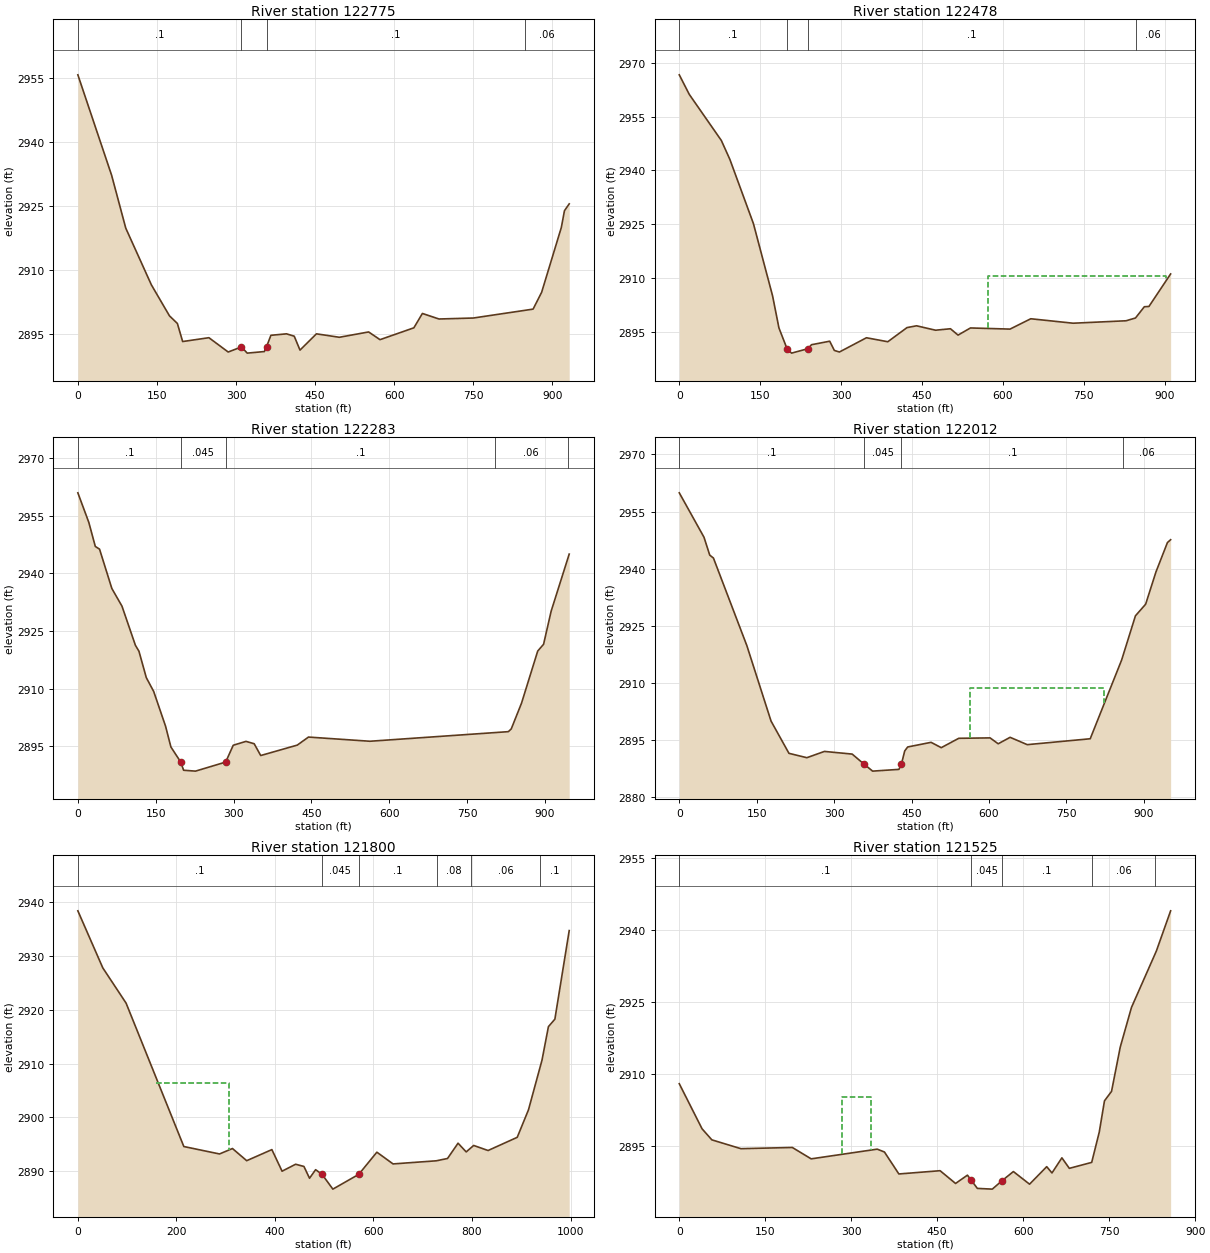
Type RM Length L Ch R = 1 ,122775  ,297.1,297.1,297.1
XS GIS Cut Line= 4
2355400.80942962660589.0816661162355612.39399976 660431.40176232
2355859.00753379660222.0323567322356115.01389021659991.171576092
#Sta/Elev= 30
       0 2955.72    64.1 2932.13    90.9 2919.73   139.5 2906.42   173.8 2899.15
   188.8 2897.36   198.8 2893.12   248.6 2894.02   285.2 2890.66   310.42891.857
   321.3  2890.4   353.8 2890.77     358 2891.92   366.2 2894.58   395.8 2894.93
   410.5 2894.37   421.4 2891.11   452.6 2894.93     496 2894.12   551.6 2895.37
   573.2 2893.56   637.4 2896.34   653.6 2899.71   685.1 2898.41   750.2 2898.64
   863.6 2900.73   879.8 2904.68   917.2 2919.91   923.1 2923.83   932.1 2925.43
#Mann= 4 ,-1,0
       0      .1       0   310.4    .045       0     358      .1       0
  847.38     .06       0
Bank Sta=310.4,358
XS Rating Curve= 0 ,0
Exp/Cntr=0.3,0.1

Type RM Length L Ch R = 1 ,122478  ,195,195,195
XS GIS Cut Line= 3
2355559.17581019660830.3575294822355798.53947903660609.645575097
2356196.44272074660180.656142631
#Sta/Elev= 30
       0 2966.62    18.5 2961.18      78 2948.33    93.9 2943.02   137.4  2925.2
   172.9 2905.08   184.7 2896.14   199.7 2890.35   208.1 2889.12   238.42890.352
     245 2891.46   278.8 2892.44   287.4 2889.87   296.8 2889.43   346.9  2893.4
   386.5 2892.29   422.1 2896.23   439.8 2896.73     475  2895.5   502.6 2895.91
   516.7 2894.14   539.7 2896.13     613 2895.81   651.5 2898.69     730 2897.45
   828.1 2898.13   845.6 2898.91     862 2902.04   870.5 2902.11   910.7 2911.17
#Mann= 4 ,-1,0
       0      .1       0   199.7    .045       0   238.4      .1       0
  845.59     .06       0
#XS Ineff= 1 ,-1
  572.15  902.68 2910.52
Permanent Ineff=
       F
Bank Sta=199.7,238.4
XS Rating Curve= 0 ,0
Exp/Cntr(USF)=0,0
Exp/Cntr=0.3,0.1

Type RM Length L Ch R = 1 ,122283  ,271.2,271.2,271.2
XS GIS Cut Line= 3
2355758.10940103660984.4233772092355937.42440271660702.885554897
2356351.64201738660250.909919036
#Sta/Elev= 30
       0 2961.01    21.2 2953.28    33.6 2947.05    41.8 2946.34    65.5  2936.1
      85  2931.5     111 2921.27   117.7 2919.77   131.9 2912.88   146.1 2909.29
     169 2900.24   179.3 2894.83   198.3 2890.88   203.8 2888.76   226.7 2888.53
   284.9 2890.89   299.4 2895.27     324 2896.28   339.8 2895.66   352.4 2892.59
   422.9 2895.31   444.4  2897.4   562.8 2896.31   829.6 2898.81   835.2 2899.52
     855 2906.23   886.2  2919.8   897.5 2921.57   912.1 2930.19   946.9 2945.06
#Mann= 5 ,-1,0
       0      .1       0   198.3    .045       0   284.9      .1       0
  803.79     .06       0  943.79      .1       0
Bank Sta=198.3,284.9
XS Rating Curve= 0 ,0
Exp/Cntr=0.3,0.1

Type RM Length L Ch R = 1 ,122012  ,212.1,212.1,212.1
XS GIS Cut Line= 2
2355829.62566979661200.2831995072356516.63048555660541.255955428
#Sta/Elev= 30
       0 2959.92    47.9 2948.24      59 2943.55    66.2 2942.77     131 2919.72
   177.8 2899.91   212.5 2891.43   247.2 2890.28   281.2 2891.93     335 2891.23
   358.3 2888.55   374.6 2886.75   425.5 2887.21   430.3 2888.53   436.8 2892.06
   442.5  2893.1   487.8 2894.32   507.6 2892.92   541.5 2895.38   602.2 2895.49
   617.9 2893.94     641 2895.64   674.2 2893.71   796.2 2895.26   857.1 2915.98
   883.8 2927.58   903.6 2930.64   923.6 2939.13   945.8 2946.84     952 2947.59
#Mann= 4 ,-1,0
       0      .1       0   358.3    .045       0   430.3      .1       0
     860     .06       0
#XS Ineff= 1 ,-1
  563.76  823.83  2908.7
Permanent Ineff=
       F
Bank Sta=358.3,430.3
XS Rating Curve= 0 ,0
Exp/Cntr(USF)=0,0
Exp/Cntr=0.3,0.1

Type RM Length L Ch R = 1 ,121800  ,274.5,274.5,274.5
XS GIS Cut Line= 3
2355862.47014218661419.9356932592356146.70501501661202.344418901
     2356585.131      660736.946
#Sta/Elev= 30
       0 2938.36    50.6 2927.77    97.9 2921.22   215.1 2894.59   287.5 2893.21
   313.8 2894.22   342.7 2891.96   393.8 2894.02   414.5 2890.01     442  2891.3
   458.9 2890.89   470.2  2888.7   482.6 2890.29   495.6 2889.43   517.6 2886.68
   570.1 2889.42   606.9 2893.54   639.8 2891.36   727.6 2891.94   750.3 2892.37
   771.7 2895.21   788.2 2893.59   803.4 2894.79   832.6 2893.85   891.8  2896.3
   914.6  2901.4   942.1 2910.64   955.1 2916.85   968.2 2918.24   997.3 2934.69
#Mann= 6 ,-1,0
       0      .1       0   495.6    .045       0   570.1      .1       0
  727.96     .08       0  797.96     .06       0  937.96      .1       0
#XS Ineff= 1 ,-1
  157.72  307.05 2906.47
Permanent Ineff=
       F
Bank Sta=495.6,570.1
XS Rating Curve= 0 ,0
Exp/Cntr=0.3,0.1

Type RM Length L Ch R = 1 ,121525  ,248,248,248
XS GIS Cut Line= 3
2355970.45076193 661425.871293692356368.29183125661289.900295313
2356771.16886348661121.195538067
#Sta/Elev= 30
       0 2907.91    39.7 2898.52    56.8 2896.21   107.5 2894.37   197.2 2894.62
   230.1 2892.25   345.3 2894.27   357.9 2893.68   383.1  2889.1     455 2889.78
     482 2887.12   502.7 2888.85   509.5 2887.77     520 2886.09   546.1 2885.94
   563.4 2887.73   582.9  2889.6   611.1 2886.97     641 2890.62   650.2 2889.31
   667.5 2892.46   680.5 2890.27   719.5 2891.51   732.7 2897.83   741.8 2904.34
   754.1 2906.31   769.3 2915.54   788.9 2923.81   832.3 2935.56   857.2 2943.94
#Mann= 5 ,-1,0
       0      .1       0   509.5    .045       0   563.4      .1       0
  720.44     .06       0  830.44      .1       0
#XS Ineff= 1 ,-1
  283.56  333.89 2905.11
Permanent Ineff=
       F
Bank Sta=509.5,563.4
XS Rating Curve= 0 ,0
Exp/Cntr(USF)=0,0
Exp/Cntr=0.3,0.1

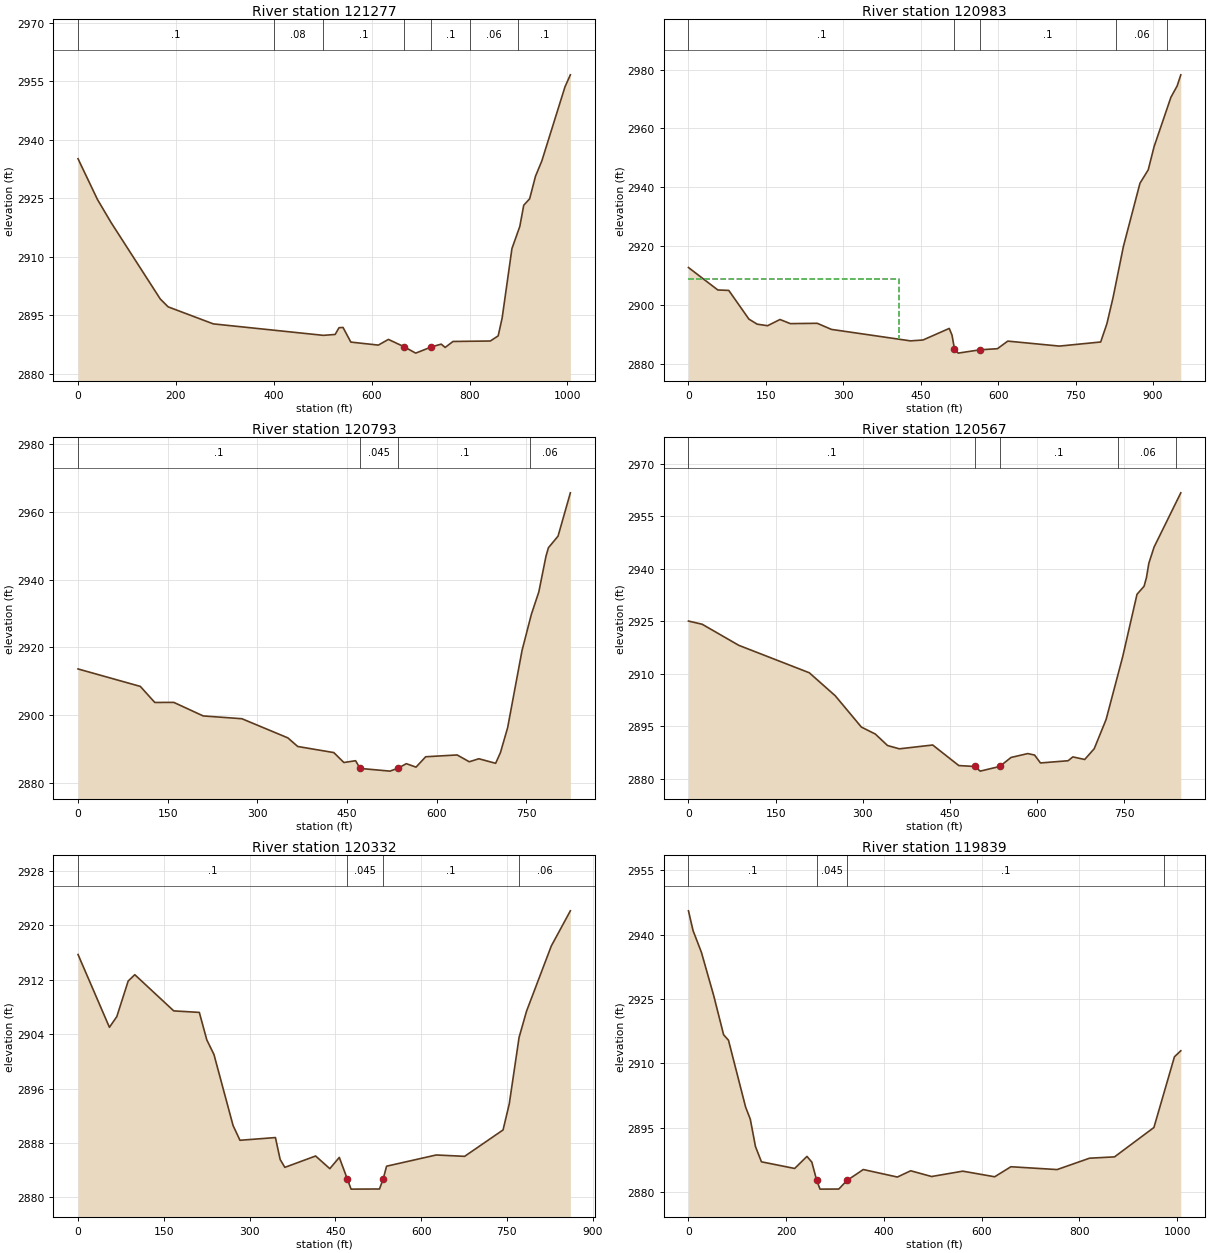
Type RM Length L Ch R = 1 ,121277  ,294.7,294.7,294.7
XS GIS Cut Line= 2
2355852.69567589661530.8962169562356855.10845393661444.898476303
#Sta/Elev= 30
       0 2935.09    39.6 2924.67    67.7  2918.7   168.1 2899.11   184.2  2897.1
   276.5 2892.73   501.3 2889.79   525.4 2890.02   533.4 2891.75   541.5 2891.82
   557.5 2888.06   613.7 2887.29   634.3 2888.75   666.7 2886.84     690 2885.23
     722 2886.81   742.2 2887.54   750.2 2886.69   766.3 2888.22   842.6 2888.34
   858.6 2889.66   866.7 2894.24   886.7 2912.05   902.8 2917.73   910.8 2923.16
   922.9 2924.83   934.9 2930.63   947.7  2934.5   995.1 2953.54  1006.1 2956.62
#Mann= 7 ,-1,0
       0      .1       0     400     .08       0     500      .1       0
   666.7    .045       0     722      .1       0     800     .06       0
     900      .1       0
Bank Sta=666.7,722
XS Rating Curve= 0 ,0
Exp/Cntr=0.3,0.1

Type RM Length L Ch R = 1 ,120983  ,189.8,189.8,189.8
XS GIS Cut Line= 3
2355919.52215753661791.7587438742356425.63642927661748.953059199
2356871.31914617661759.024985005
#Sta/Elev= 30
       0 2912.76    56.9 2905.14    78.1 2904.99   117.1 2895.24   133.1 2893.53
   153.2    2893   177.3 2895.11   197.4 2893.71   249.5 2893.82   276.9 2891.75
   430.2 2887.85   454.3 2888.15   505.2 2892.08   510.5  2889.8   515.32885.149
   522.4 2883.69   565.32884.836   598.5 2885.19   618.5 2887.77   718.5 2886.08
   798.5 2887.47   810.5 2893.65   822.5 2902.58   842.5  2919.9   874.6 2941.38
   890.6 2945.95   901.9 2953.78   934.6 2970.61   946.6 2974.42   953.7 2978.21
#Mann= 5 ,-1,0
       0      .1       0   515.3    .045       0   565.3      .1       0
  827.92     .06       0  927.92      .1       0
#XS Ineff= 2 , 0
          407.72 2908.87
Permanent Ineff=
       F       F
Bank Sta=515.3,565.3
XS Rating Curve= 0 ,0
Exp/Cntr(USF)=0,0
Exp/Cntr=0.3,0.1

Type RM Length L Ch R = 1 ,120793  ,226.1,226.1,226.1
XS GIS Cut Line= 3
2355997.21418068662012.9178700492356645.89624322      661913.918
2356812.76801668661900.374779708
#Sta/Elev= 30
       0 2913.62   104.2 2908.47   128.4 2903.74   160.3 2903.75   209.4 2899.76
   274.1 2898.94     351 2893.29   367.5 2890.75   427.9 2888.95   444.7 2886.02
   464.3 2886.55   471.8 2884.28   521.9 2883.48     536  2884.4   549.2 2885.68
   565.4 2884.66   581.6 2887.72   634.2 2888.25   654.5 2886.24   670.5 2887.13
   698.6 2885.79   706.6 2888.93   718.7 2896.32   742.8  2919.1   758.3 2929.68
   770.8 2936.32   782.9 2946.93   786.9 2949.38     803 2952.79   823.6 2965.57
#Mann= 4 ,-1,0
       0      .1       0   471.8    .045       0     536      .1       0
  756.19     .06       0
Bank Sta=471.8,536
XS Rating Curve= 0 ,0
Exp/Cntr=0.3,0.1

Type RM Length L Ch R = 1 ,120567  ,235,235,235
XS GIS Cut Line= 2
2356020.96330602662268.6174560872356849.92839291662092.462375122
#Sta/Elev= 30
       0  2925.1    23.7 2924.18    86.6 2918.16     208 2910.31   252.7 2903.73
   297.7 2894.77   321.7 2892.78   342.7  2889.5   363.1 2888.56   420.4 2889.65
   465.4 2883.77     493 2883.51   502.2 2882.18   535.82883.519   555.3 2886.09
     584  2887.2   595.8 2886.78   605.9 2884.52   653.5 2885.15   661.7 2886.25
   682.1 2885.51   698.5  2888.6   718.9 2896.94   747.5 2914.92   772.1 2932.75
   784.3 2935.06   788.4 2937.54   792.5 2941.64   801.5 2946.25   847.5 2961.77
#Mann= 5 ,-1,0
       0      .1       0     493    .045       0   535.8      .1       0
     740     .06       0     840      .1       0
Bank Sta=493,535.8
XS Rating Curve= 0 ,0
Exp/Cntr(USF)=0,0
Exp/Cntr=0.3,0.1

Type RM Length L Ch R = 1 ,120332  ,492.5,492.5,492.5
XS GIS Cut Line= 3
2356098.30839541662514.4036893672356756.92963308662341.371615706
  2356922.880836662271.509599026
#Sta/Elev= 30
       0 2915.71    54.9 2905.01    67.8 2906.58    87.7 2911.81    99.3 2912.74
   167.4 2907.42   212.1  2907.2   225.2 2903.16   237.7 2901.02   271.1 2890.58
   283.2  2888.4   345.2  2888.8   353.5 2885.58   361.7 2884.42   415.5 2886.09
   440.3 2884.23   456.9 2885.88   470.9 2882.72   477.5 2881.22   527.2 2881.24
   533.8 2882.75   539.6 2884.59   626.4 2886.24   676.1 2886.04   743.3 2889.92
   754.2 2893.77   771.3 2903.52   784.4 2907.39   827.7 2916.97     861 2922.13
#Mann= 4 ,-1,0
       0      .1       0   470.9    .045       0   533.8      .1       0
  770.97     .06       0
Bank Sta=470.9,533.8
XS Rating Curve= 0 ,0
Exp/Cntr=0.3,0.1

Type RM Length L Ch R = 1 ,119839  ,189.4,189.4,189.4
XS GIS Cut Line= 3
2356362.83928839663040.9976101462356676.79746907662803.613706047
2357058.41164976662322.963344684
#Sta/Elev= 30
       0 2945.54     9.4 2940.93    26.5 2935.86    51.8 2925.71    71.9 2916.65
    81.9 2915.36     117 2899.75   126.5 2896.96   137.1 2890.58   149.3 2887.02
   217.3 2885.47   242.4 2888.28   252.4 2886.95   262.4 2882.68   269.2 2880.65
   307.6 2880.67   324.42882.674   357.7 2885.22   427.4 2883.47   454.7 2884.93
   497.4 2883.59   561.3 2884.84   626.5 2883.53   659.7 2885.87   754.2 2885.21
   820.6 2887.86   871.7 2888.17   952.3 2895.02   994.3 2911.51  1007.3 2912.91
#Mann= 4 ,-1,0
       0      .1       0   262.4    .045       0   324.4      .1       0
   973.6     .06       0
Bank Sta=262.4,324.4
XS Rating Curve= 0 ,0
Exp/Cntr=0.3,0.1

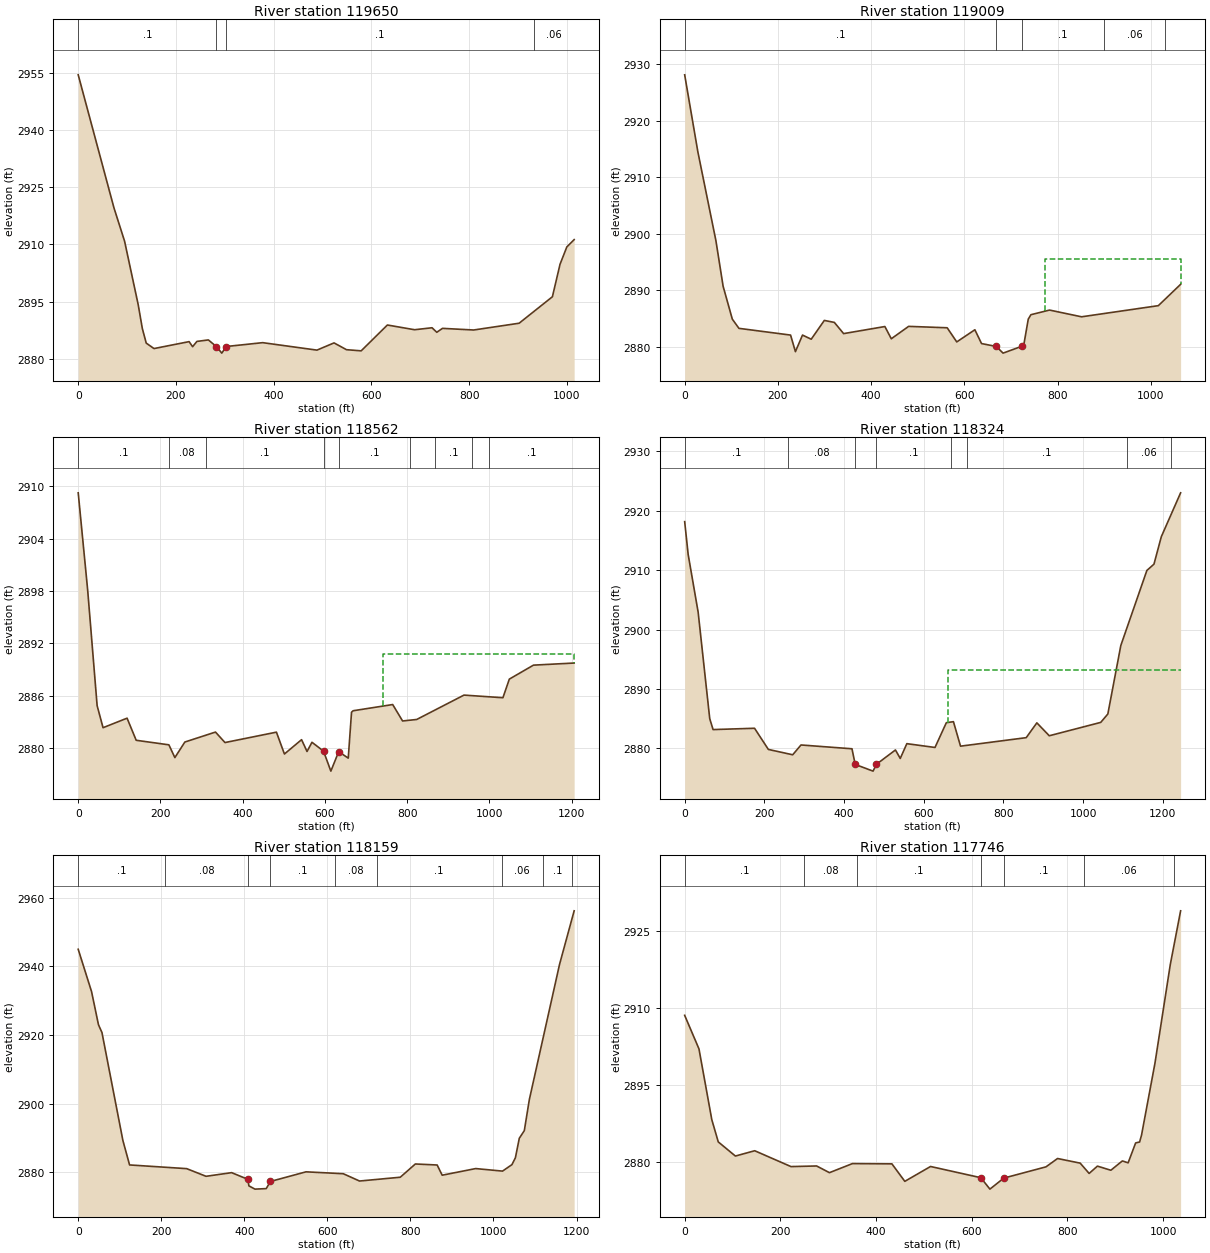
Type RM Length L Ch R = 1 ,119650  ,640.7,640.7,640.7
XS GIS Cut Line= 3
2356594.31066936663215.2766250732356786.02977707662884.867099016
2357108.28104323662340.303250514
#Sta/Elev= 30
       0 2954.59    73.1 2919.64    94.9 2910.85   122.7  2894.2   131.2  2887.9
   139.2 2884.06   155.1 2882.63   226.9 2884.45   234.1 2883.12   242.9 2884.51
   266.3  2884.9   282.7 2883.16   293.8 2881.43     303 2883.17   377.5 2884.18
   488.5 2882.22   523.5 2884.12     549 2882.33     579 2882.03   632.6 2888.82
   688.4 2887.58     724  2888.1   733.7 2886.91   745.4 2887.94   809.2 2887.51
   902.2 2889.29   970.3 2896.25   985.9 2904.78   999.8 2909.34  1014.8 2911.27
#Mann= 4 ,-1,0
       0      .1       0   282.7    .045       0     303      .1       0
     932     .06       0
Bank Sta=282.7,303
XS Rating Curve= 0 ,0
Exp/Cntr(USF)=0,0
Exp/Cntr=0.3,0.1

Type RM Length L Ch R = 1 ,119009  ,447.4,447.4,447.4
XS GIS Cut Line= 3
2356796.22760195 663409.035297762357163.34929757662960.331003115
2357450.92795914662570.774092764
#Sta/Elev= 30
       0 2928.12    28.3  2914.5      67 2898.81    82.5 2890.74   102.2 2884.94
   116.4 2883.31   227.2 2882.12   237.6 2879.19   252.8 2882.12   271.5 2881.39
   299.6 2884.71   321.1 2884.36     341 2882.38   429.5 2883.63   443.3 2881.47
   480.5 2883.66   563.2 2883.41   583.7 2880.91   622.6 2883.06   636.9 2880.62
   668.4 2880.11   683.1 2878.93   722.9 2880.13   727.9 2880.55   737.1 2884.93
   742.8 2885.72   782.8 2886.54   851.5 2885.35  1016.2 2887.32    1064 2891.09
#Mann= 5 ,-1,0
       0      .1       0   668.4    .045       0   722.9      .1       0
  899.75     .06       0 1029.75      .1       0
#XS Ineff= 2 , 0
                          773.15         2895.61
Permanent Ineff=
       F       F
Bank Sta=668.4,722.9
XS Rating Curve= 0 ,0
Exp/Cntr(USF)=0,0
Exp/Cntr=0.3,0.1

Type RM Length L Ch R = 1 ,118562  ,238,238,238
XS GIS Cut Line= 4
2356882.03907306663518.9877222882357310.34771795663226.650075777
2357539.23223188663237.9809923092357888.22446105662941.110979185
#Sta/Elev= 30
       0 2909.23      23  2898.1      46 2884.87    60.4 2882.35   118.8 2883.44
     141 2880.91   220.5 2880.39     235 2878.93   259.3 2880.71   333.8 2881.85
   356.9 2880.65     482 2881.84   501.4 2879.34   543.1 2880.98   556.4 2879.63
   568.4 2880.68   596.5 2879.67   614.3 2877.38   633.4 2879.61   656.6 2878.87
   664.6 2884.12   668.6 2884.29   764.7    2885   788.7 2883.12     823 2883.29
     938 2886.08  1032.7 2885.78  1048.3 2887.91    1107 2889.51  1205.9 2889.75
#Mann= 9 ,-1,0
       0      .1       0     220     .08       0     310      .1       0
   596.5    .045       0   633.4      .1       0  807.73     .08       0
  867.73      .1       0  957.73     .08       0  997.73      .1       0
#XS Ineff= 2 , 0
                          742.28         2890.73
Permanent Ineff=
       F       F
Bank Sta=596.5,633.4
XS Rating Curve= 0 ,0
Exp/Cntr(USF)=0,0
Exp/Cntr=0.3,0.1

Type RM Length L Ch R = 1 ,118324  ,164.6,164.6,164.6
XS GIS Cut Line= 4
2356887.71942844663572.9930952612357255.42676552663466.337485533
 2357499.7447154663431.2797142182358052.20193128663160.375034361
#Sta/Elev= 30
       0 2918.16     8.8 2912.62    33.8 2902.94    62.9 2885.02    71.3 2883.18
   175.4  2883.4   210.1 2879.84   271.2 2878.94     292 2880.59     420 2879.95
   428.1 2877.32   472.9 2876.19   481.42877.342   529.1 2879.75   541.2 2878.32
   557.7 2880.81   628.4 2880.17   656.9 2884.34   674.7 2884.51   692.5 2880.39
   857.4 2881.82   884.1 2884.31   915.3 2882.14  1044.5 2884.39  1062.3  2885.8
  1094.9 2897.33  1160.3 2909.95  1178.1 2911.01  1196.5 2915.62    1245 2923.01
#Mann= 8 ,-1,0
       0      .1       0     260     .08       0   428.1    .045       0
   481.4      .1       0  669.68     .08       0  709.68      .1       0
 1109.68     .06       0 1219.68      .1       0
#XS Ineff= 2 , 0
                          660.07         2893.13
Permanent Ineff=
       F       F
Bank Sta=428.1,481.4
XS Rating Curve= 0 ,0
Exp/Cntr=0.3,0.1

Type RM Length L Ch R = 1 ,118159  ,413.4,413.4,413.4
XS GIS Cut Line= 3
2356933.27330302663739.5920257392357489.74720378663578.441212848
2358099.09871503663495.347824951
#Sta/Elev= 30
       0 2944.99    32.2 2932.63    48.8    2923    57.2 2920.73   107.6 2889.26
   123.7 2882.14   261.2 2881.06   307.8 2878.83   369.5 2879.89   408.22877.966
   411.1 2876.04   425.7 2875.09   452.8 2875.24   462.8 2877.32   548.6 2880.13
   638.3 2879.58   677.5 2877.45   775.6 2878.56   811.9 2882.42   864.4 2882.12
   876.5 2879.15   957.2 2881.08  1021.8 2880.34  1044.5 2882.23  1052.8 2884.22
  1062.2 2889.91  1074.3 2892.14  1086.4  2901.2  1159.1 2940.58  1194.3  2956.2
#Mann= 9 ,-1,0
       0      .1       0     210     .08       0   408.2    .045       0
   462.8      .1       0  619.34     .08       0  719.34      .1       0
 1019.34     .06       0 1119.34      .1       0 1189.34     .06       0
Bank Sta=408.2,462.8
XS Rating Curve= 0 ,0
Exp/Cntr(USF)=0,0
Exp/Cntr=0.3,0.1

Type RM Length L Ch R = 1 ,117746  ,273.7,273.7,273.7
XS GIS Cut Line= 4
2357109.53200462664009.0160410422357587.94848039663767.289821705
2357731.47342312663631.3188233282358033.63119729663611.174971716
#Sta/Elev= 30
       0 2908.54    29.9 2902.01    56.7 2888.26    70.2 2883.94     106 2881.19
   146.4 2882.22   222.2 2879.14   275.8 2879.26   302.6 2877.96   350.6 2879.72
   433.2 2879.67   460.1 2876.27   513.9 2879.16     619 2876.98     638 2874.76
     667  2876.9   755.2 2879.09   779.4 2880.71   826.7 2879.81   845.4 2877.81
   862.7 2879.23   890.8 2878.43   914.8 2880.24   926.9 2879.87   942.6 2883.74
   950.9 2883.92   954.9 2885.25     983 2899.25    1015  2918.4  1036.6 2928.85
#Mann= 7 ,-1,0
       0      .1       0     250     .08       0     360      .1       0
     619    .045       0     667      .1       0  833.72     .06       0
 1023.72      .1       0
Bank Sta=619,667
XS Rating Curve= 0 ,0
Exp/Cntr(USF)=0,0
Exp/Cntr=0.3,0.1

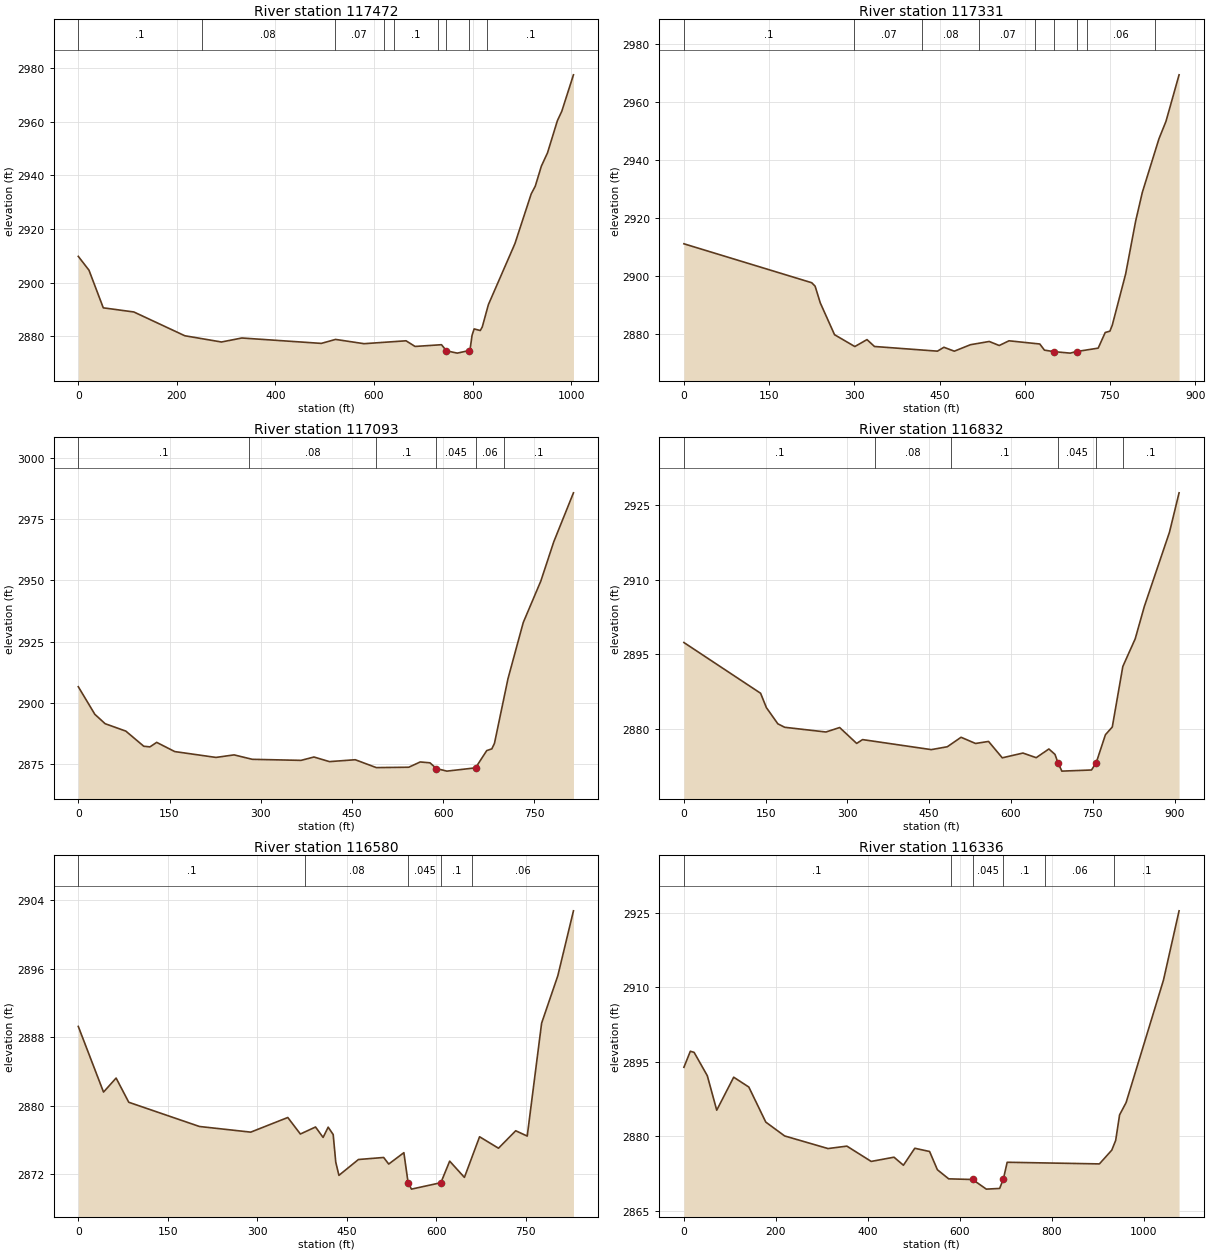
Type RM Length L Ch R = 1 ,117472  ,140.8,140.8,140.8
XS GIS Cut Line= 2
2357127.15787478664051.8217257162358099.09871503663797.505599122
#Sta/Elev= 30
       0 2909.81    21.7 2904.65    50.7 2890.62   112.7 2889.08   216.1 2880.21
   290.5 2877.88   331.8 2879.37   493.1 2877.36     522 2878.84   579.9 2877.25
     665 2878.33   683.3 2876.22     737 2876.87   746.9  2874.6   768.9 2873.73
   792.9 2874.69   794.9  2875.1     799 2880.41   803.2 2882.76   815.6 2882.16
   819.7  2883.5   832.1 2891.82   885.9 2914.54   918.9 2933.08   927.2 2935.98
   939.6 2943.47     952  2948.4   972.1 2960.42     981 2963.91  1004.7 2977.51
#Mann= 9 ,-1,0
       0      .1       0     250     .08       0     520     .07       0
     620     .08       0     640      .1       0     730     .06       0
   746.9    .045       0   792.9     .06       0     830      .1       0
Bank Sta=746.9,792.9
XS Rating Curve= 0 ,0
Exp/Cntr(USF)=0,0
Exp/Cntr=0.3,0.1

Type RM Length L Ch R = 1 ,117331  ,238.5,238.5,238.5
XS GIS Cut Line= 3
2357258.60576567664257.3843915222357785.80279305664018.481127171
2358070.55932795663950.085413793
#Sta/Elev= 30
       0 2911.03     225  2897.6     231  2896.4   240.1 2890.63   265.2 2879.67
   300.9 2875.59   322.3 2877.98   335.5 2875.61   446.3    2874   457.7 2875.34
     476 2873.99   504.4 2876.22   537.5 2877.34   555.1 2875.95   572.3 2877.57
   626.5 2876.47   634.7 2874.35   651.2 2873.84     680 2873.32   691.3 2873.87
   729.3 2875.04   741.7 2880.44   749.9 2880.89     754 2882.89   777.6 2900.58
   795.2  2918.8     807 2928.76   836.3 2947.25   848.6 2953.23   871.7  2969.3
#Mann= 9 ,-1,0
       0      .1       0     300     .07       0     420     .08       0
     520     .07       0   618.8     .08       0   651.2    .045       0
   691.3     .08       0   708.8     .06       0   828.8      .1       0
Bank Sta=651.2,691.3
XS Rating Curve= 0 ,0
Exp/Cntr=0.3,0.1

Type RM Length L Ch R = 1 ,117093  ,260.3,260.3,260.3
XS GIS Cut Line= 2
2357366.52196577 664428.189720942358134.75810661664158.513907492
#Sta/Elev= 30
       0 2906.64    27.2 2895.38    44.1 2891.55    78.1 2888.53   107.7 2882.34
   117.8 2882.09   128.9 2883.92   158.6 2880.17   226.4 2877.78   256.1 2878.82
   286.1 2877.01   366.3 2876.58   387.5 2877.95     413 2876.07   455.4 2876.84
     490 2873.63   543.4 2873.78   562.2 2875.93   578.3 2875.58   588.8 2873.25
   606.1 2872.19   653.2 2873.53   671.6 2880.57     680 2881.28   684.3 2883.52
   706.5 2909.88   731.6 2932.81   760.6 2949.81   781.8 2965.77   814.2 2985.77
#Mann= 6 ,-1,0
       0      .1       0     280     .08       0     490      .1       0
   588.8    .045       0   653.2     .06       0     700      .1       0
Bank Sta=588.8,653.2
XS Rating Curve= 0 ,0
Exp/Cntr(USF)=0,0
Exp/Cntr=0.3,0.1

Type RM Length L Ch R = 1 ,116832  ,252.4,252.4,252.4
XS GIS Cut Line= 3
2357360.17884693664686.1644135072357840.90767589664531.641122167
2358224.78524698664407.920989992
#Sta/Elev= 30
       0 2897.32   140.7  2887.1   151.3 2884.21   172.3 2880.95   184.9 2880.25
   260.5  2879.3   285.7  2880.2   316.9    2877   327.7 2877.77   453.8 2875.75
   483.2 2876.33   508.4 2878.24   534.9 2876.99   558.8  2877.4     584  2874.1
   621.9 2875.06   646.2 2874.13   669.5 2875.88   680.7 2874.79     686 2873.15
   693.3 2871.42   747.7 2871.65   756.3 2873.11   773.2 2878.75   785.8 2880.31
   805.1 2892.49   827.8 2898.06   844.6 2904.59   890.7 2919.54   908.3 2927.47
#Mann= 6 ,-1,0
       0      .1       0     350     .08       0     490      .1       0
     686    .045       0   756.3     .06       0  804.95      .1       0
Bank Sta=686,756.3
XS Rating Curve= 0 ,0
Exp/Cntr=0.3,0.1

Type RM Length L Ch R = 1 ,116580  ,243.6,243.6,243.6
XS GIS Cut Line= 3
2357568.21228003664892.7572987282358218.60688894664668.405151406
2358336.44842086664589.088735686
#Sta/Elev= 30
       0 2889.24    42.3 2881.57    63.4 2883.21    84.6 2880.38   203.1 2877.55
   289.1 2876.89   351.2  2878.6   372.3 2876.67   397.7 2877.49   410.4 2876.27
   418.9 2877.47   427.3 2876.61   431.6 2873.39   436.9 2871.84   469.6 2873.69
   511.9 2873.93   520.4 2873.16   545.8 2874.49   552.92870.979   558.5 2870.23
   607.8 2870.98   622.6  2873.5   647.3  2871.6   672.7 2876.35   704.4 2875.01
   733.3 2877.05   752.6 2876.43   776.7 2889.62   803.9 2895.17   830.1 2902.75
#Mann= 5 ,-1,0
       0      .1       0     380     .08       0   552.9    .045       0
   607.8      .1       0     660     .06       0
Bank Sta=552.9,607.8
XS Rating Curve= 0 ,0
Exp/Cntr(USF)=0,0
Exp/Cntr=0.3,0.1

Type RM Length L Ch R = 1 ,116336  ,234.5,234.5,234.5
XS GIS Cut Line= 3
2357562.53813582665063.2082160442358299.75378233 664895.35353355
2358513.52215057664655.851531927
#Sta/Elev= 30
       0 2893.85      14 2897.08    22.2 2896.85    50.9 2892.15    71.4 2885.21
   108.3 2891.85   141.2 2889.87   178.1 2882.81   219.1 2880.02   313.5 2877.48
   354.5 2877.97   407.4 2874.89     457 2875.74   477.5 2874.12   502.2 2877.54
   534.4 2876.89   551.4 2873.21     576 2871.38   627.9 2871.25   657.8 2869.31
   686.8 2869.45   694.8 2871.32   703.2 2874.72   903.8 2874.39   930.7 2877.16
   939.2 2879.12   947.7 2884.26   961.9 2886.75  1043.2 2911.42  1077.1 2925.36
#Mann= 6 ,-1,0
       0      .1       0     580     .08       0   627.9    .045       0
   694.8      .1       0  786.08     .06       0  936.08      .1       0
Bank Sta=627.9,694.8
XS Rating Curve= 0 ,0
Exp/Cntr=0.3,0.1