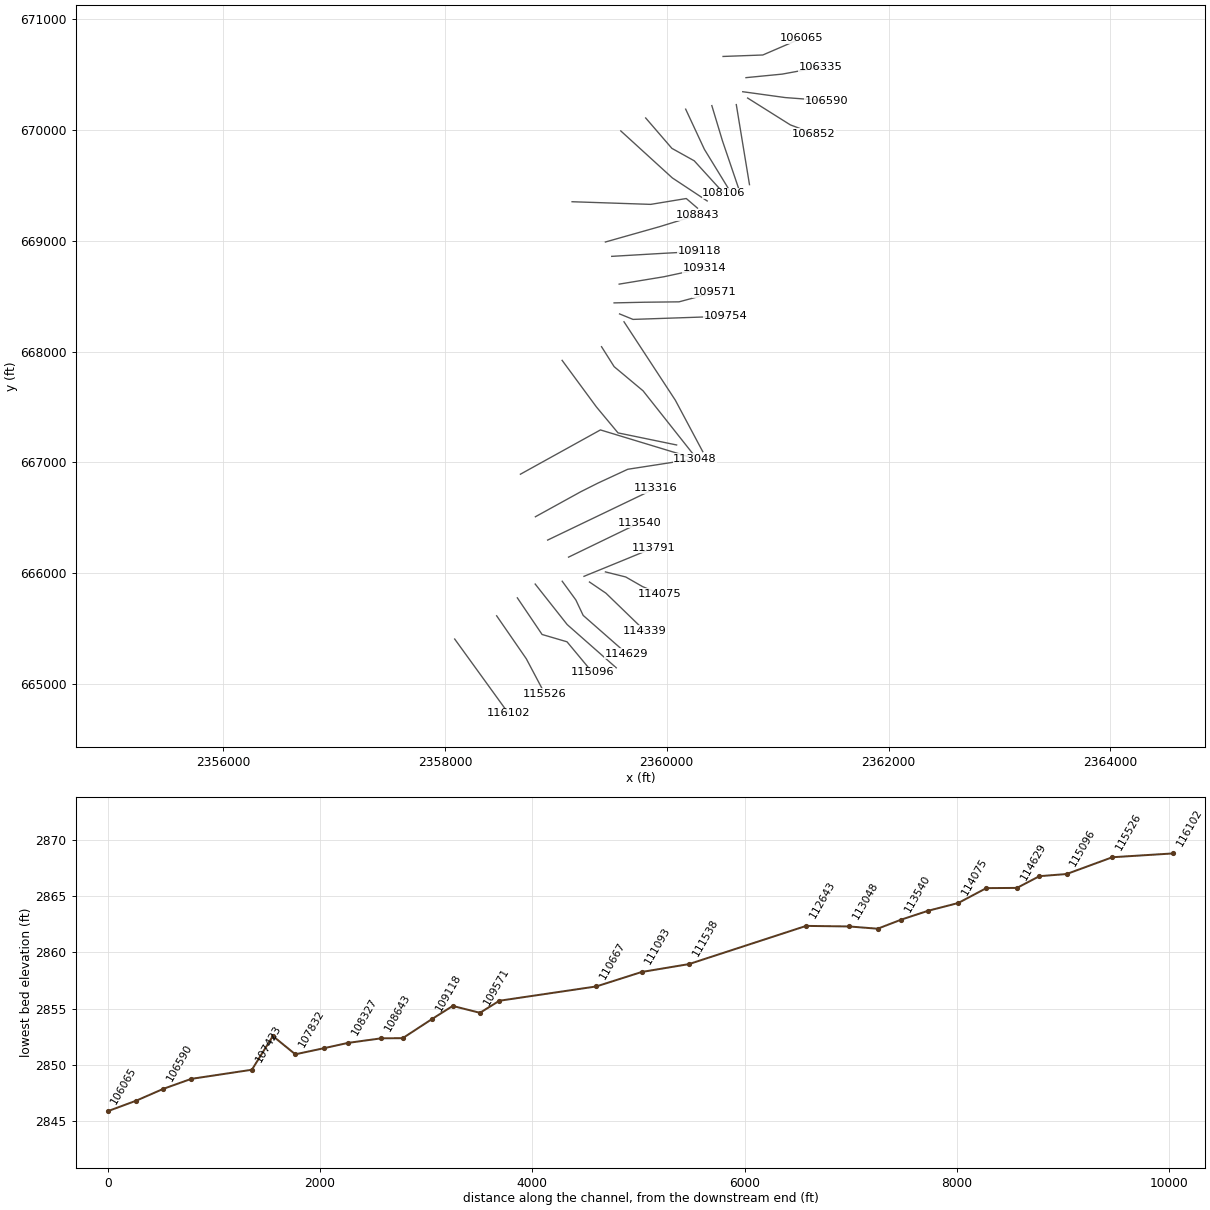
HEC-RAS study LAURELFK.prj: LAURELFK

--- LAURELFK.g01 (geometry) --- (continued)

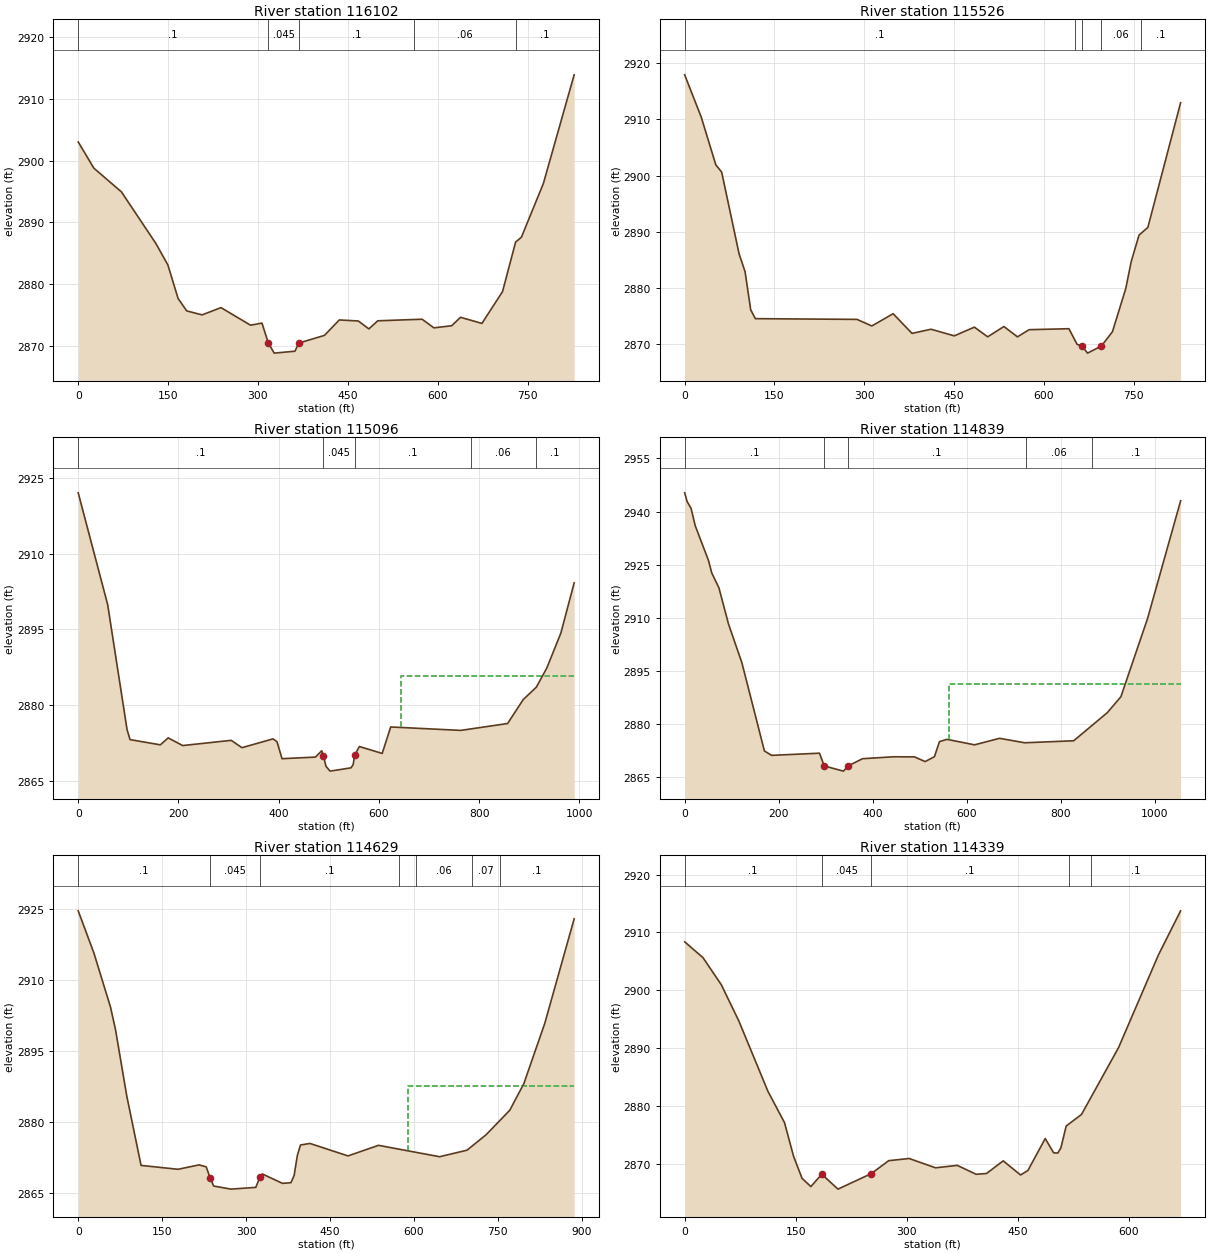
Type RM Length L Ch R = 1 ,116102  ,575.5,575.5,575.5
XS GIS Cut Line= 2
2358088.45879463665406.2704676452358573.42202217664735.480208985
#Sta/Elev= 30
       0 2903.03      26 2898.79    72.2 2894.92   129.7 2886.55   149.7 2883.07
   166.7 2877.64   181.1 2875.63   206.8 2874.98   238.3 2876.16   287.6 2873.31
   306.7 2873.65   317.2 2870.44   327.1 2868.78   361.7 2869.09   368.2 2870.41
     411 2871.66   435.7 2874.16   467.5 2873.99   485.1 2872.71   499.9 2874.02
   573.9 2874.28   593.6 2872.88   623.3 2873.22   638.1 2874.59   673.8  2873.6
   708.2 2878.76     730 2886.79   739.7 2887.58   776.3 2896.28   827.7 2913.91
#Mann= 5 ,-1,0
       0      .1       0   317.2    .045       0   368.2      .1       0
     560     .06       0     730      .1       0
Bank Sta=317.2,368.2
XS Rating Curve= 0 ,0
Exp/Cntr(USF)=0,0
Exp/Cntr=0.3,0.1

Type RM Length L Ch R = 1 ,115526  ,430.7,430.7,430.7
XS GIS Cut Line= 3
2358466.70319769  665616.02349842358734.33491379665227.792305284
2358901.19172445  664912.2512079
#Sta/Elev= 30
       0 2917.93    27.7  2910.4      52 2901.93    61.8 2900.63    90.9 2886.09
   100.9 2882.92   110.3 2876.14   118.1 2874.57   287.8 2874.44   312.7 2873.27
   348.2 2875.45   379.8 2871.95   411.5 2872.69   450.4 2871.51     484 2873.06
   506.2 2871.34   533.3 2873.17   555.9 2871.34   575.5 2872.61   641.9 2872.78
   655.5 2870.01   663.7 2869.68   673.1 2868.44   696.2 2869.71   714.6 2872.24
   736.9 2879.94     746 2884.73     759 2889.42   773.8  2890.8   828.5 2912.97
#Mann= 5 ,-1,0
       0      .1       0  651.54     .06       0   663.7    .045       0
   696.2     .06       0  761.54      .1       0
Bank Sta=663.7,696.2
XS Rating Curve= 0 ,0
Exp/Cntr(USF)=0,0
Exp/Cntr=0.3,0.1

Type RM Length L Ch R = 1 ,115096  ,256.3,256.3,256.3
XS GIS Cut Line= 4
2358653.38457991665777.924166168   2358876.41101665447.514640111
2359101.08948772  665381.43273492359329.07206069665107.192828273
#Sta/Elev= 30
       0 2922.02    58.8 2899.89    97.4  2875.2   103.4 2873.19   163.9 2872.15
   179.5 2873.53   208.4 2872.01   305.3 2873.04   326.7 2871.59   388.6 2873.33
   396.6 2872.77   406.7 2869.41   473.4 2869.73   485.9 2870.98   489.3 2870.02
   494.3 2867.91   502.6 2866.95   544.3  2867.6   548.5 2868.22   551.8 2870.17
     561 2871.82   606.5 2870.45   623.5 2875.69   763.2 2875.01   856.7 2876.37
     888 2881.12   914.1 2883.57   934.9 2887.34     963 2894.27   989.5  2904.2
#Mann= 5 ,-1,0
       0      .1       0   489.3    .045       0   551.8      .1       0
  782.83     .06       0  912.83      .1       0
#XS Ineff= 2 , 0
                           644.3         2885.83
Permanent Ineff=
       F       F
Bank Sta=489.3,551.8
XS Rating Curve= 0 ,0
Exp/Cntr(USF)=0,0
Exp/Cntr=0.3,0.1

Type RM Length L Ch R = 1 ,114839  ,210.9,210.9,210.9
XS GIS Cut Line= 3
 2358814.2863862665902.4124704382359102.86298655665536.688441765
2359545.07528673665146.717198933
#Sta/Elev= 30
       0  2945.3     5.1 2942.87    13.6 2940.92    22.4 2936.04    50.6 2926.24
    57.6 2922.71    72.9 2918.48    93.3 2908.27   121.8 2897.33   169.7 2872.45
     185 2871.21   286.9 2871.82   297.1 2868.22   337.9 2866.76     348 2868.23
   378.6 2870.27   444.9 2870.81   489.1 2870.78   511.8 2869.45   531.6 2870.84
   542.3 2875.09   558.3 2875.73   616.9 2874.18   670.3 2876.02   723.6 2874.76
     828 2875.33   899.6 2883.28   928.4 2887.76   985.1 2909.81  1055.5 2943.05
#Mann= 5 ,-1,0
       0      .1       0   297.1    .045       0     348      .1       0
  725.87     .06       0  865.87      .1       0
#XS Ineff= 2 , 0
                          561.74         2891.34
Permanent Ineff=
       F       F
Bank Sta=297.1,348
XS Rating Curve= 0 ,0
Exp/Cntr=0.3,0.1

Type RM Length L Ch R = 1 ,114629  ,289.2,289.2,289.2
XS GIS Cut Line= 4
2359057.79744093665927.9700933292359180.78320897665759.094113345
2359246.86511418 665619.587869012359639.68532849665274.493475129
#Sta/Elev= 30
       0 2924.63    28.2 2915.65    57.9 2904.17    66.7 2899.45    86.7 2885.48
   112.3 2870.74   178.4 2869.92   215.9 2870.85   228.7 2870.44   235.5 2868.18
     242 2866.38   272.9 2865.72   317.3 2866.09   324.82868.278     329 2868.93
     365 2866.94   380.1 2867.08   385.8  2868.6   391.6 2872.87   397.2 2875.06
   414.1 2875.39   482.1 2872.75   536.6 2874.99   645.7 2872.58   694.7 2873.96
   728.7 2877.21   771.2 2882.42   796.3 2888.05   833.6 2900.77   886.2 2922.93
#Mann= 7 ,-1,0
       0      .1       0   235.5    .045       0   324.8      .1       0
  573.28     .07       0  603.28     .06       0  703.28     .07       0
  753.28      .1       0
#XS Ineff= 2 , 0
                          588.93         2887.57
Permanent Ineff=
       F       F
Bank Sta=235.5,324.8
XS Rating Curve= 0 ,0
Exp/Cntr(USF)=0,0
Exp/Cntr=0.3,0.1

Type RM Length L Ch R = 1 ,114339  ,264,264,264
XS GIS Cut Line= 3
2359303.65661584665921.0079402392359451.92665587665820.231127171
2359804.35434413665478.734608478
#Sta/Elev= 30
       0 2908.39    24.8 2905.65    49.5 2900.98    73.2 2894.72   112.5 2882.58
   134.9 2877.17   147.1 2871.37   158.6 2867.56   170.5 2866.14   185.2 2868.27
   207.1  2865.7     252 2868.37   275.6 2870.61   303.2 2870.99   338.9 2869.38
   368.3  2869.8   393.8 2868.26   407.8  2868.4   430.3 2870.58   453.8 2868.14
   463.7 2868.92   487.1 2874.43   498.4 2871.97   504.1 2871.93   508.2  2872.8
   515.4 2876.59   536.1 2878.59   586.2 2890.14   639.9 2906.09     670 2913.74
#Mann= 5 ,-1,0
       0      .1       0   185.2    .045       0     252      .1       0
  519.28     .07       0  549.28      .1       0
Bank Sta=185.2,252
XS Rating Curve= 0 ,0
Exp/Cntr=0.3,0.1

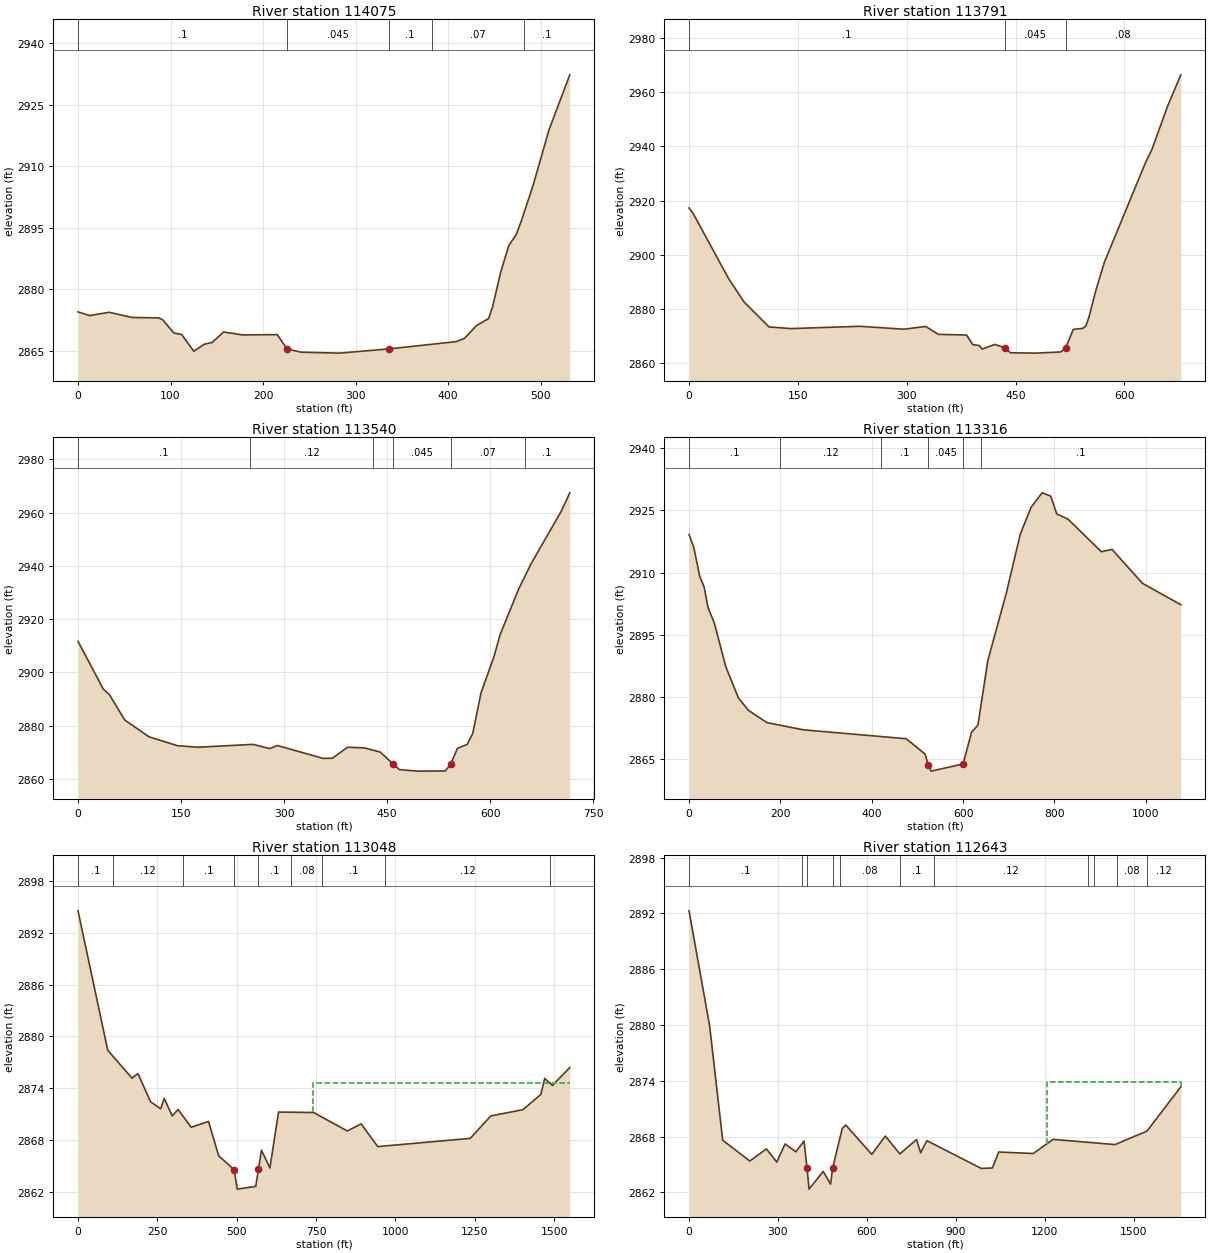
Type RM Length L Ch R = 1 ,114075  ,284.5,284.5,284.5
XS GIS Cut Line= 4
2359447.54741111666012.296576625 2359630.5072861665966.517871369
 2359781.0271813665880.2442728992359936.90433057665813.962043413
#Sta/Elev= 30
       0 2874.43    12.8 2873.54    33.6 2874.34    58.4 2873.08    87.2 2872.97
    91.4 2872.54   103.7 2869.28   112.1 2868.91   125.1 2864.85   136.7 2866.57
     145 2866.97   157.3 2869.54   177.9 2868.82   215.4 2868.89   225.92865.384
   241.2 2864.61   282.7 2864.38     3362865.411     409 2867.19   417.7 2867.99
   430.7 2871.09   443.8 2872.82   448.1 2875.71   456.8 2884.08   465.5 2890.59
   473.6 2893.29   478.5 2896.23   491.6  2905.1     509 2918.79   531.5 2932.25
#Mann= 5 ,-1,0
       0      .1       0   225.9    .045       0     336      .1       0
  382.09     .07       0  482.09      .1       0
Bank Sta=225.9,336
XS Rating Curve= 0 ,0
Exp/Cntr(USF)=0,0
Exp/Cntr=0.3,0.1

Type RM Length L Ch R = 1 ,113791  ,251,251,251
XS GIS Cut Line= 3
2359254.22093259665972.2511621992359622.74988284666123.022216956
2359881.06919959 666229.74740153
#Sta/Elev= 30
       0 2917.27     5.3 2915.44    54.3 2891.31    75.8 2882.58   110.2 2873.36
   140.4 2872.75   234.9  2873.6     296 2872.53   326.2 2873.53   343.5 2870.62
   382.4 2870.38   391.1 2866.81   399.7 2866.49     404  2865.2   421.4 2866.91
   435.3 2865.64     443 2863.82   477.2 2863.69   512.2 2864.12   519.1 2865.66
   529.5 2872.46   542.5 2872.84   546.9 2873.75     551 2876.87   560.2 2886.45
   572.4 2897.28   629.1 2934.07   637.8 2938.83   659.4 2954.81   677.7 2966.43
#Mann= 3 ,-1,0
       0      .1       0   435.3    .045       0   519.1     .08       0
Bank Sta=435.3,519.1
XS Rating Curve= 0 ,0
Exp/Cntr=0.3,0.1

Type RM Length L Ch R = 1 ,113540  ,223.8,223.8,223.8
XS GIS Cut Line= 2
 2359115.0210874666145.4890607162359759.31966321666457.542501992
#Sta/Elev= 30
       0 2911.64    36.8 2893.73    45.7 2891.65    67.9 2882.14   103.5 2875.77
   144.4 2872.48   174.6 2871.88   254.6 2872.96   279.1 2871.38   290.2 2872.53
   356.9 2867.69   370.2 2867.76   392.4 2871.88   416.9 2871.62   439.8 2870.07
   458.8 2865.59     468 2863.47   494.4 2862.91   534.6 2862.95   542.6 2865.57
   552.4 2871.47   566.5 2872.92   574.6 2877.03   586.6 2892.18   605.5  2905.9
   614.6 2914.21   641.6 2931.34   659.4  2940.7   703.5 2960.48   715.9 2967.39
#Mann= 6 ,-1,0
       0      .1       0     250     .12       0     430      .1       0
   458.8    .045       0   542.6     .07       0     650      .1       0
Bank Sta=458.8,542.6
XS Rating Curve= 0 ,0
Exp/Cntr(USF)=0,0
Exp/Cntr=0.3,0.1

Type RM Length L Ch R = 1 ,113316  ,268.3,268.3,268.3
XS GIS Cut Line= 2
2358926.51297344666299.434781406 2359897.0610171666765.490369127
#Sta/Elev= 30
       0 2919.18    10.7 2915.95    23.5    2909    32.9 2906.57    41.8 2901.45
    55.1 2897.92    80.5 2887.28   108.3  2879.7   130.5 2876.73   170.4 2873.81
   250.3 2872.06   475.3 2869.92   516.6 2866.23   523.52863.666   530.2  2862.1
   599.92863.831   618.6 2871.52   632.4 2873.17   654.1 2888.78   694.1 2904.84
   725.1 2919.23     749  2925.8     773 2929.23   791.7 2928.44     805 2924.13
   829.9 2922.86   902.6 2915.02   925.9 2915.59   992.8 2907.39  1076.6 2902.24
#Mann= 6 ,-1,0
       0      .1       0     200     .12       0     420      .1       0
   523.5    .045       0   599.9     .08       0     640      .1       0
Bank Sta=523.5,599.9
XS Rating Curve= 0 ,0
Exp/Cntr=0.3,0.1

Type RM Length L Ch R = 1 ,113048  ,404.9,404.9,404.9
XS GIS Cut Line= 5
2358816.02439918666509.9447742372359225.72007812666735.923099397
2359379.77079191666813.5429469992359649.14846645 666938.45185384
2360254.23891206 667032.13561717
#Sta/Elev= 30
       0 2894.55    93.8 2878.39   170.3 2875.16   188.9 2875.69   228.6 2872.42
   260.6 2871.61   271.7 2872.82   296.9 2870.78   315.4 2871.53   356.5 2869.47
   411.3 2870.14   443.3 2866.16   491.5 2864.57     502  2862.3     560 2862.62
   568.5 2864.59   578.1 2866.82   604.7 2864.75   631.9 2871.23   742.2 2871.18
   848.7 2869.04   892.2 2869.86   944.4 2867.23  1235.9 2868.18  1300.6 2870.78
  1402.2 2871.51  1458.5 2873.28  1470.6 2875.13  1494.9 2874.32  1549.6 2876.39
#Mann= 9 ,-1,0
       0      .1       0     110     .12       0     330      .1       0
   491.5    .045       0   568.5      .1       0  670.39     .08       0
  770.39      .1       0  967.31     .12       0 1487.31      .1       0
#XS Ineff= 2 , 0
                          741.66          2874.6
Permanent Ineff=
       F       F
Bank Sta=491.5,568.5
XS Rating Curve= 0 ,0
Exp/Cntr=0.3,0.1

Type RM Length L Ch R = 1 ,112643  ,1104.4,1104.4,1104.4
XS GIS Cut Line= 3
 2358680.9258495666893.8676867782359402.46471328667293.526449159
2360200.45605351667050.971448247
#Sta/Elev= 30
       0 2892.27    69.6 2879.87   113.5 2867.61     205 2865.37   260.8 2866.68
   296.2 2865.26   323.8 2867.21   360.4 2866.36   387.8 2867.52   397.9 2864.63
     405 2862.35   452.6 2864.26   477.4 2862.88   484.5 2864.63   516.9 2868.88
   528.6 2869.24   616.4 2866.09   662.2 2868.05   711.1 2866.14   767.3 2867.68
   781.1 2866.26   802.3 2867.56   985.5 2864.58  1023.1 2864.62  1044.5 2866.34
  1161.1 2866.18    1228  2867.7    1437 2867.14  1544.7 2868.59  1658.9 2873.35
#Mann= 11 ,-1,0
       0      .1       0     380     .12       0   397.9    .045       0
   484.5     .12       0     510     .08       0     710      .1       0
  824.83     .12       0 1344.83     .08       0 1364.83     .12       0
 1444.83     .08       0 1544.83     .12       0
#XS Ineff= 2 , 0
                          1207.8         2873.89
Permanent Ineff=
       F       F
Bank Sta=397.9,484.5
XS Rating Curve= 0 ,0
Exp/Cntr(USF)=0,0
Exp/Cntr=0.3,0.1

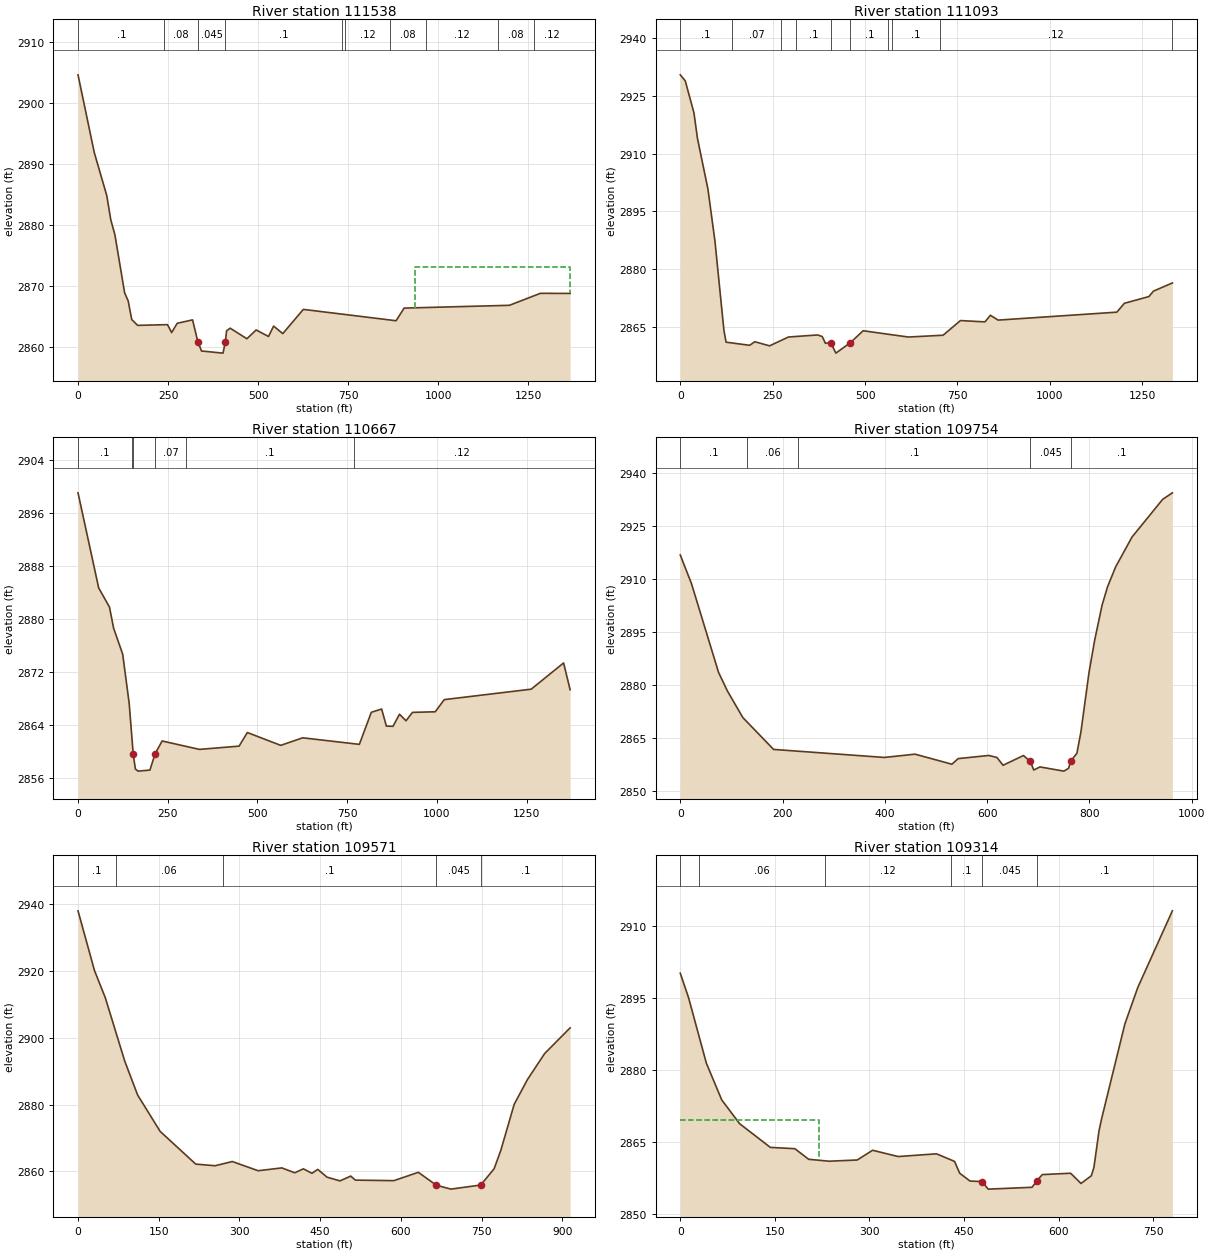
Type RM Length L Ch R = 1 ,111538  ,445.1,445.1,445.1
XS GIS Cut Line= 4
2359057.04248883667921.3033736052359366.25632201667500.898134014
2359560.76986508667266.8380432642360089.25590575667157.710257327
#Sta/Elev= 30
       0 2904.58    45.2 2891.82    79.8 2884.79      91  2880.8   102.5 2878.33
   129.3 2868.85   139.2 2867.52   149.1 2864.47   165.4 2863.51   248.3 2863.63
   259.8 2862.33   275.3 2863.85   317.9 2864.41  332.51 2860.83   342.8 2859.31
   402.4 2858.96  409.09 2860.82   412.3 2862.62   422.2 2863.05   468.7 2861.32
   494.4 2862.76   528.7 2861.69   542.9 2863.39   568.3 2862.16   625.3 2866.13
   882.8 2864.27     905 2866.34  1197.3  2866.8  1283.1 2868.76  1365.8 2868.75
#Mann= 10 ,-1,0
       0      .1       0     240     .08       0  332.51    .045       0
  409.09      .1       0  731.88     .08       0  741.88     .12       0
  866.21     .08       0  966.21     .12       0 1166.21     .08       0
 1266.21     .12       0
#XS Ineff= 2 , 0
                          935.44         2873.07
Permanent Ineff=
       F       F
Bank Sta=332.51,409.09
XS Rating Curve= 0 ,0
Exp/Cntr(USF)=0,0
Exp/Cntr=0.3,0.1

Type RM Length L Ch R = 1 ,111093  ,426.5,426.5,426.5
XS GIS Cut Line= 4
2359412.39446366668044.4920582132359526.10709561667864.447057632
2359786.69854381667646.4978464022360269.97722958667035.292449694
#Sta/Elev= 30
       0  2930.4    13.4 2928.86      37 2920.56    46.5 2913.94    74.9 2900.77
    93.8 2887.36   118.2 2864.14     124  2861.1   187.8 2860.29   201.8 2861.21
   241.7 2860.15   292.9 2862.44   372.1 2862.97   384.3 2862.55   392.9  2860.8
     407 2861.01   421.2 2858.26   460.7    2861     495 2864.06   617.3 2862.43
   711.3  2862.9   758.3  2866.7   824.6 2866.36   839.4 2868.07   860.3 2866.82
  1181.6 2868.88    1202 2871.18  1268.3 2872.92  1280.8 2874.34  1331.9 2876.45
#Mann= 10 ,-1,0
       0      .1       0     140     .07       0  272.95     .08       0
  312.95      .1       0     407    .045       0   460.7      .1       0
  562.67     .12       0  572.67      .1       0  702.67     .12       0
 1331.85      .1       0
Bank Sta=407,460.7
XS Rating Curve= 0 ,0
Exp/Cntr(USF)=0,0
Exp/Cntr=0.3,0.1

Type RM Length L Ch R = 1 ,110667  ,913.1,913.1,913.1
XS GIS Cut Line= 3
2359615.01206954668269.3867422412360078.23135709667561.026543886
2360325.11705548667097.386244098
#Sta/Elev= 30
       0 2899.09    57.6  2884.7    87.7  2881.8    99.2 2878.61   124.5 2874.68
   142.6 2867.23  153.82 2859.56   159.9  2857.3   167.5 2856.98   200.4 2857.14
   214.8 2859.59   234.4 2861.54   338.3 2860.27   448.9 2860.76     472 2862.82
   564.9 2860.88   626.3 2862.02   784.1 2861.03   817.5 2865.88   846.2 2866.38
   859.5 2863.79   877.9 2863.76     896 2865.59   914.2  2864.6   932.3 2865.87
   995.7 2865.96  1020.7  2867.8  1263.1 2869.38  1353.4 2873.35  1371.6  2869.3
#Mann= 6 ,-1,0
       0      .1       0     150     .06       0  153.82    .045       0
   214.8     .07       0     300      .1       0     770     .12       0
Bank Sta=153.82,214.8
XS Rating Curve= 0 ,0
Exp/Cntr(USF)=0,0
Exp/Cntr=0.3,0.1

Type RM Length L Ch R = 1 ,109754  ,182.9,182.9,182.9
XS GIS Cut Line= 3
2359574.94710906668340.4520917252359696.18709973668290.927434453
2360527.08155593668319.333475513
#Sta/Elev= 30
       0 2916.86    21.9 2908.76    74.8 2883.67    92.4 2878.33   122.3 2870.87
   182.5 2861.85   399.1 2859.58   459.1 2860.51   531.2 2857.66   543.4 2859.25
   603.2 2860.14   619.2 2859.57   631.2 2857.37   671.1 2860.12   684.4 2858.44
   691.3 2856.02   703.3  2856.9   750.2 2855.71   759.3 2856.51   763.3 2858.48
   775.6 2860.76   783.4 2866.74   799.3 2883.64   810.4 2892.78   824.8 2902.63
   835.4 2907.82   851.4  2913.5   883.4 2921.94   943.4 2932.61   962.3 2934.44
#Mann= 5 ,-1,0
       0      .1       0     130     .06       0  230.96      .1       0
   684.4    .045       0   763.3      .1       0
#XS Ineff= 2 , 0
                         1168.79          2897.9
Permanent Ineff=
       F       F
Bank Sta=684.4,763.3
XS Rating Curve= 0 ,0
Exp/Cntr(USF)=0,0
Exp/Cntr=0.3,0.1

Type RM Length L Ch R = 1 ,109571  ,256.6,256.6,256.6
XS GIS Cut Line= 4
2359525.53572313668439.9654118482359793.91957776668445.790731194
  2360111.205152668449.4543380812360428.49599469668534.587290953
#Sta/Elev= 30
       0 2938.04    30.6 2920.14    50.7 2911.99    86.7 2893.06   110.7 2882.86
   152.6 2871.94   218.7 2862.14   254.7 2861.65   286.7 2862.91   334.7 2860.15
   378.7    2861   402.7 2859.53   418.7 2860.72   434.7 2859.38   445.4 2860.56
   462.7 2858.22   486.7 2857.11   506.7 2858.55   515.3 2857.34   586.8 2857.18
   632.3 2859.68   665.52855.836   692.7 2854.64   748.3 2855.87   773.1 2860.76
   785.4 2866.19   810.4 2880.07   835.2 2887.53   867.1  2895.3   914.3 2902.97
#Mann= 5 ,-1,0
       0      .1       0      70     .06       0  268.45      .1       0
   665.5    .045       0   748.3      .1       0
Bank Sta=665.5,748.3
XS Rating Curve= 0 ,0
Exp/Cntr(USF)=0,0
Exp/Cntr=0.3,0.1

Type RM Length L Ch R = 1 ,109314  ,196.3,196.3,196.3
XS GIS Cut Line= 3
2359571.28186878668609.2347097322359975.64788489668676.014314265
2360337.85258476 668753.86807406
#Sta/Elev= 30
       0 2900.26    13.1 2895.18    41.4 2881.49    65.8 2873.83    94.2 2868.88
   142.8 2863.95   181.7 2863.68   203.6 2861.47     236 2861.07   280.6 2861.32
     305 2863.35   345.5 2862.04   406.3 2862.61   434.9 2861.03   443.1 2858.56
   459.5 2856.93   478.6 2856.83   488.1 2855.25   557.7 2855.63   565.4 2856.96
     574 2858.28     619 2858.56   635.4 2856.43   651.8 2858.04   655.9 2859.78
     664 2867.42   668.1 2869.93     705 2889.69   725.4 2897.26   780.3 2913.26
#Mann= 6 ,-1,0
       0      .1       0      30     .06       0     230     .12       0
  429.84      .1       0   478.6    .045       0   565.4      .1       0
#XS Ineff= 2 , 0
          220.24 2869.61
Permanent Ineff=
       F       F
Bank Sta=478.6,565.4
XS Rating Curve= 0 ,0
Exp/Cntr=0.3,0.1

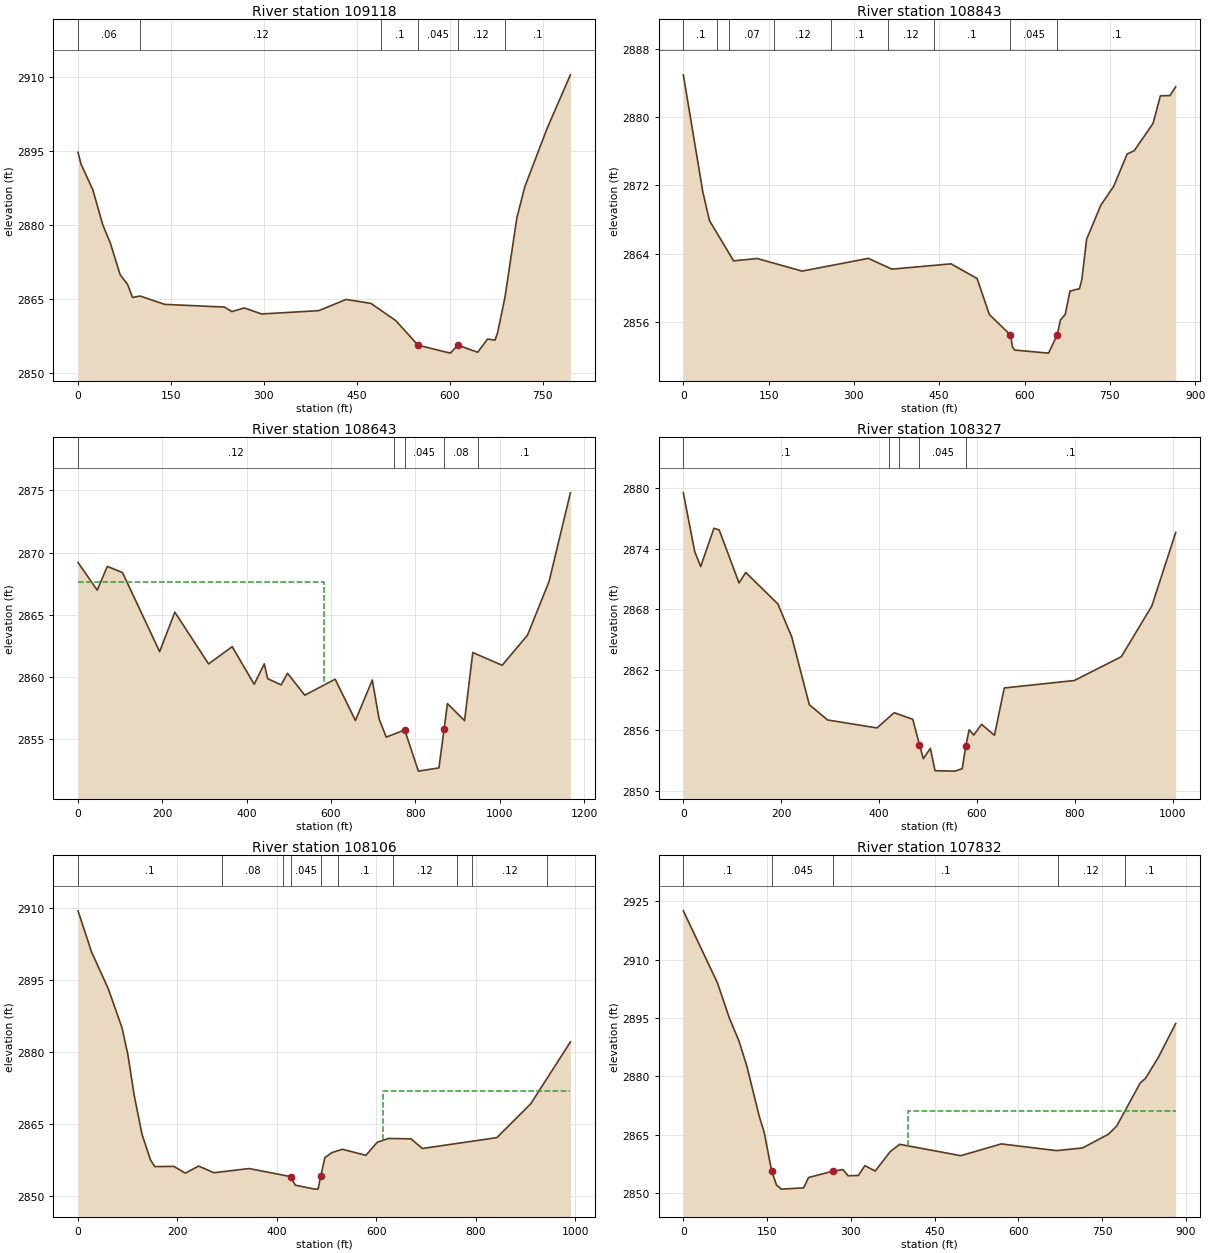
Type RM Length L Ch R = 1 ,109118  ,274.7,274.7,274.7
XS GIS Cut Line= 3
2359504.37162221668859.8853146612359932.42846895668885.065129175
 2360297.5357794668905.208980786
#Sta/Elev= 30
       0  2894.7     4.8 2892.32    23.8 2887.14    39.9 2880.05    51.9 2876.42
    67.9 2869.96    79.9 2867.98      88 2865.34     100 2865.63     140 2863.94
   236.2  2863.4   248.2 2862.48   268.3 2863.22   296.2    2862   388.5 2862.67
   432.5 2864.94   472.6 2864.14   512.7 2860.66   548.7 2855.68   600.8 2854.08
   612.8 2855.69   644.9 2854.25   660.9 2856.93   672.9  2856.7   676.9 2858.16
   688.9 2865.36   708.2  2881.5     721 2887.75     757 2899.56   794.5 2910.37
#Mann= 6 ,-1,0
       0     .06       0     100     .12       0   488.8      .1       0
   548.7    .045       0   612.8     .12       0   688.8      .1       0
Bank Sta=548.7,612.8
XS Rating Curve= 0 ,0
Exp/Cntr(USF)=0,0
Exp/Cntr=0.3,0.1

Type RM Length L Ch R = 1 ,108843  ,200.6,200.6,200.6
XS GIS Cut Line= 3
2359447.16122421668989.4401483892359938.77874194669128.696296777
2360277.79640969669233.319630652
#Sta/Elev= 30
       0 2884.93    34.3 2871.23      46 2867.88    88.4 2863.18   129.9 2863.45
   208.9 2861.98   325.3 2863.47   366.7 2862.21   470.8 2862.83   516.6 2861.11
   538.1  2856.9   575.2 2854.52   578.9  2853.1   582.8 2852.75   642.2 2852.39
   657.7 2854.56   663.1 2856.26   671.5 2856.91   679.9 2859.64   696.6 2859.93
   700.8 2861.01   709.2 2865.72   734.3 2869.71   756.8  2871.9   780.3 2875.66
   792.9 2876.06     826 2879.25   838.9 2882.48   855.7  2882.5   865.8 2883.53
#Mann= 9 ,-1,0
       0      .1       0      60     .06       0      80     .07       0
     160     .12       0     260      .1       0     360     .12       0
     440      .1       0   575.2    .045       0   657.7      .1       0
Bank Sta=575.2,657.7
XS Rating Curve= 0 ,0
Exp/Cntr=0.3,0.1

Type RM Length L Ch R = 1 ,108643  ,315.4,315.4,315.4
XS GIS Cut Line= 4
  2359146.749182669352.8754034952359855.86871386669329.025732543
2360176.36488208669381.8883058962360277.37880883669295.032982949
#Sta/Elev= 30
       0 2869.19    45.5 2866.97    69.5 2868.88   105.5 2868.38   193.5 2862.01
   229.6 2865.19   309.6 2861.02   365.6 2862.41   417.7 2859.38   441.7 2861.03
   449.7 2859.83   481.7 2859.33   496.7 2860.27   537.7  2858.5   609.8 2859.79
   657.8 2856.46   697.8 2859.72   713.9  2856.6   730.8 2855.12   774.7  2855.7
   807.1 2852.38   855.8 2852.64867.99982855.745     876 2857.82   916.6 2856.45
   936.1 2861.94  1005.8 2860.91  1065.9 2863.34    1117 2867.66  1167.6 2874.81
#Mann= 5 ,-1,0
       0     .12       0  749.52      .1       0   774.7    .045       0
867.9998     .08       0  949.52      .1       0
#XS Ineff= 2 , 0
          583.89 2867.63
Permanent Ineff=
       F       F
Bank Sta=774.7,867.9998
XS Rating Curve= 0 ,0
Exp/Cntr(USF)=0,0
Exp/Cntr=0.3,0.1

Type RM Length L Ch R = 1 ,108327  ,221.2,221.2,221.2
XS GIS Cut Line= 3
 2359586.0306492669991.8606290282360050.34853629669568.043352423
2360364.82370485669359.907667749
#Sta/Elev= 30
       0 2879.55    23.2 2873.74    35.4 2872.24    62.5 2876.04    73.3 2875.87
   113.8 2870.61   127.5 2871.66   193.1 2868.54   221.4 2865.28   257.4 2858.55
   294.7 2857.04   395.6 2856.25   430.7 2857.76   468.7 2857.11   482.42854.579
   490.3  2853.2   504.6 2854.23   514.2 2852.01   555.5 2851.97   569.7 2852.22
     577 2854.45   583.8 2856.07   593.2 2855.54   609.2 2856.61   635.6 2855.52
   655.6 2860.21   798.7 2860.95   894.7 2863.31     957 2868.33  1005.8 2875.62
#Mann= 5 ,-1,0
       0      .1       0     420     .08       0     440     .12       0
   482.4    .045       0     577      .1       0
Bank Sta=482.4,577
XS Rating Curve= 0 ,0
Exp/Cntr=0.3,0.1

Type RM Length L Ch R = 1 ,108106  ,274.1,274.1,274.1
XS GIS Cut Line= 4
2359810.40001201670108.8148758642360046.64282314669834.574969239
2360248.19263403669722.2357303812360515.82435013669428.171252193
#Sta/Elev= 30
       0  2909.4    27.2 2900.83    60.6 2893.25    88.5 2885.06   100.3 2879.46
     113    2871   128.6 2862.95   145.6 2857.61   154.2  2856.2   192.7 2856.24
     216 2854.83   242.4 2856.31   273.3 2854.92   344.2 2855.79   427.8 2854.11
     437 2852.33   476.1 2851.51   482.8 2851.53   488.1 2854.14   496.4 2858.05
   510.3  2859.1   531.7  2859.8   578.8 2858.54   601.9 2861.26   624.6 2862.05
   669.9 2861.97   692.5 2859.96   842.3 2862.22   910.6 2869.27   990.3 2882.13
#Mann= 10 ,-1,0
       0      .1       0     290     .08       0  411.96      .1       0
   427.8    .045       0   488.1     .08       0  521.96      .1       0
  632.71     .12       0  762.71      .1       0  792.71     .12       0
  942.71      .1       0
#XS Ineff= 2 , 0
                          612.42         2872.02
Permanent Ineff=
       F       F
Bank Sta=427.8,488.1
XS Rating Curve= 0 ,0
Exp/Cntr(USF)=0,0
Exp/Cntr=0.3,0.1

Type RM Length L Ch R = 1 ,107832  ,211.6,211.6,211.6
XS GIS Cut Line= 3
2360170.94602656670188.4053176532360339.83133225669825.692391144
2360591.10362903669415.129075818
#Sta/Elev= 30
       0 2922.54    60.9 2904.07      83 2894.71    99.7 2889.04   113.9 2882.48
   135.9 2869.67   144.8 2865.55     158 2855.69   166.8 2852.02   175.6 2850.96
   215.4 2851.29   224.2 2853.95   268.3  2855.6   285.9 2855.98   294.8 2854.39
   313.4 2854.48   325.1    2857   343.5  2855.6   370.6 2860.64   387.4 2862.48
   496.7 2859.56   569.3 2862.59   668.4 2860.86   714.9 2861.56   760.9 2865.07
   775.9 2867.19   818.1  2878.3   827.5 2879.46   850.9 2884.97   881.5 2893.56
#Mann= 5 ,-1,0
       0      .1       0     158    .045       0   268.3      .1       0
   670.1     .12       0   790.1      .1       0
#XS Ineff= 2 , 0
                          402.68         2870.95
Permanent Ineff=
       F       F
Bank Sta=158,268.3
XS Rating Curve= 0 ,0
Exp/Cntr=0.3,0.1

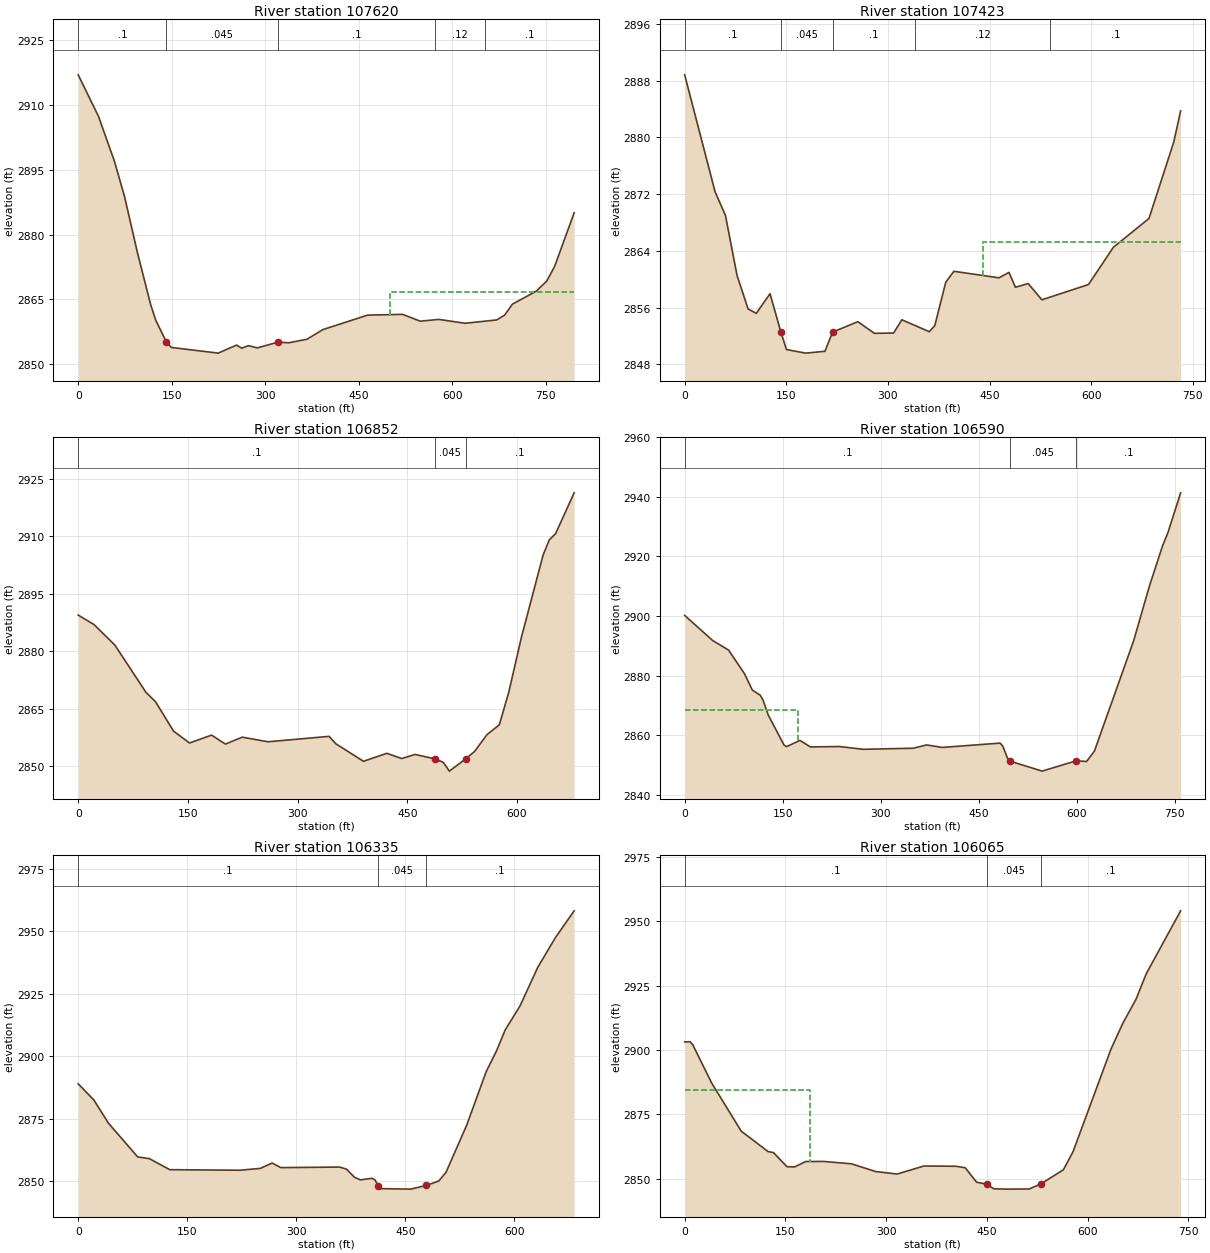
Type RM Length L Ch R = 1 ,107620  ,197.4,197.4,197.4
XS GIS Cut Line= 3
2360406.89719996670220.2521178112360502.75675382669902.079981611
2360651.64499704669463.573511848
#Sta/Elev= 30
       0 2916.96    32.5 2907.36    58.1 2896.97    74.2 2888.85    95.1 2875.76
     116 2863.91   124.4 2860.17   141.5 2855.14   149.4 2853.89   224.6 2852.58
   253.9 2854.44   262.2 2853.73   273.2 2854.31   287.3 2853.79   320.7 2855.13
   337.5 2854.97     367  2855.8   392.4 2858.02   464.2 2861.37   520.2 2861.55
   548.7 2859.97   578.3 2860.38   620.5 2859.49   671.2 2860.26   683.9 2861.38
   696.5 2863.92   734.4 2866.89   751.5 2869.26   764.1 2872.64   795.4 2885.04
#Mann= 5 ,-1,0
       0      .1       0   141.5    .045       0   320.7      .1       0
   572.3     .12       0   652.3      .1       0
#XS Ineff= 2 , 0
                          500.62          2866.8
Permanent Ineff=
       F       F
Bank Sta=141.5,320.7
XS Rating Curve= 0 ,0
Exp/Cntr(USF)=0,0
Exp/Cntr=0.3,0.1

Type RM Length L Ch R = 1 ,107423  ,571.3,571.3,571.3
XS GIS Cut Line= 2
2360627.36327498670229.4959846982360746.34284238669507.103803308
#Sta/Elev= 30
       0  2888.8    44.9 2872.31    60.2 2868.99    77.3 2860.55    93.6 2855.81
   105.7  2855.2     126 2857.96   142.2  2852.5   150.3 2850.09   178.7 2849.59
   207.1 2849.85  218.29 2852.55   255.7 2854.02     280 2852.38   308.4 2852.42
   320.6 2854.29   361.1 2852.61   369.2 2853.46   385.4 2859.58   397.4 2861.12
   463.9  2860.2   478.7 2860.96   488.3 2858.87   507.1 2859.39   527.3  2857.1
   596.2 2859.26   632.7 2864.49   685.4 2868.56   721.9 2879.31   732.1 2883.71
#Mann= 5 ,-1,0
       0      .1       0   142.2    .045       0  218.29      .1       0
     340     .12       0     540      .1       0
#XS Ineff= 2 , 0
                          440.47         2865.25
Permanent Ineff=
       F       F
Bank Sta=142.2,218.29
XS Rating Curve= 0 ,0
Exp/Cntr=0.3,0.1

Type RM Length L Ch R = 1 ,106852  ,261.8,261.8,261.8
XS GIS Cut Line= 3
2360729.78649598670288.6724069892361114.70227807670046.394902966
2361323.99985268669968.247209172
#Sta/Elev= 30
       0 2889.44    21.7 2886.96    50.1 2881.64    92.6 2869.33   105.8 2866.84
   130.4  2859.2   152.2 2856.11   182.4 2858.16   201.3 2855.82   224.3 2857.63
   259.5 2856.43   343.1 2857.84   352.3 2855.91   390.1 2851.34     422 2853.42
   442.4 2852.06   460.7 2853.13   487.7 2851.97   499.1 2851.08   507.6 2848.78
   530.2 2852.03   541.8 2853.86   558.9 2858.26   575.9 2860.87   588.8 2869.35
   606.1 2883.67   635.7 2905.06   644.3 2909.07   652.8 2910.65   678.2  2921.3
#Mann= 3 ,-1,0
       0      .1       0   487.7    .045       0   530.2      .1       0
Bank Sta=487.7,530.2
XS Rating Curve= 0 ,0
Exp/Cntr=0.3,0.1

Type RM Length L Ch R = 1 ,106590  ,255.2,255.2,255.2
XS GIS Cut Line= 3
2360685.57786903670345.7593672882361068.31104965670292.881756809
2361439.73222377670264.924936091
#Sta/Elev= 30
       0  2900.2      43 2891.75    67.2 2888.56    91.5 2880.62   103.6 2875.11
   115.7 2873.38   119.7 2871.88   127.8 2866.78     152 2856.66   156.1 2856.14
   176.3 2858.22   192.4 2856.03     237 2856.16   273.2 2855.23   349.9 2855.59
   370.1  2856.7   394.3 2855.86   482.5 2857.31   486.5 2856.37   494.1  2852.2
   497.9 2851.24     547  2847.9   599.1 2851.38   614.9 2851.13   626.9 2854.62
   687.1 2891.79   711.1 2910.09   731.2  2923.6   739.2 2927.88   758.8 2941.38
#Mann= 3 ,-1,0
       0      .1       0   497.9    .045       0   599.1      .1       0
#XS Ineff= 2 , 0
          174.11 2868.49
Permanent Ineff=
       F       F
Bank Sta=497.9,599.1
XS Rating Curve= 0 ,0
Exp/Cntr(USF)=0,0
Exp/Cntr=0.3,0.1

Type RM Length L Ch R = 1 ,106335  ,270.2,270.2,270.2
XS GIS Cut Line= 3
2360714.77401737670472.6354539292361041.75779806670504.633132175
2361389.39545393670568.830057403
#Sta/Elev= 30
       0 2888.98    21.5 2882.52    41.6 2873.23    81.8 2859.74    97.9 2859.04
     126 2854.63   222.5 2854.41   250.6 2855.15   266.7 2857.29   278.7 2855.45
   359.5 2855.68   368.9 2854.87   379.8 2851.65     388 2850.55   404.2 2851.18
   408.3  2850.5   412.4 2848.25   416.4 2847.04   457.1 2846.85   478.7 2848.31
   495.9 2850.09   505.9 2853.59   534.4  2872.5   561.1 2893.84   575.1 2902.01
   587.3 2910.57   607.6 2920.11     632 2935.55   656.4  2947.5   682.1 2958.19
#Mann= 3 ,-1,0
       0      .1       0   412.4    .045       0   478.7      .1       0
Bank Sta=412.4,478.7
XS Rating Curve= 0 ,0
Exp/Cntr=0.3,0.1

Type RM Length L Ch R = 1 ,106065  ,232.2,232.2,232.2
XS GIS Cut Line= 3
2360508.06178822670663.9097481282360866.55612399670677.126129171
2361215.13817397670827.462463525
#Sta/Elev= 30
       0 2903.16     8.1 2903.24    12.1 2902.03    40.1 2887.22    84.2 2868.46
   124.2 2860.52   132.2 2860.12   152.2 2854.65   163.5 2854.53   180.2 2856.64
   206.6 2856.68   248.3 2855.76   284.3 2852.75   316.3 2851.78   356.2  2854.9
   404.1  2854.8   417.8 2854.21   434.6 2848.61   449.8 2847.82   460.4 2846.03
   481.8 2845.91     513 2845.98   530.2 2847.91   563.9 2853.45   578.3 2860.51
   634.9 2900.49   652.8 2910.63     672 2919.74   687.2 2929.65   738.4 2954.14
#Mann= 3 ,-1,0
       0      .1       0   449.8    .045       0   530.2      .1       0
#XS Ineff= 2 , 0
          186.58 2884.29
Permanent Ineff=
       F       F
Bank Sta=449.8,530.2
XS Rating Curve= 0 ,0
Exp/Cntr(USF)=0,0
Exp/Cntr=0.3,0.1