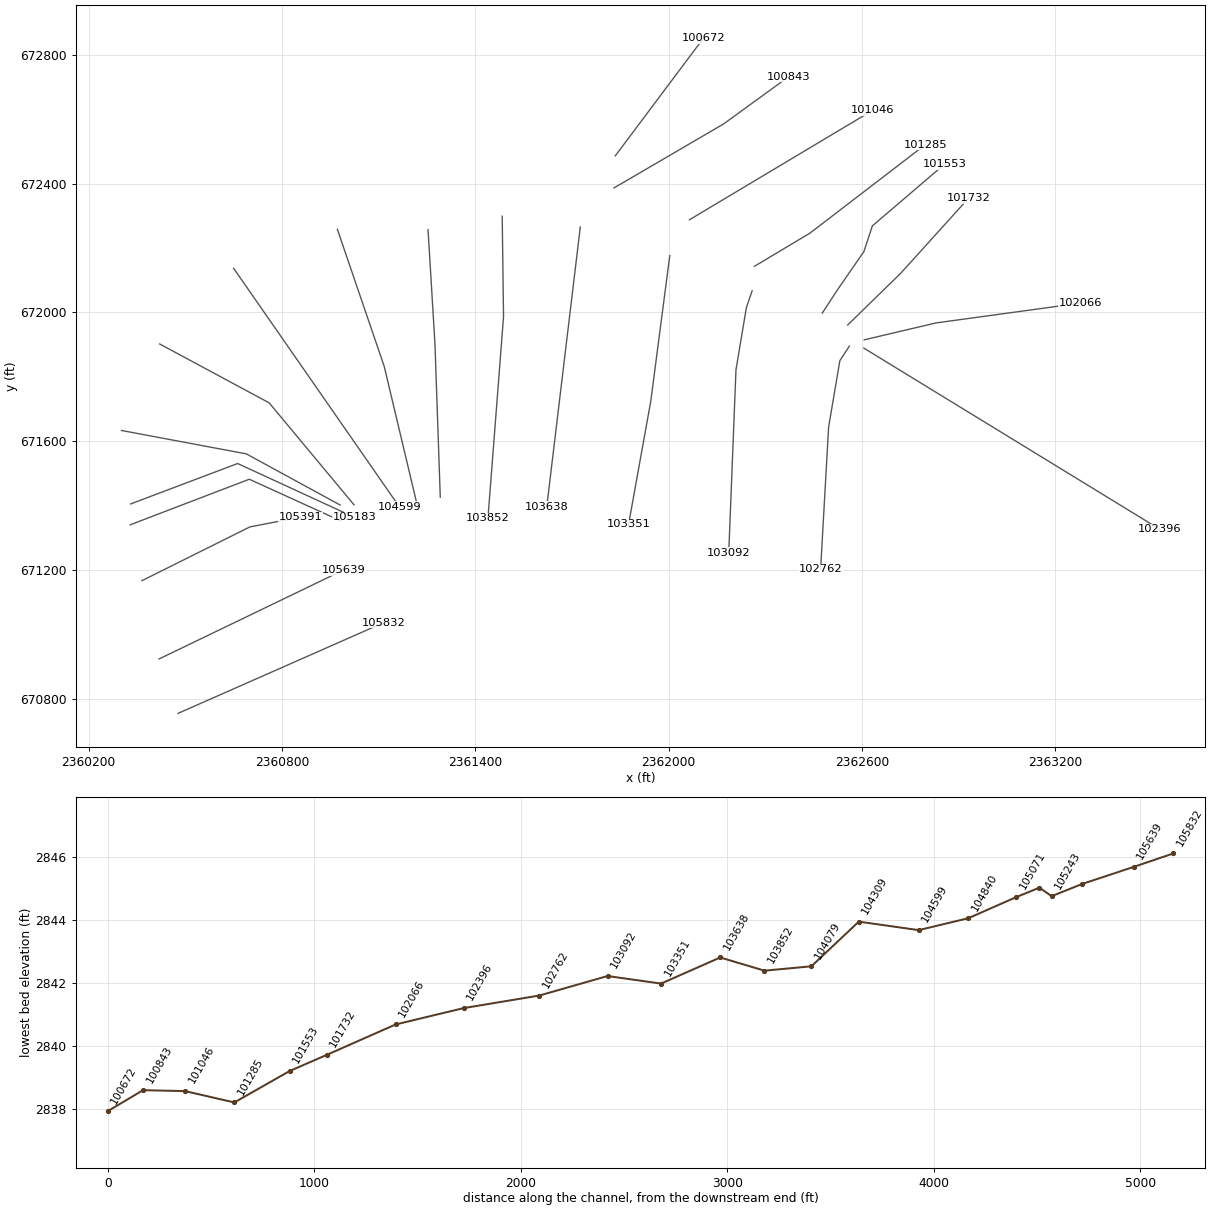
HEC-RAS study LAURELFK.prj: LAURELFK

--- LAURELFK.g01 (geometry) --- (continued)

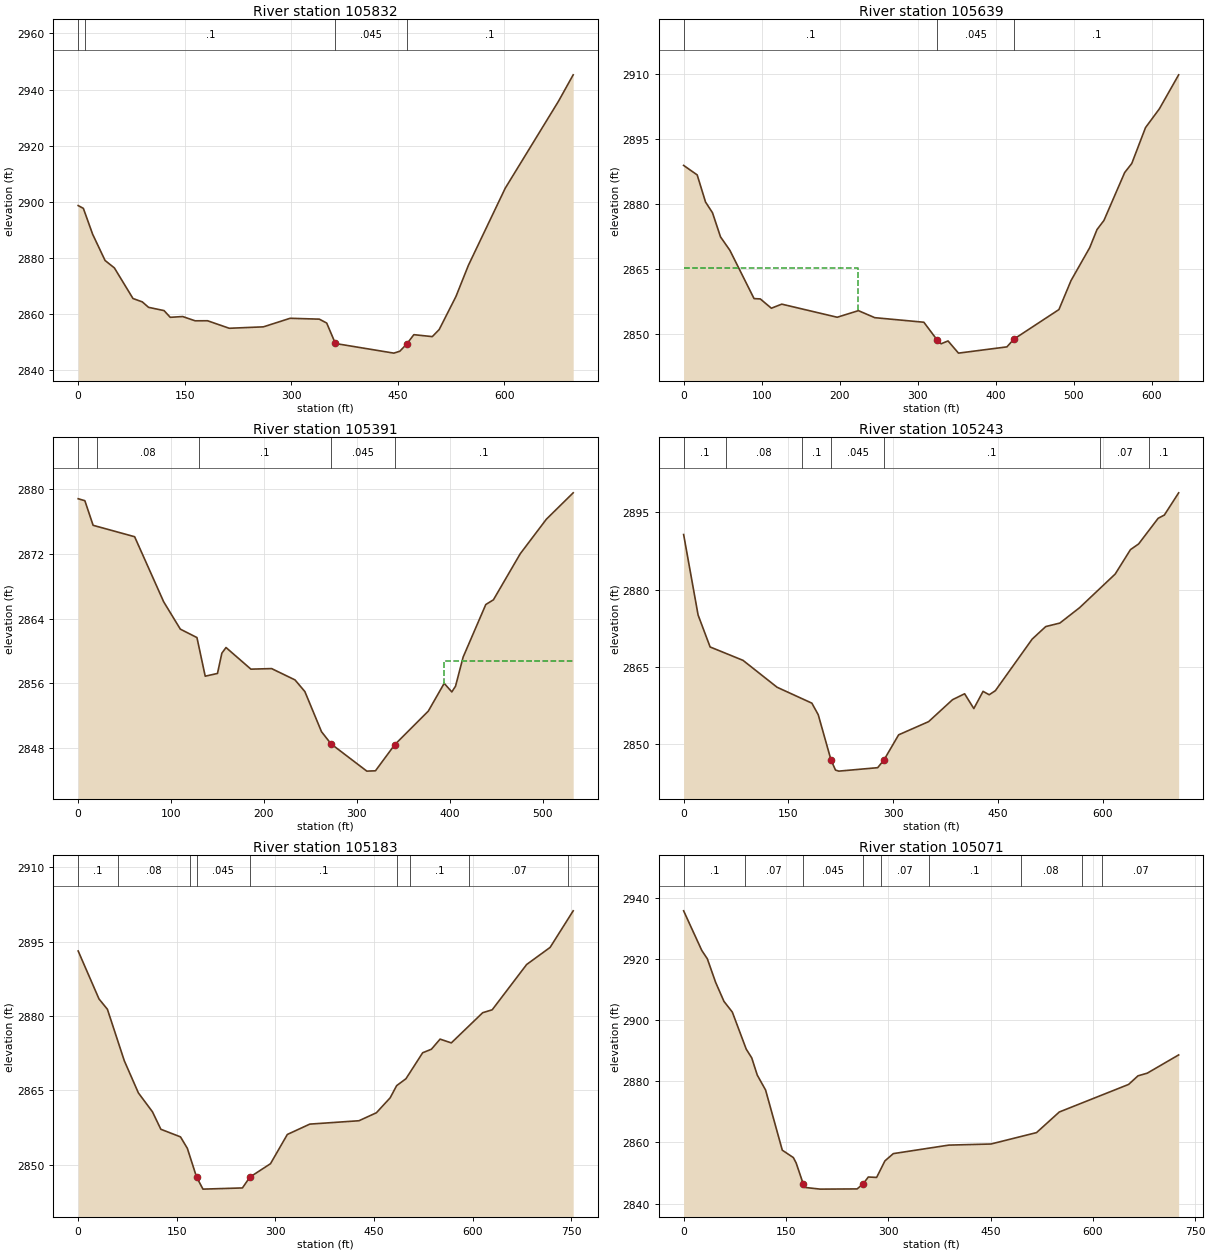
Type RM Length L Ch R = 1 ,105832  ,192.9,192.9,192.9
XS GIS Cut Line= 2
2360477.53508602670754.2272715052361115.20287364671035.806558235
#Sta/Elev= 30
       0 2898.68     7.3 2897.69    20.4 2888.46    37.9 2879.12      51 2876.48
    77.2 2865.58    90.3 2864.38    99.1 2862.44   120.9 2861.28   129.7 2858.88
   147.2 2859.16   164.7 2857.64   182.2 2857.66   212.8 2854.98   260.9 2855.49
   298.5 2858.54   339.6 2858.23     350 2856.84   362.2 2849.56   444.5 2846.13
   452.9 2846.79   462.8 2849.41   472.7  2852.7   498.7 2852.01   508.4 2854.53
     532  2866.3   549.5 2877.38   601.4 2904.86   676.3 2935.79   697.1 2945.24
#Mann= 4 ,-1,0
       0     .08       0      10      .1       0   362.2    .045       0
   462.8      .1       0
Bank Sta=362.2,462.8
XS Rating Curve= 0 ,0
Exp/Cntr=0.3,0.1

Type RM Length L Ch R = 1 ,105639  ,248.4,248.4,248.4
XS GIS Cut Line= 2
2360418.85121618670923.2812260812360990.45969626671199.173180336
#Sta/Elev= 30
       0 2888.96    17.4 2886.77    28.1 2880.52      37 2878.06    47.3 2872.49
    59.2 2869.43    90.3 2858.27    98.3 2858.19   112.5 2856.05   125.8 2856.99
   196.9 2853.97   224.1 2855.49   245.1 2853.87     308 2852.82     325 2848.75
   330.1 2847.85     339 2848.51   352.4  2845.7   414.5 2847.14   423.4 2848.92
   481.2 2855.74   496.7 2862.42   520.7 2870.02     530 2874.17   538.9 2876.28
   565.5 2887.32   574.6 2889.41   592.2 2897.67     610 2902.01   634.7 2909.84
#Mann= 3 ,-1,0
       0      .1       0     325    .045       0   423.4      .1       0
#XS Ineff= 2 , 0
          223.57 2865.41
Permanent Ineff=
       F       F
Bank Sta=325,423.4
XS Rating Curve= 0 ,0
Exp/Cntr(USF)=0,0
Exp/Cntr=0.3,0.1

Type RM Length L Ch R = 1 ,105391  ,148.5,148.5,148.5
XS GIS Cut Line= 3
2360365.74138198671166.4862383872360700.59281019671333.435904739
2360856.57352205671363.567761613
#Sta/Elev= 30
       0 2878.79     7.2 2878.55    16.1 2875.51    60.8  2874.1    92.1 2866.06
     110 2862.69   127.9 2861.65   136.8 2856.88     150 2857.22   154.7 2859.72
   159.2 2860.42     186 2857.75   208.3 2857.82   233.5 2856.42   244.1 2854.98
     262 2850.03   272.3 2848.52   310.8 2845.16   320.1  2845.2   340.9 2848.43
     377 2852.57   394.1    2856   402.3 2854.94   406.3 2855.64   414.5 2859.24
   438.9 2865.73   447.1 2866.31     476    2872   504.1 2876.26     533 2879.52
#Mann= 5 ,-1,0
       0     .07       0      20     .08       0     130      .1       0
   272.3    .045       0   340.9      .1       0
#XS Ineff= 2 , 0
                          393.78         2858.81
Permanent Ineff=
       F       F
Bank Sta=272.3,340.9
XS Rating Curve= 0 ,0
Exp/Cntr=0.3,0.1

Type RM Length L Ch R = 1 ,105243  ,59.2,59.2,59.2
XS GIS Cut Line= 3
2360328.80674707671339.8446887862360698.70132973671481.507912894
2360982.85533932671351.844611788
#Sta/Elev= 30
       0 2890.71    20.7 2875.09    37.9 2868.88      85 2866.28   133.7 2861.06
   183.5 2857.97   192.6 2855.74  210.92 2846.93   217.3 2844.98   222.1 2844.77
   277.7 2845.44   286.72846.939   307.7 2851.82   350.6 2854.38   384.8 2858.64
   402.1 2859.79   415.3 2856.92   428.5 2860.26   437.3  2859.6   446.1 2860.39
   498.8 2870.41   518.2 2872.84   538.4 2873.52   566.5 2876.49   617.6 2883.04
   639.5 2887.79   651.1 2888.88   679.1 2893.87   687.9 2894.49   708.4 2898.81
#Mann= 7 ,-1,0
       0      .1       0      60     .08       0     170      .1       0
  210.92    .045       0   286.7      .1       0  596.09     .07       0
  666.09      .1       0
Bank Sta=210.92,286.7
XS Rating Curve= 0 ,0
Exp/Cntr(USF)=0,0
Exp/Cntr=0.3,0.1

Type RM Length L Ch R = 1 ,105183  ,112.2,112.2,112.2
XS GIS Cut Line= 3
 2360330.5235495671404.7557931182360662.49209664671530.280278707
2361024.11205113671363.497879003
#Sta/Elev= 30
       0  2893.1    31.7 2883.42    44.5 2881.33    70.2 2870.94    91.6 2864.46
     113 2860.65   125.8 2857.12   155.7 2855.58   166.1 2853.27   180.22847.445
   189.9 2845.04   249.9 2845.28   261.3 2847.47   292.6 2850.17   318.2 2856.07
   352.4 2858.16   427.2 2858.84   453.7 2860.45   474.6 2863.46   484.5 2865.92
   498.7 2867.32   524.1 2872.56   537.4 2873.27   550.6 2875.31   567.7 2874.55
   615.4 2880.64   629.9 2881.23   682.3 2890.37     718 2893.82   753.1  2901.2
#Mann= 9 ,-1,0
       0      .1       0      60     .08       0     170      .1       0
   180.2    .045       0   261.3      .1       0  484.91     .08       0
  504.91      .1       0  594.91     .07       0  744.91      .1       0
Bank Sta=180.2,261.3
XS Rating Curve= 0 ,0
Exp/Cntr(USF)=0,0
Exp/Cntr=0.3,0.1

Type RM Length L Ch R = 1 ,105071  ,231.5,231.5,231.5
XS GIS Cut Line= 3
2360301.98920113671632.9353585172360689.31892563671560.311035175
2360980.62315592671401.344460747
#Sta/Elev= 30
       0 2935.73    26.6 2922.79    34.8 2920.03      47  2912.3    59.2 2906.11
    71.4 2902.63    91.8 2890.51    99.9 2887.64     108 2882.02   120.2 2877.13
   144.7 2857.47   160.9 2855.05     165  2853.3  175.29 2846.51   177.2 2845.31
   200.4 2844.74   254.5 2844.81   263.5 2846.55   270.8  2848.7     283 2848.57
   295.2 2853.98   307.5 2856.35   388.8 2859.13   450.7 2859.49   517.5 2863.22
   550.9 2869.96   652.5 2878.97   666.2 2881.77   679.9 2882.66   725.9 2888.62
#Mann= 9 ,-1,0
       0      .1       0      90     .07       0  175.29    .045       0
   263.5     .08       0     290     .07       0     360      .1       0
  494.08     .08       0  584.08      .1       0  614.08     .07       0
Bank Sta=175.29,263.5
XS Rating Curve= 0 ,0
Exp/Cntr(USF)=0,0
Exp/Cntr=0.3,0.1

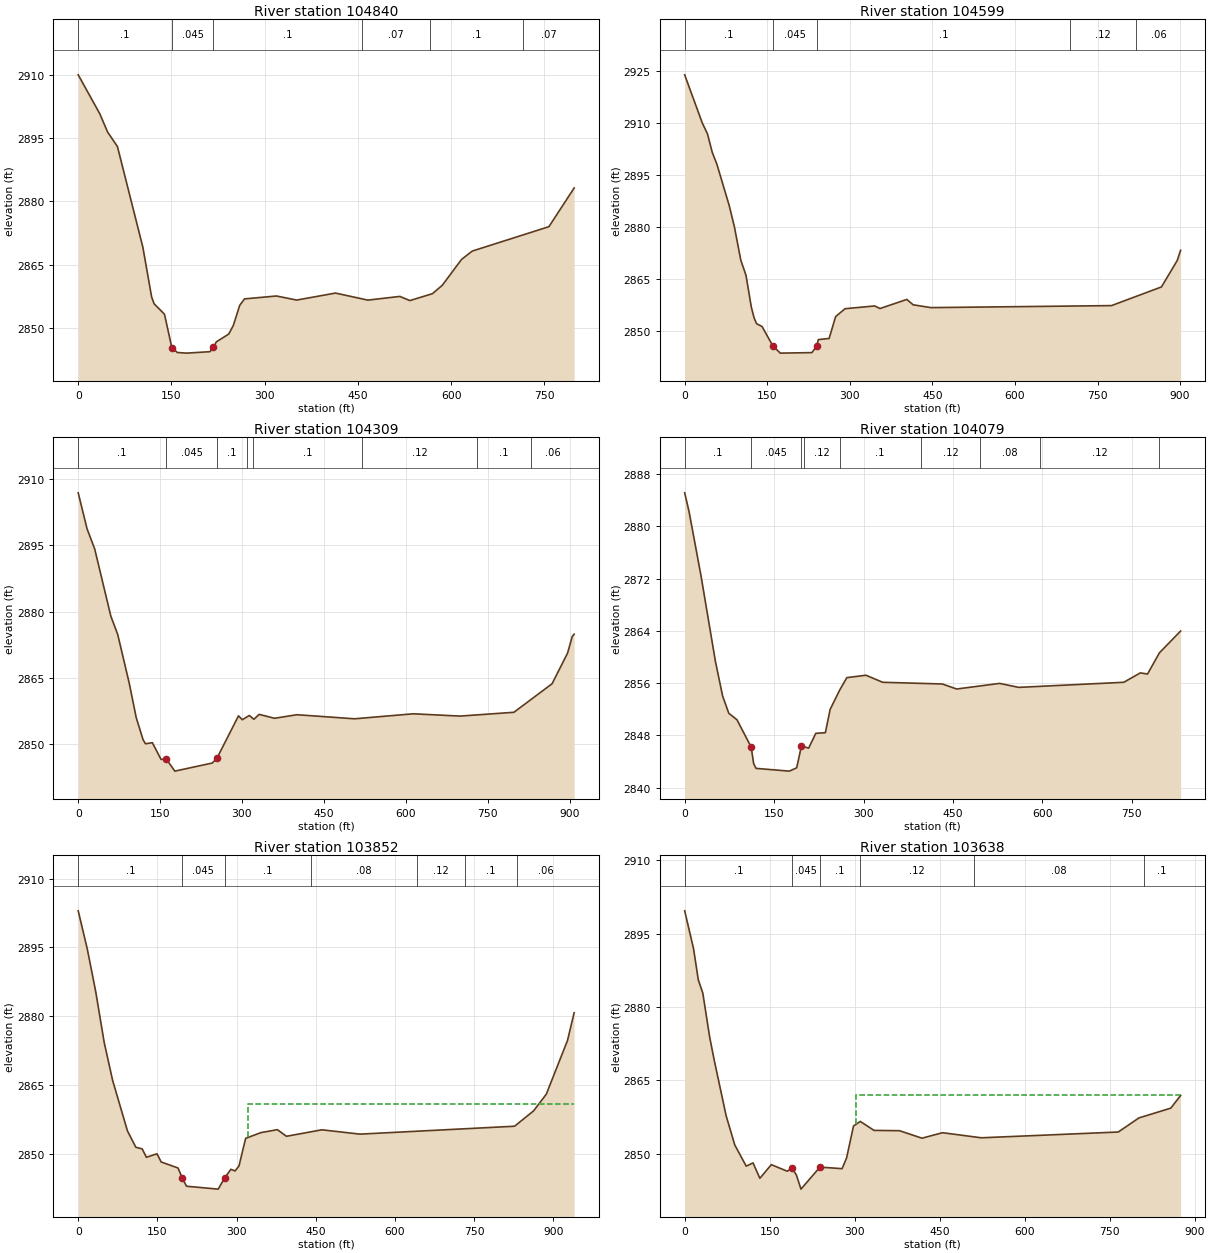
Type RM Length L Ch R = 1 ,104840  ,240.6,240.6,240.6
XS GIS Cut Line= 3
2360420.60367267671901.646184674 2360760.3547726671718.700270833
 2361023.7235279671401.962984815
#Sta/Elev= 30
       0 2910.01    34.7 2900.79    47.3 2896.45    63.1 2893.02     104 2869.17
   118.1 2857.38   122.2 2855.74   138.8 2853.28   150.6 2845.39   159.5 2844.22
   174.3 2844.07   211.9 2844.41   217.6 2845.43   222.1 2846.73   242.2  2848.6
   249.4 2850.59   259.9 2855.42   267.6 2856.92   318.9 2857.61   351.4 2856.64
   413.9  2858.3   465.9 2856.63   517.5 2857.51   533.5 2856.52   569.9 2858.16
   585.7 2860.15   616.7 2866.28   633.9 2868.25   757.2 2874.03   797.8  2883.2
#Mann= 6 ,-1,0
       0      .1       0   150.6    .045       0   217.6      .1       0
  455.88     .07       0  565.88      .1       0  715.88     .07       0
Bank Sta=150.6,217.6
XS Rating Curve= 0 ,0
Exp/Cntr=0.3,0.1

Type RM Length L Ch R = 1 ,104599  ,290.2,290.2,290.2
XS GIS Cut Line= 2
2360649.98865485  672136.69816992361163.77546787671396.580831539
#Sta/Elev= 30
       0 2923.87    31.9 2910.03    41.5 2906.83    50.1 2901.53    58.7 2898.04
      81 2886.16    90.3 2880.11     102 2870.45   111.4 2866.11   121.1 2856.94
     126 2853.91   130.6 2852.17   140.6 2851.36   160.1  2845.8   173.7 2843.69
   231.2 2843.84   239.8 2845.74   242.9 2847.59   262.4 2847.91   274.3 2854.23
   291.4 2856.49   345.1 2857.28   354.9 2856.54   403.6 2859.16   415.1 2857.61
   447.4  2856.8   775.4 2857.38   866.2 2862.76   894.7 2870.34     901 2873.31
#Mann= 5 ,-1,0
       0      .1       0   160.1    .045       0   239.8      .1       0
     700     .12       0     820     .06       0
Bank Sta=160.1,239.8
XS Rating Curve= 0 ,0
Exp/Cntr(USF)=0,0
Exp/Cntr=0.3,0.1

Type RM Length L Ch R = 1 ,104309  ,229.6,229.6,229.6
XS GIS Cut Line= 3
2360971.99141572672257.7367528422361117.39674365671831.785355577
2361223.34899534671385.800522011
#Sta/Elev= 30
       0 2906.82    16.3 2898.65    30.2 2894.15    59.8 2878.95    72.4 2874.82
    93.6 2863.76   106.3 2856.03   118.9 2851.03   123.2 2850.14   135.8 2850.38
   151.8 2846.61   161.2 2846.71     177 2843.96   245.7 2845.79   254.2 2846.89
   293.6 2856.44   300.7 2855.57   313.4 2856.53   321.8 2855.67   331.4 2856.78
   359.6  2855.9   400.8  2856.7   506.2 2855.78     614 2856.91   699.4 2856.39
   798.1 2857.25     868 2863.69   896.4  2870.6     905 2874.37   908.5 2874.88
#Mann= 8 ,-1,0
       0      .1       0   161.2    .045       0   254.2      .1       0
     310     .12       0     320      .1       0  520.09     .12       0
  730.09      .1       0  830.09     .06       0
Bank Sta=161.2,254.2
XS Rating Curve= 0 ,0
Exp/Cntr=0.3,0.1

Type RM Length L Ch R = 1 ,104079  ,227,227,227
XS GIS Cut Line= 3
 2361253.3390609672256.7074320572361274.81568009671901.517191549
 2361291.3361564671425.727474032
#Sta/Elev= 30
       0 2885.11     7.5 2882.17    27.6 2872.31    51.6 2859.31    63.6 2854.05
      74 2851.39    87.7  2850.4   111.6 2846.21   115.7 2843.69   119.7 2842.96
   175.6 2842.54   187.9 2843.05   195.9 2846.41   207.9 2846.05   219.9 2848.32
     236 2848.42     244 2851.98     260 2854.93     272 2856.84   304.1 2857.21
   332.1 2856.13   432.2 2855.87   456.2  2855.1   528.3 2855.96   560.3 2855.35
   736.6 2856.13   764.4 2857.57   776.4 2857.39   796.4 2860.64   831.9 2863.97
#Mann= 9 ,-1,0
       0      .1       0   111.6    .045       0   195.9      .1       0
     200     .12       0     260      .1       0  395.84     .12       0
  495.84     .08       0  595.84     .12       0  795.84     .06       0
Bank Sta=111.6,195.9
XS Rating Curve= 0 ,0
Exp/Cntr(USF)=0,0
Exp/Cntr=0.3,0.1

Type RM Length L Ch R = 1 ,103852  ,214.5,214.5,214.5
XS GIS Cut Line= 3
2361483.49346158672298.3685695362361487.61345008671986.446950893
2361439.27711621671360.616536798
#Sta/Elev= 30
       0 2902.97    17.2 2894.66    33.2 2885.37    49.2 2874.34    65.2 2866.07
    93.2  2855.1   109.2 2851.51   121.2 2851.16   129.2 2849.33   149.2 2850.09
   157.2 2848.31   189.2 2846.99   197.2 2844.79   205.2 2843.03   265.2  2842.4
   277.2 2844.77   289.2 2846.71   297.2 2846.36   304.6 2847.44   317.2 2853.45
   346.1  2854.7   377.4 2855.34   394.5  2853.9   461.6 2855.31   533.9 2854.37
   826.7 2856.09   862.9 2859.45   886.9 2863.08     927 2874.75   939.6 2880.79
#Mann= 7 ,-1,0
       0      .1       0   197.2    .045       0   277.2      .1       0
  441.95     .08       0  641.95     .12       0  731.95      .1       0
  831.95     .06       0
#XS Ineff= 2 , 0
                          321.65         2860.93
Permanent Ineff=
       F       F
Bank Sta=197.2,277.2
XS Rating Curve= 0 ,0
Exp/Cntr=0.3,0.1

Type RM Length L Ch R = 1 ,103638  ,286.2,286.2,286.2
XS GIS Cut Line= 2
2361725.82468316672264.9676702082361621.74568245671395.990616687
#Sta/Elev= 30
       0 2899.64    15.7  2891.9      24 2885.57      32 2882.84    44.1 2873.87
    52.2 2869.11    73.2 2857.79    88.4 2851.84   108.6 2847.51   120.6 2848.18
   132.7 2845.03   152.9 2847.82   181.1 2846.47   189.1 2847.14   197.2  2845.7
   205.2 2842.82   238.7 2847.31   277.8    2847   285.8 2849.22   297.9  2855.7
     310 2856.64   334.2 2854.81   379.1 2854.75   418.8 2853.22     455 2854.34
   523.5  2853.3   765.2 2854.48   801.5 2857.35   857.9 2859.36   875.2 2861.94
#Mann= 6 ,-1,0
       0      .1       0   189.1    .045       0   238.7      .1       0
     310     .12       0     510     .08       0     810      .1       0
#XS Ineff= 2 , 0
                          302.01         2862.02
Permanent Ineff=
       F       F
Bank Sta=189.1,238.7
XS Rating Curve= 0 ,0
Exp/Cntr(USF)=0,0
Exp/Cntr=0.3,0.1

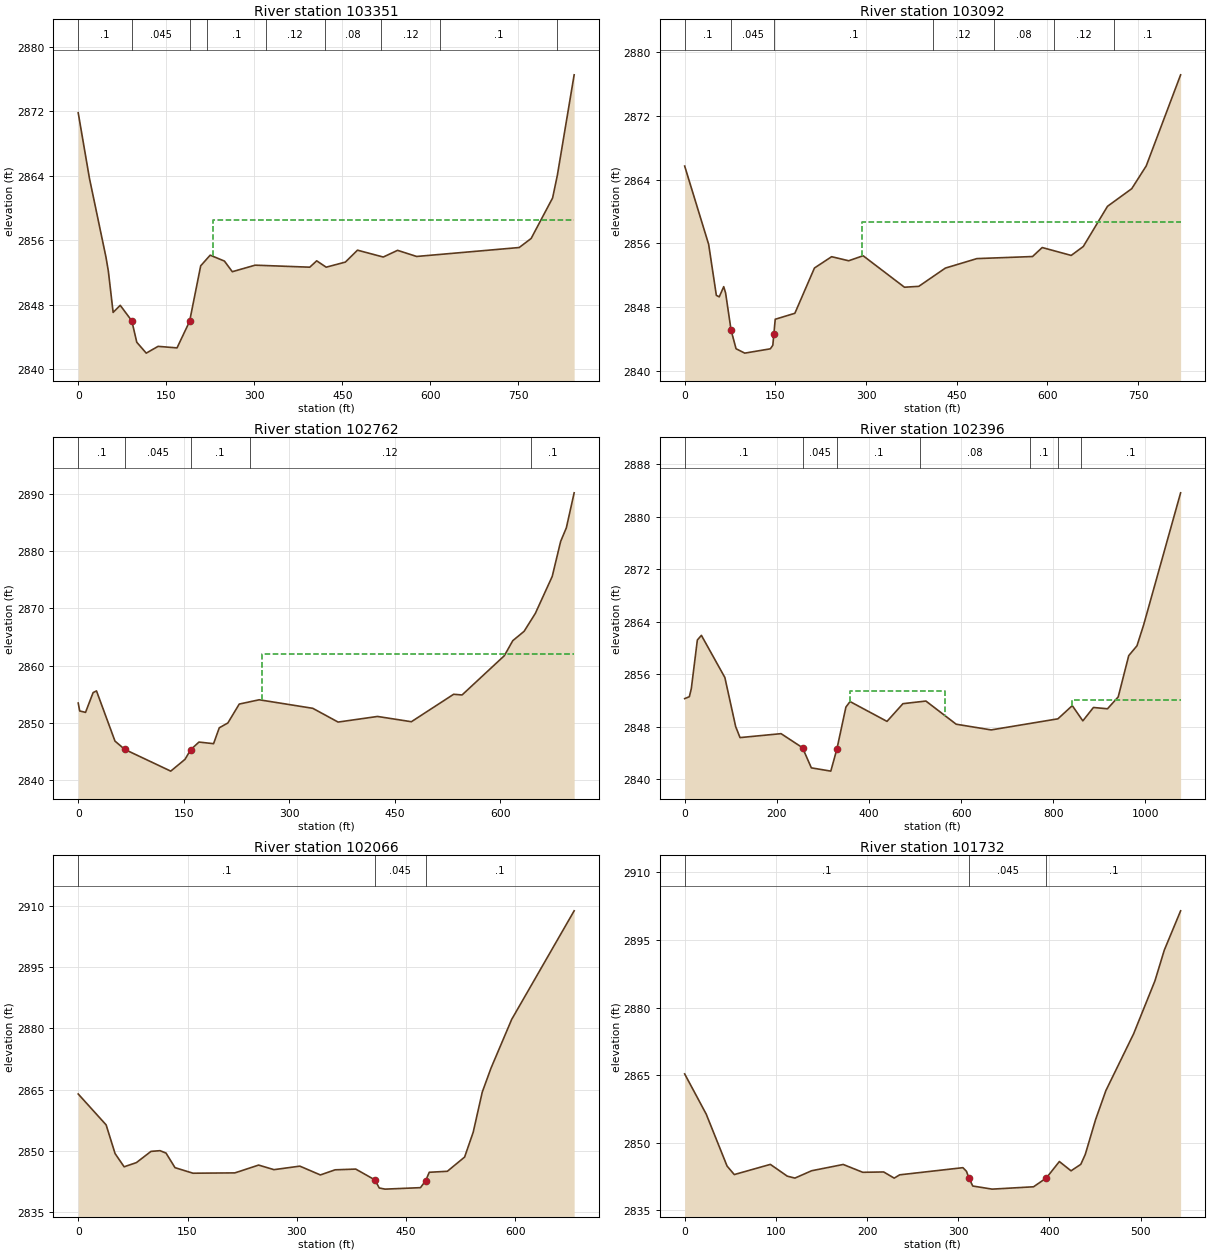
Type RM Length L Ch R = 1 ,103351  ,259.3,259.3,259.3
XS GIS Cut Line= 3
2362003.51591653672176.1425482942361944.52383746 671723.89408568
2361875.60350081671341.016466964
#Sta/Elev= 30
       0  2871.8    19.1 2863.69    47.4 2853.86    51.4 2852.14    59.5 2847.04
    71.6 2847.92    91.3    2846    99.8 2843.34   115.9 2841.99   136.1 2842.83
   168.4 2842.64   189.8 2845.93   208.7 2852.82   224.9 2854.14   249.1 2853.41
   262.6 2852.09   301.5  2852.9   394.6 2852.65   406.4 2853.44   422.5 2852.65
   455.2 2853.28   475.9 2854.76   519.8 2853.91   544.2 2854.74   576.7 2853.98
   751.5 2855.09   771.8 2856.21   808.4 2861.24   816.5 2864.06   845.1 2876.51
#Mann= 9 ,-1,0
       0      .1       0    91.3    .045       0   189.8     .12       0
     220      .1       0     320     .12       0     420     .08       0
  516.08     .12       0  616.08      .1       0  816.08     .06       0
#XS Ineff= 2 , 0
                          230.07         2858.54
Permanent Ineff=
       F       F
Bank Sta=91.3,189.8
XS Rating Curve= 0 ,0
Exp/Cntr=0.3,0.1

Type RM Length L Ch R = 1 ,103092  ,330,330,330
XS GIS Cut Line= 4
2362259.04259949672066.733742797 2362241.2508876672014.665630345
2362208.90148127671821.3670794192362186.46626654671252.328451217
#Sta/Elev= 30
       0  2865.7    39.7 2855.87    52.4 2849.48    57.2 2849.29    64.6 2850.57
    67.7 2849.78    76.8  2845.1      85 2842.78    99.4 2842.23   141.7 2842.77
   145.8 2843.21   147.62844.674   149.8 2846.48   182.3 2847.23   214.7 2852.91
   243.1 2854.33   271.3 2853.82   295.2 2854.45   363.6  2850.5   387.3 2850.61
   431.3  2852.9   483.4 2854.09   575.5 2854.35   591.5 2855.48   639.5 2854.49
   659.5 2855.61   699.5 2860.65   739.6 2862.86   763.6 2865.72   820.5 2877.15
#Mann= 7 ,-1,0
       0      .1       0    76.8    .045       0   147.6      .1       0
  411.01     .12       0  511.01     .08       0  611.01     .12       0
  711.01      .1       0
#XS Ineff= 2 , 0
                          293.95         2858.74
Permanent Ineff=
       F       F
Bank Sta=76.8,147.6
XS Rating Curve= 0 ,0
Exp/Cntr(USF)=0,0
Exp/Cntr=0.3,0.1

Type RM Length L Ch R = 1 ,102762  ,366.6,366.6,366.6
XS GIS Cut Line= 4
2362560.82628925671894.9207214172362531.29767583671849.800608985
2362496.40156778671643.4388291942362471.53261518 671202.01492043
#Sta/Elev= 30
       0 2853.49     2.1 2852.11    10.4 2851.86    21.2 2855.31      26 2855.61
    52.3 2846.85    66.22845.402   131.6 2841.61   151.9 2843.67     160 2845.35
   171.7 2846.68   192.5  2846.4   200.6 2849.17   212.8 2850.01     229 2853.31
   257.4 2854.06   333.6 2852.57   369.6 2850.17   425.7 2851.15   473.8 2850.23
   533.9 2855.02   545.9  2854.9     606 2861.75     618 2864.37   634.1    2866
   650.1 2869.13   674.1 2875.58   686.1 2881.69   694.2 2884.06   705.3 2890.17
#Mann= 5 ,-1,0
       0      .1       0    66.2    .045       0     160      .1       0
  243.92     .12       0  643.22      .1       0
#XS Ineff= 2 , 0
                          261.74         2862.02
Permanent Ineff=
       F       F
Bank Sta=66.2,160
XS Rating Curve= 0 ,0
Exp/Cntr(USF)=0,0
Exp/Cntr=0.3,0.1

Type RM Length L Ch R = 1 ,102396  ,329.3,329.3,329.3
XS GIS Cut Line= 2
 2362605.8065169671888.6836574532363523.54610012671326.297738017
#Sta/Elev= 30
       0 2852.26    10.1 2852.55    14.4 2853.78    27.5 2861.19    36.3  2861.9
    87.2 2855.48   110.7 2847.99   120.1 2846.32   209.2 2846.92   255.72844.779
   274.9 2841.71   317.1 2841.21   330.42844.592   349.9 2850.97   358.9 2851.81
   439.1 2848.79   473.7 2851.49   523.5 2851.89   589.2 2848.36   665.1 2847.49
     810 2849.18   841.2 2851.19   864.1 2848.87   887.1 2850.91   917.6 2850.71
   940.9 2852.52   963.7 2858.81   981.6 2860.31   996.2 2863.53  1076.3 2883.62
#Mann= 7 ,-1,0
       0      .1       0   255.7    .045       0   330.4      .1       0
     510     .08       0     750      .1       0     810     .08       0
     860      .1       0
#XS Ineff= 2 ,-1
  358.85  565.592853.406  840.47 1216.96 2852.06
Permanent Ineff=
       F       F
Bank Sta=255.7,330.4
XS Rating Curve= 0 ,0
Exp/Cntr(USF)=0,0
Exp/Cntr=0.3,0.1

Type RM Length L Ch R = 1 ,102066  ,334.4,334.4,334.4
XS GIS Cut Line= 3
2362606.90228294671914.455189324 2362829.7023224671966.984129538
2363277.10725468672028.316254426
#Sta/Elev= 30
       0 2863.95    38.3  2856.4    50.6 2849.38      63 2846.15    79.8 2847.17
    99.9 2849.92   112.3 2850.09   120.5  2849.5   132.8 2845.94   157.5 2844.58
     215 2844.66   247.6 2846.57   268.6 2845.45   304.1 2846.31   332.3 2844.16
   352.5 2845.41   380.8 2845.59     407 2842.96   413.1 2840.97   421.1 2840.69
   469.6 2841.05   476.6 2842.71   481.7 2844.81   506.5 2845.05   530.2 2848.53
     542 2854.61   554.4 2864.41   566.5 2870.31   594.8 2882.19   680.5 2908.73
#Mann= 3 ,-1,0
       0      .1       0     407    .045       0   476.6      .1       0
Bank Sta=407,476.6
XS Rating Curve= 0 ,0
Exp/Cntr(USF)=0,0
Exp/Cntr=0.3,0.1

Type RM Length L Ch R = 1 ,101732  ,178.5,178.5,178.5
XS GIS Cut Line= 3
2362555.69202011671960.7123695892362719.97590629672121.041055243
2362930.73095377672354.457935787
#Sta/Elev= 30
       0 2865.28    23.6 2856.37    46.5 2844.84    54.4 2842.95      94 2845.21
   112.5  2842.6   120.9 2842.17   139.3  2843.8   173.9 2845.19   195.4 2843.45
   218.3 2843.53   229.8 2842.16   235.8 2842.89   305.2 2844.48   309.1 2843.67
   311.9 2842.13     316 2840.41   337.3 2839.72   382.7 2840.24   396.72842.194
     411 2845.84   423.8 2843.78   434.5 2845.22   439.4 2847.41   450.7 2855.12
     462 2861.57   492.5  2874.2   515.8 2885.91   526.1 2892.74     544 2901.46
#Mann= 3 ,-1,0
       0      .1       0   311.9    .045       0   396.7      .1       0
Bank Sta=311.9,396.7
XS Rating Curve= 0 ,0
Exp/Cntr(USF)=0,0
Exp/Cntr=0.3,0.1

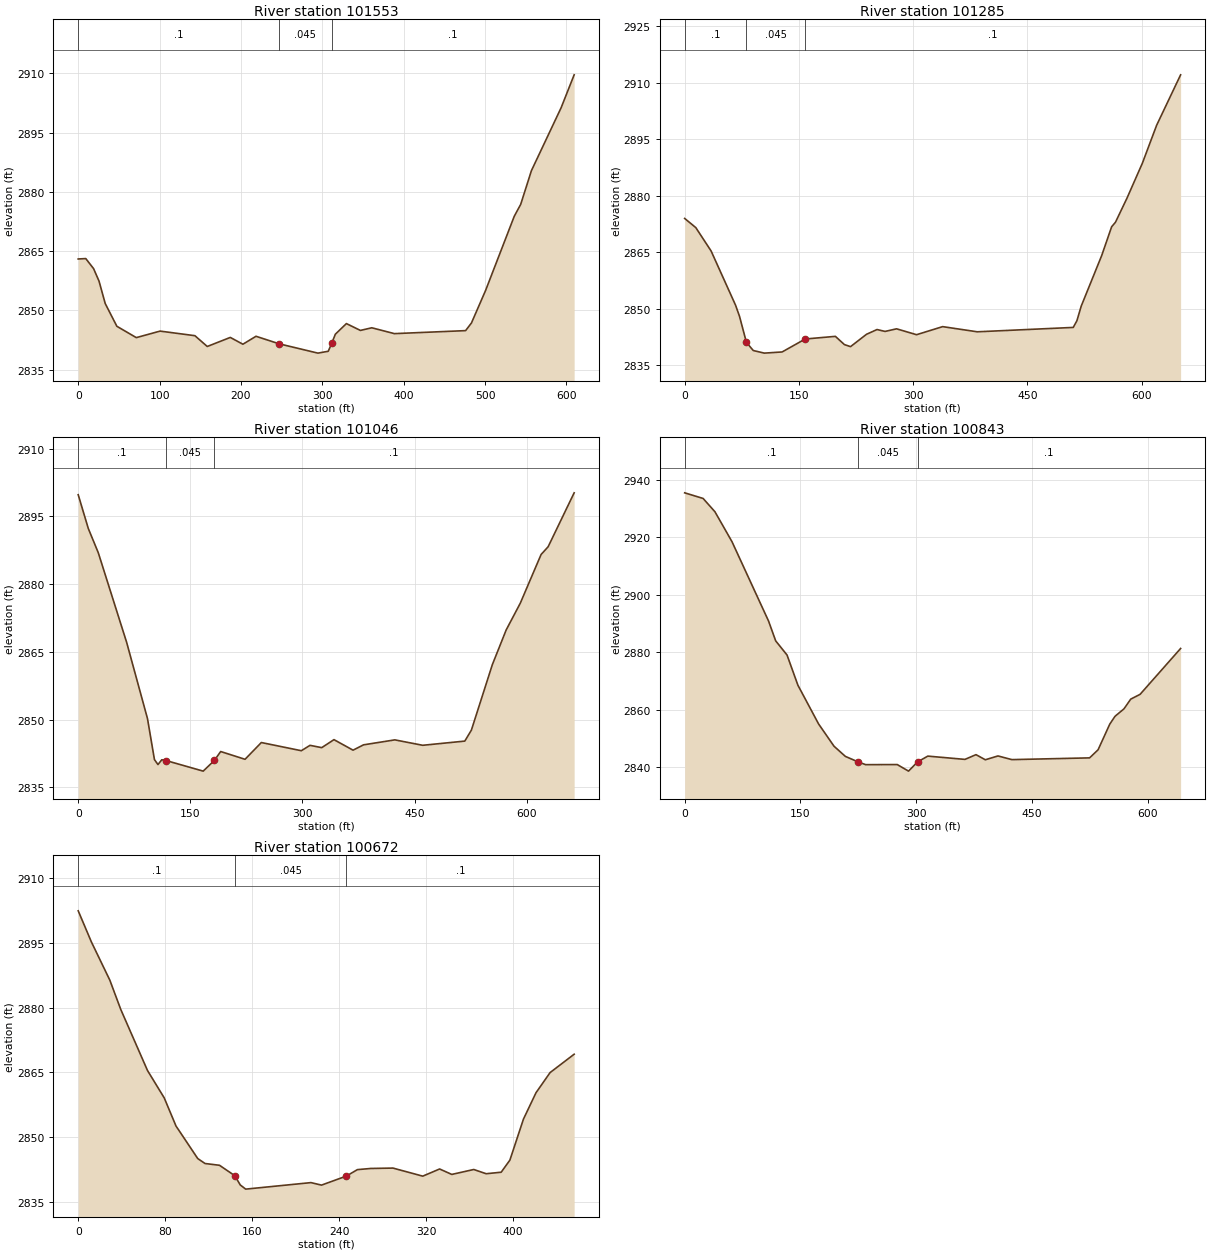
Type RM Length L Ch R = 1 ,101553  ,268.2,268.2,268.2
XS GIS Cut Line= 5
2362476.58730991671997.3751150252362525.49707042672072.225600433
2362605.85569341672188.5877049352362632.19466875  672268.4825968
2362856.07595914672459.879150939
#Sta/Elev= 30
       0 2863.02     9.3 2863.12    18.9 2860.58    25.6 2857.41    33.2 2851.75
    47.5    2846    71.4 2843.13   100.6 2844.78   143.4 2843.62   158.6 2840.89
   186.9 2843.18   202.4 2841.46   218.5 2843.47     247 2841.56   294.6 2839.21
   307.3 2839.68   311.5 2841.65     316 2843.99   329.6 2846.68   346.8 2844.95
   360.8 2845.62   388.6 2844.14   476.1  2844.9   483.3 2846.84   500.7 2855.08
   535.9 2873.82   543.8 2876.83     557 2885.36   593.5 2901.27   609.5 2909.59
#Mann= 3 ,-1,0
       0      .1       0     247    .045       0   311.5      .1       0
Bank Sta=247,311.5
XS Rating Curve= 0 ,0
Exp/Cntr(USF)=0,0
Exp/Cntr=0.3,0.1

Type RM Length L Ch R = 1 ,101285  ,239,239,239
XS GIS Cut Line= 3
2362266.39940838672142.8859127222362439.01455765672246.251075871
2362796.05400115 672520.37152293
#Sta/Elev= 30
       0 2873.95    14.6 2871.52    34.7 2865.32    66.8 2850.94      72 2847.99
    81.12841.047    90.1  2838.9   104.6 2838.21     128 2838.52   158.32841.958
   197.9 2842.66   209.8 2840.47   217.8 2839.93   238.8 2843.21   252.6 2844.47
   263.2 2843.97   278.3 2844.66   304.5  2843.1   338.8 2845.24   384.2 2843.87
   510.3 2845.03   515.1 2846.81   520.8  2850.7   547.6 2864.07   560.7 2871.73
   565.8 2872.96   580.9 2879.35   601.1 2888.62   619.8 2898.67   651.3 2912.06
#Mann= 3 ,-1,0
       0      .1       0    81.1    .045       0   158.3      .1       0
Bank Sta=81.1,158.3
XS Rating Curve= 0 ,0
Exp/Cntr(USF)=0,0
Exp/Cntr=0.3,0.1

Type RM Length L Ch R = 1 ,101046  ,203,203,203
XS GIS Cut Line= 2
2362064.58723024672287.4398943482362634.04804839672627.926910944
#Sta/Elev= 30
       0 2899.77    13.5 2892.29    26.8 2886.95    64.8 2867.08    92.7 2850.19
     102 2841.12   106.7 2840.03   111.8 2841.08   117.6 2840.91   167.2 2838.57
   182.12840.926   190.6 2842.91   223.2 2841.19     245  2844.9   298.5 2843.09
   310.1 2844.28   325.8 2843.77   342.2 2845.54   367.7 2843.21   381.7 2844.39
   423.6 2845.49   460.9 2844.29   517.2 2845.22     526 2847.64   554.1 2862.17
   572.6 2869.84   591.4 2875.74   619.3 2886.54   628.7 2888.25   663.5 2900.19
#Mann= 3 ,-1,0
       0      .1       0   117.6    .045       0   182.1      .1       0
Bank Sta=117.6,182.1
XS Rating Curve= 0 ,0
Exp/Cntr(USF)=0,0
Exp/Cntr=0.3,0.1

Type RM Length L Ch R = 1 ,100843  ,171.5,171.5,171.5
XS GIS Cut Line= 3
2361830.35493453672386.2690403482362170.48952956672584.986172037
     2362371.505      672731.168
#Sta/Elev= 30
       0 2935.37    23.9 2933.41    39.2 2928.79    61.3 2918.38   108.7 2890.77
   117.9  2883.9   132.6 2878.98   146.7 2868.47   173.5    2855   193.5 2847.25
   208.2 2843.72   224.5 2841.83   234.5 2840.85   275.4 2840.88     290  2838.6
   301.7 2841.81     315 2843.82   363.1 2842.68   377.4 2844.33   389.5 2842.55
   405.9 2843.88   423.9  2842.6   524.6 2843.21   535.6 2846.03   550.7 2854.93
   557.5 2857.66   569.1 2860.25   577.9 2863.64     590  2865.3   642.5 2881.25
#Mann= 3 ,-1,0
       0      .1       0   224.5    .045       0   301.7      .1       0
Bank Sta=224.5,301.7
XS Rating Curve= 0 ,0
Exp/Cntr=0.3,0.1

Type RM Length L Ch R = 1 ,100672  ,301.7,301.7,301.7
XS GIS Cut Line= 2
2361834.31997994672485.8859411632362107.64088897672850.925629454
#Sta/Elev= 30
       0 2902.46    12.2  2895.2    29.1 2886.37    39.1 2879.61    63.7 2865.44
    79.1 2859.08    89.9 2852.57   109.9 2845.02   116.6 2843.87   129.9 2843.46
     144 2841.04     149  2838.9     154 2837.93     214 2839.44   223.7 2838.86
   246.6 2840.96   256.7 2842.45     269 2842.72   289.4 2842.81   316.8 2840.94
   332.3  2842.6   343.5 2841.34   363.7 2842.48   375.1  2841.5   388.9 2841.85
   396.9 2844.65   409.4 2854.17   420.9 2860.27   433.9 2864.96     456 2869.21
#Mann= 3 ,-1,0
       0      .1       0     144    .045       0   246.6      .1       0
Bank Sta=144,246.6
XS Rating Curve= 0 ,0
Exp/Cntr(USF)=0,0
Exp/Cntr=0.3,0.1