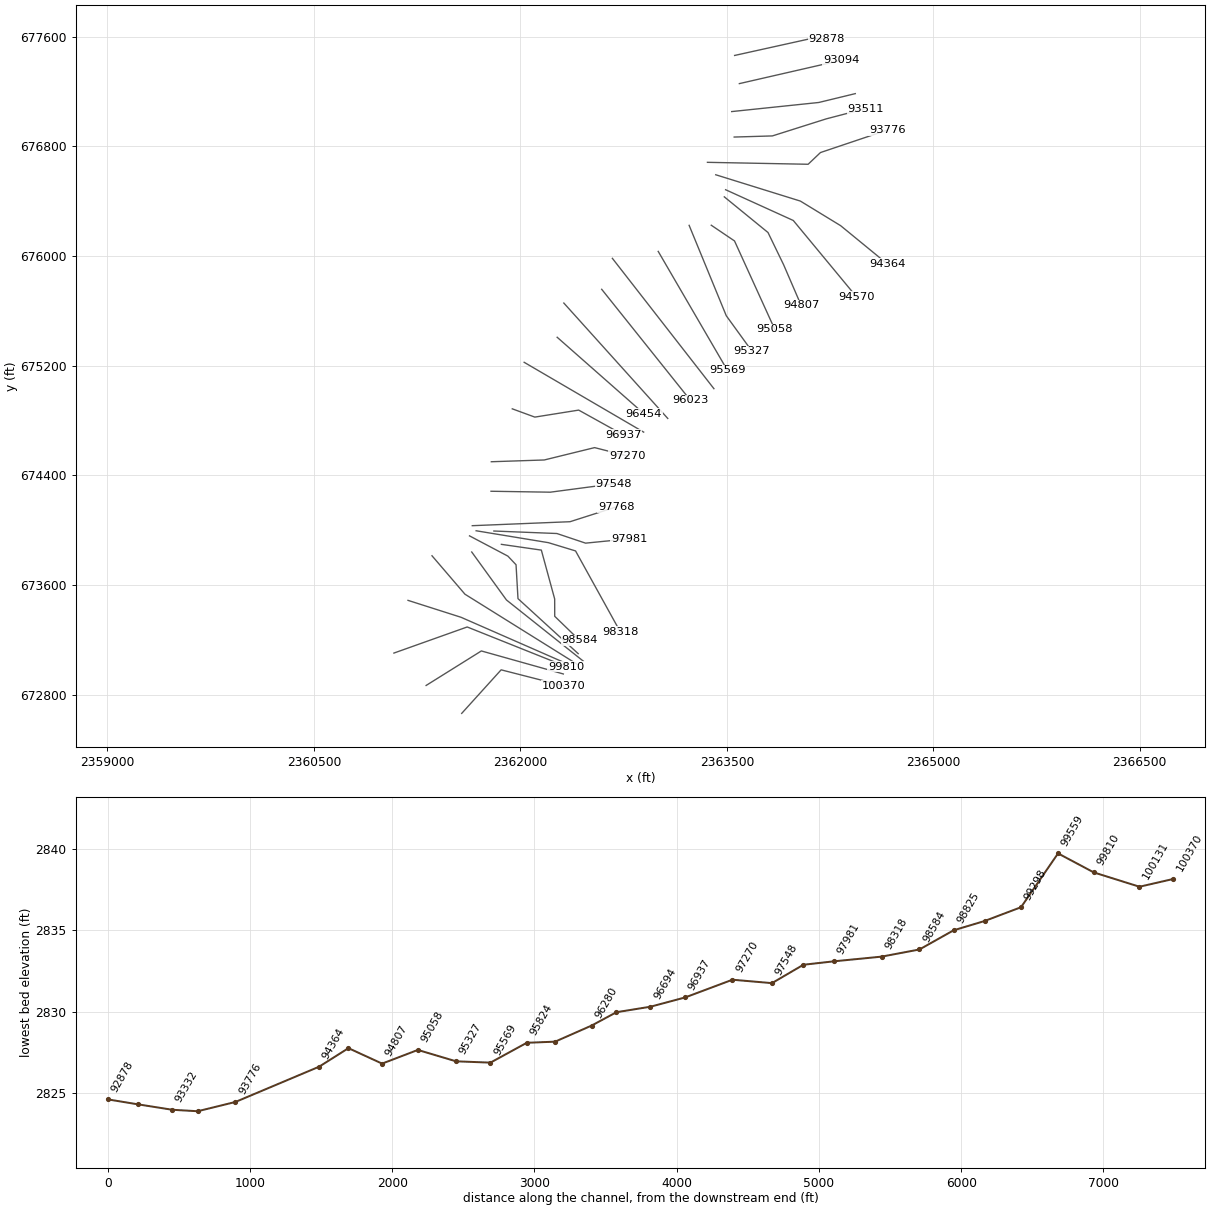
HEC-RAS study LAURELFK.prj: LAURELFK

--- LAURELFK.g01 (geometry) --- (continued)

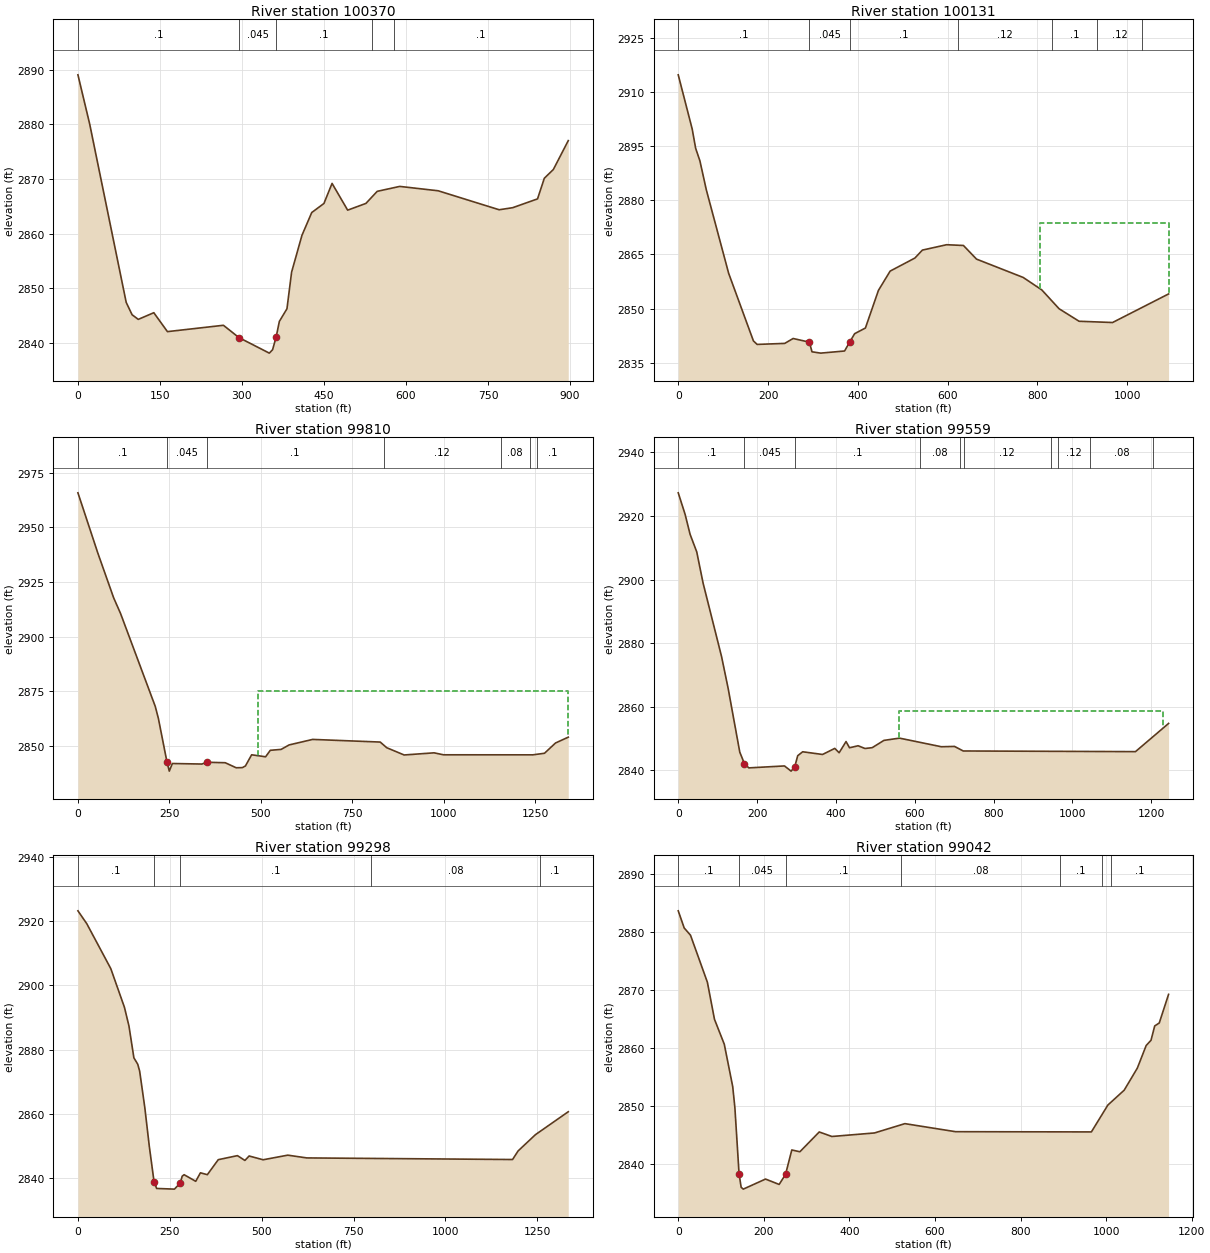
Type RM Length L Ch R = 1 ,100370  ,238.8,238.8,238.8
XS GIS Cut Line= 3
2361573.77572121672663.6027273852361860.19731982672981.170638828
2362314.57168637672864.425355749
#Sta/Elev= 30
       0 2889.05    21.5 2880.05    88.3 2847.44    99.1 2845.18   110.4 2844.34
   138.8 2845.56   163.7  2842.1   266.1 2843.26   294.5 2841.01     350 2838.17
     356 2838.79   362.5  2841.1   368.4 2843.97   382.3 2846.28   390.8 2852.98
   409.7  2859.7   427.6 2863.87   449.9 2865.53   464.8  2869.2   493.3 2864.31
   526.7 2865.54   547.4 2867.75   588.6 2868.65   658.9 2867.85   770.4 2864.38
   795.2 2864.76   840.6 2866.37     853 2870.14   869.5 2871.74   896.8 2877.02
#Mann= 5 ,-1,0
       0      .1       0   294.5    .045       0   362.5      .1       0
  537.65     .12       0  577.65      .1       0
Bank Sta=294.5,362.5
XS Rating Curve= 0 ,0
Exp/Cntr=0.3,0.1

Type RM Length L Ch R = 1 ,100131  ,321,321,321
XS GIS Cut Line= 3
2361315.26443239672867.2421692272361716.52759022 673118.92446725
2362312.06409259672951.014900314
#Sta/Elev= 30
       0 2914.71    31.1 2899.71    38.8 2894.38    48.3 2890.89    62.5 2882.91
   112.3 2859.79   167.5 2841.07   175.8  2840.1   237.2 2840.38     256 2841.74
   292.2 2840.72     298 2838.06   317.4 2837.69   370.6 2838.28   382.2  2840.8
     393 2843.07     417 2844.64     446 2855.05   472.1 2860.39   527.3 2864.01
   543.9  2866.2     598 2867.69   635.4 2867.48   664.5 2863.71   768.4 2858.64
   809.9 2855.19   848.6 2849.96     893 2846.51   967.6 2846.16  1092.4 2854.07
#Mann= 7 ,-1,0
       0      .1       0   292.2    .045       0   382.2      .1       0
  623.66     .12       0  833.66      .1       0  933.66     .12       0
 1033.66      .1       0
#XS Ineff= 2 , 0
                          805.88         2873.64
Permanent Ineff=
       F       F
Bank Sta=292.2,382.2
XS Rating Curve= 0 ,0
Exp/Cntr(USF)=0,0
Exp/Cntr=0.3,0.1

Type RM Length L Ch R = 1 ,99810   ,251.4,251.4,251.4
XS GIS Cut Line= 3
2361081.09716956 673103.371996182361613.59155137673293.756712102
2362332.56310052673005.113957631
#Sta/Elev= 30
       0 2965.73    54.2 2938.29    97.7 2917.73   116.5  2910.6   211.4 2868.13
   219.9 2862.66  243.57  2842.6   249.7 2838.57   258.1 2842.05   338.9 2841.81
   351.6 2842.62   402.6 2842.41   432.5 2840.11   449.3 2840.17   457.8 2840.92
   474.8 2846.03     513 2845.12   525.8 2848.08   555.5  2848.5   577.2 2850.54
   641.6 2853.06   826.3 2851.85   844.1 2849.27   891.6 2845.95   973.5 2846.93
   999.3 2846.03  1243.5 2846.01  1275.3 2846.73  1305.4 2851.42  1340.3 2854.09
#Mann= 7 ,-1,0
       0      .1       0  243.57    .045       0   351.6      .1       0
  835.51     .12       0 1155.51     .08       0 1235.51     .12       0
 1255.51      .1       0
#XS Ineff= 2 , 0
                          493.05         2875.28
Permanent Ineff=
       F       F
Bank Sta=243.57,351.6
XS Rating Curve= 0 ,0
Exp/Cntr=0.3,0.1

Type RM Length L Ch R = 1 ,99559   ,260.2,260.2,260.2
XS GIS Cut Line= 3
2361183.53138224673487.803828705 2361568.7825443673364.422737587
 2362337.0835584673026.466743069
#Sta/Elev= 30
       0 2927.29    17.5 2920.49    30.1 2914.23    46.9 2908.73      63 2898.92
   109.9 2875.78   126.7 2865.72   156.1 2845.72     168 2842.06   179.1 2840.76
   269.5 2841.37   286.3 2839.74   295.42841.057   303.1 2844.59   315.7 2845.83
   366.1 2844.98   397.1 2846.89   408.2 2845.53   425.7 2849.04   434.5 2847.09
   456.3 2847.72   473.8 2846.86   492.1 2847.12   521.8 2849.41   561.3 2850.12
   667.5 2847.41   700.9 2847.51   722.9 2846.08  1159.9 2845.87  1243.9 2854.74
#Mann= 10 ,-1,0
       0      .1       0     168    .045       0   295.4      .1       0
  614.53     .08       0  714.53      .1       0  724.53     .12       0
  944.53     .08       0  964.53     .12       0 1044.53     .08       0
 1204.53      .1       0
#XS Ineff= 1 ,-1
  559.06 1230.87  2858.6
Permanent Ineff=
       F
Bank Sta=168,295.4
XS Rating Curve= 0 ,0
Exp/Cntr(USF)=0,0
Exp/Cntr=0.3,0.1

Type RM Length L Ch R = 1 ,99298   ,256.7,256.7,256.7
XS GIS Cut Line= 3
2361357.95042391673812.9383508592361597.37563586673532.712165469
2362415.94425844673019.924337578
#Sta/Elev= 30
       0 2923.29    24.1 2919.27    89.4 2905.26   126.6 2893.17   138.9 2887.33
   152.3 2877.41   162.8 2875.41     168 2873.25     182 2861.89   194.3 2849.74
   207.12838.789   214.2 2836.64   262.7 2836.43   278.5 2838.34   283.8 2840.48
     289 2840.93   320.6 2838.87   333.4 2841.52   352.2 2840.94   381.9 2845.62
   434.1 2846.88   454.4 2845.39     466 2846.77     504 2845.59   571.1 2847.03
   622.8 2846.17  1182.9 2845.67  1197.9 2848.34  1245.1 2853.42  1334.5 2860.58
#Mann= 5 ,-1,0
       0      .1       0   207.1    .045       0   278.5      .1       0
  798.58     .08       0 1258.58      .1       0
Bank Sta=207.1,278.5
XS Rating Curve= 0 ,0
Exp/Cntr=0.3,0.1

Type RM Length L Ch R = 1 ,99042   ,217.3,217.3,217.3
XS GIS Cut Line= 3
2361646.61788333673840.4436057982361898.81462493673490.660478662
2362457.20672396673044.607618493
#Sta/Elev= 30
       0 2883.69    13.9 2880.73    28.7 2879.47    68.1 2871.35    84.7 2864.94
   107.6 2860.63   127.3 2853.32   132.4 2849.65   142.1 2838.28     147  2835.9
     152 2835.58     204 2837.32   235.8 2836.39   250.72838.112   265.4 2842.35
   284.3 2842.04   329.5 2845.46   359.1 2844.68   458.6 2845.29   529.7  2846.9
     648 2845.51   965.5 2845.47    1004 2850.11  1042.2 2852.69  1072.9  2856.5
  1093.5  2860.4  1104.9 2861.32  1113.5 2863.79  1124.1  2864.3  1145.9 2869.25
#Mann= 7 ,-1,0
       0      .1       0   142.1    .045       0   250.7      .1       0
  521.22     .08       0  891.22      .1       0  991.22     .08       0
 1011.22      .1       0
Bank Sta=142.1,250.7
XS Rating Curve= 0 ,0
Exp/Cntr(USF)=0,0
Exp/Cntr=0.3,0.1

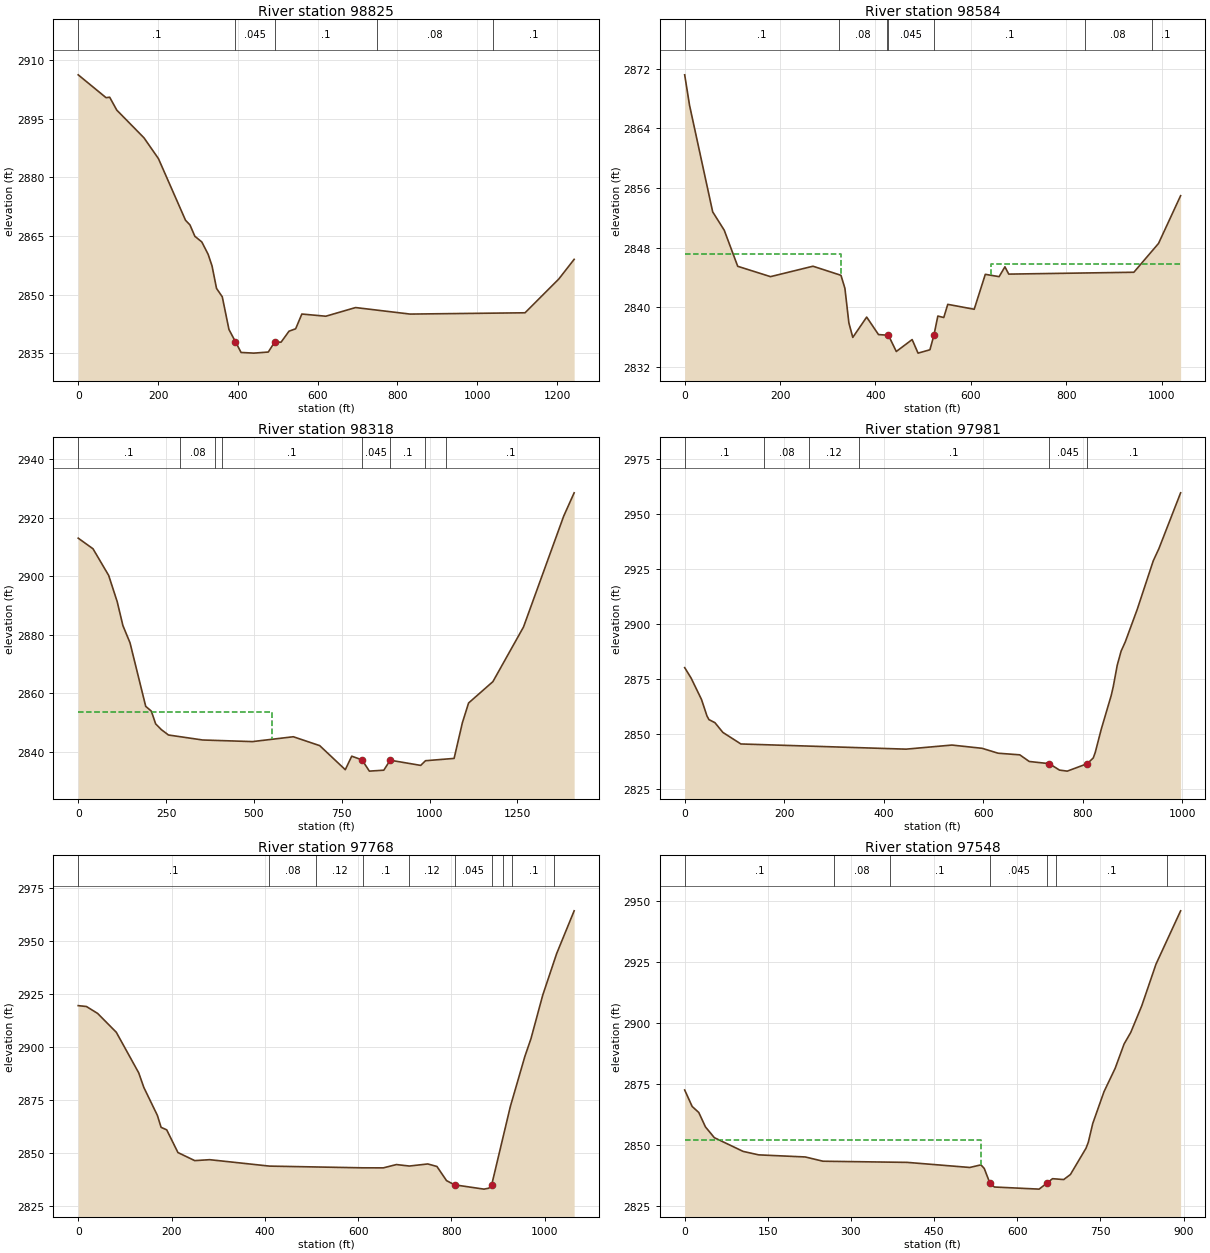
Type RM Length L Ch R = 1 ,98825   ,240.2,240.2,240.2
XS GIS Cut Line= 5
2361630.48987179673958.1482613062361909.35366616673810.317204517
2361968.50011129673747.5265733822361982.66461082673500.377949333
2362420.06285124673099.110472336
#Sta/Elev= 30
       0 2906.28    69.8 2900.43    78.9 2900.54    96.6 2897.25   164.9 2890.14
   201.1 2884.82     269 2869.03   280.1 2867.84   292.4 2864.93   309.8 2863.48
   325.6 2860.33   335.4 2857.35   346.7 2851.58   361.1 2849.43   377.8 2841.07
   394.1 2837.93   408.2 2835.18   440.3 2835.01   476.4 2835.29   492.52837.858
   508.4 2837.81   528.4 2840.63     545 2841.24   560.5 2845.02   620.6 2844.46
   695.2 2846.68   831.7 2845.01  1119.9 2845.34  1204.5 2853.99    1243 2859.03
#Mann= 5 ,-1,0
       0      .1       0   394.1    .045       0   492.5      .1       0
  749.44     .08       0 1039.44      .1       0
Bank Sta=394.1,492.5
XS Rating Curve= 0 ,0
Exp/Cntr=0.3,0.1

Type RM Length L Ch R = 1 ,98584   ,266.1,266.1,266.1
XS GIS Cut Line= 5
2361862.08857166673896.2964591792362152.32505296673854.289367645
2362249.16484825673497.9153330292362249.50468799673371.577113179
2362429.34240303673196.947177149
#Sta/Elev= 30
       0  2871.2    10.2 2867.11    58.7  2852.8    82.9 2850.34   111.2 2845.49
   179.9  2844.1   268.9  2845.5   327.6 2844.28   335.9 2842.53   344.2 2837.89
   352.4 2835.94   381.5 2838.67   406.3 2836.32   427.1 2836.23   443.6 2834.05
   476.8 2835.65   489.2 2833.83   514.1 2834.28   522.4 2836.22   530.7 2838.81
   543.1 2838.61   551.5 2840.38   606.9 2839.72   630.2 2844.41   659.1  2844.1
   671.3 2845.42   679.3 2844.44   941.6 2844.69   993.3 2848.56  1039.6 2854.97
#Mann= 7 ,-1,0
       0      .1       0  323.26     .08       0  423.26      .1       0
   427.1    .045       0   522.4      .1       0   838.9     .08       0
   978.9      .1       0
#XS Ineff= 2 , 0
          327.34 2847.14  642.66         2845.74
Permanent Ineff=
       F       F
Bank Sta=427.1,522.4
XS Rating Curve= 0 ,0
Exp/Cntr(USF)=0,0
Exp/Cntr=0.3,0.1

Type RM Length L Ch R = 1 ,98318   ,337,337,337
XS GIS Cut Line= 4
2361678.68222421673995.3254096952362203.95749598673908.518481121
2362400.82344517673848.3742766042362725.76555321673258.671649202
#Sta/Elev= 30
       0 2913.08    42.1 2909.45    86.7 2900.34     111 2891.34   127.2 2883.19
   147.5 2877.27   192.1 2855.56   208.1 2853.92   220.4 2849.56   236.7 2847.58
   256.9 2845.75   354.2 2844.04   496.1 2843.49   612.3 2845.15   687.4 2842.11
   760.2 2833.88   778.5  2838.5   807.8 2837.24   828.7 2833.39   869.8 2833.71
     888 2837.13   974.8 2835.35   988.5 2836.95  1069.9 2837.74  1093.5 2849.96
  1111.1 2856.69  1180.3    2864  1267.4 2882.68    1382 2920.67  1411.6 2928.59
#Mann= 8 ,-1,0
       0      .1       0     290     .08       0     390     .12       0
     410      .1       0   807.8    .045       0     888      .1       0
  988.25     .08       0 1048.25      .1       0
#XS Ineff= 2 , 0
          552.63 2853.62
Permanent Ineff=
       F       F
Bank Sta=807.8,888
XS Rating Curve= 0 ,0
Exp/Cntr=0.3,0.1

Type RM Length L Ch R = 1 ,97981   ,212.8,212.8,212.8
XS GIS Cut Line= 4
 2361807.4074056673993.4622711852362265.17643347673975.332804735
2362473.66529764673905.0811222412362790.93096052673936.807688529
#Sta/Elev= 30
       0 2880.19    12.8  2875.5    33.9 2865.67    44.8 2858.21    48.8 2856.54
    60.8 2855.15    76.8 2850.71     113 2845.46   445.1  2843.1   537.3 2844.96
     598 2843.48   630.1 2841.25   673.7 2840.51   692.7 2837.49   732.9  2836.5
   753.6 2833.56   769.1  2833.1   809.3 2836.48   821.4  2839.1   825.4 2841.63
   837.4 2852.13   857.5 2867.53   861.6 2871.57   869.6 2881.31   877.4 2887.73
   885.7 2891.88   909.8 2906.72     942 2928.79   953.3 2934.31     997 2959.73
#Mann= 6 ,-1,0
       0      .1       0     160     .08       0     250     .12       0
     350      .1       0   732.9    .045       0   809.3      .1       0
Bank Sta=732.9,809.3
XS Rating Curve= 0 ,0
Exp/Cntr(USF)=0,0
Exp/Cntr=0.3,0.1

Type RM Length L Ch R = 1 ,97768   ,220.7,220.7,220.7
XS GIS Cut Line= 3
2361650.58612562674032.4039203122362360.90694688674061.423198672
2362696.35733758674169.070165469
#Sta/Elev= 30
       0 2919.46    17.6 2919.05    41.6 2915.79    81.7 2906.88   129.7 2887.76
   140.7 2880.86   169.7 2867.69   177.7 2862.04   189.7 2860.87   213.8 2850.15
   249.8 2846.34   281.8 2846.78     410 2843.75     610 2842.94   654.1 2842.92
   682.2 2844.48     710 2843.78   749.4 2844.77     769 2843.58   789.6  2836.9
   806.8 2834.92   869.8 2832.89   880.3 2833.33   886.6 2835.06   926.4 2871.87
   957.6 2895.54   970.6 2903.86   995.8 2924.37  1025.6 2943.97  1063.2 2964.19
#Mann= 10 ,-1,0
       0      .1       0     410     .08       0     510     .12       0
     610      .1       0     710     .12       0   806.8    .045       0
   886.6      .1       0  910.91     .12       0  930.91      .1       0
 1020.91     .12       0
Bank Sta=806.8,886.6
XS Rating Curve= 0 ,0
Exp/Cntr=0.3,0.1

Type RM Length L Ch R = 1 ,97548   ,277.8,277.8,277.8
XS GIS Cut Line= 3
2361786.66669913674283.5202637022362217.24152732674276.721713783
2362677.27673849674337.908663052
#Sta/Elev= 30
       0  2872.5    13.5 2865.73    25.5 2863.24    37.5 2857.32    53.5 2852.91
   105.5 2847.26   133.5 2845.84   217.5 2844.98   249.5 2843.23   401.7 2842.75
   514.3 2840.66   534.5 2841.73   540.5 2840.24   550.6 2834.24   558.7 2832.63
   639.4 2831.76   654.5  2834.4   663.6 2836.05   683.8 2835.69   695.9 2837.77
   724.1  2848.6   728.2 2851.05   736.2 2858.74   756.4 2871.76   776.6 2881.41
   792.7  2891.4   804.8 2896.19   824.5 2907.04   850.3 2924.23   894.7 2946.13
#Mann= 7 ,-1,0
       0      .1       0     270     .08       0     370      .1       0
   550.6    .045       0   654.5     .12       0  670.63      .1       0
  870.63     .06       0
#XS Ineff= 2 , 0
          534.77 2852.01
Permanent Ineff=
       F       F
Bank Sta=550.6,654.5
XS Rating Curve= 0 ,0
Exp/Cntr(USF)=0,0
Exp/Cntr=0.3,0.1

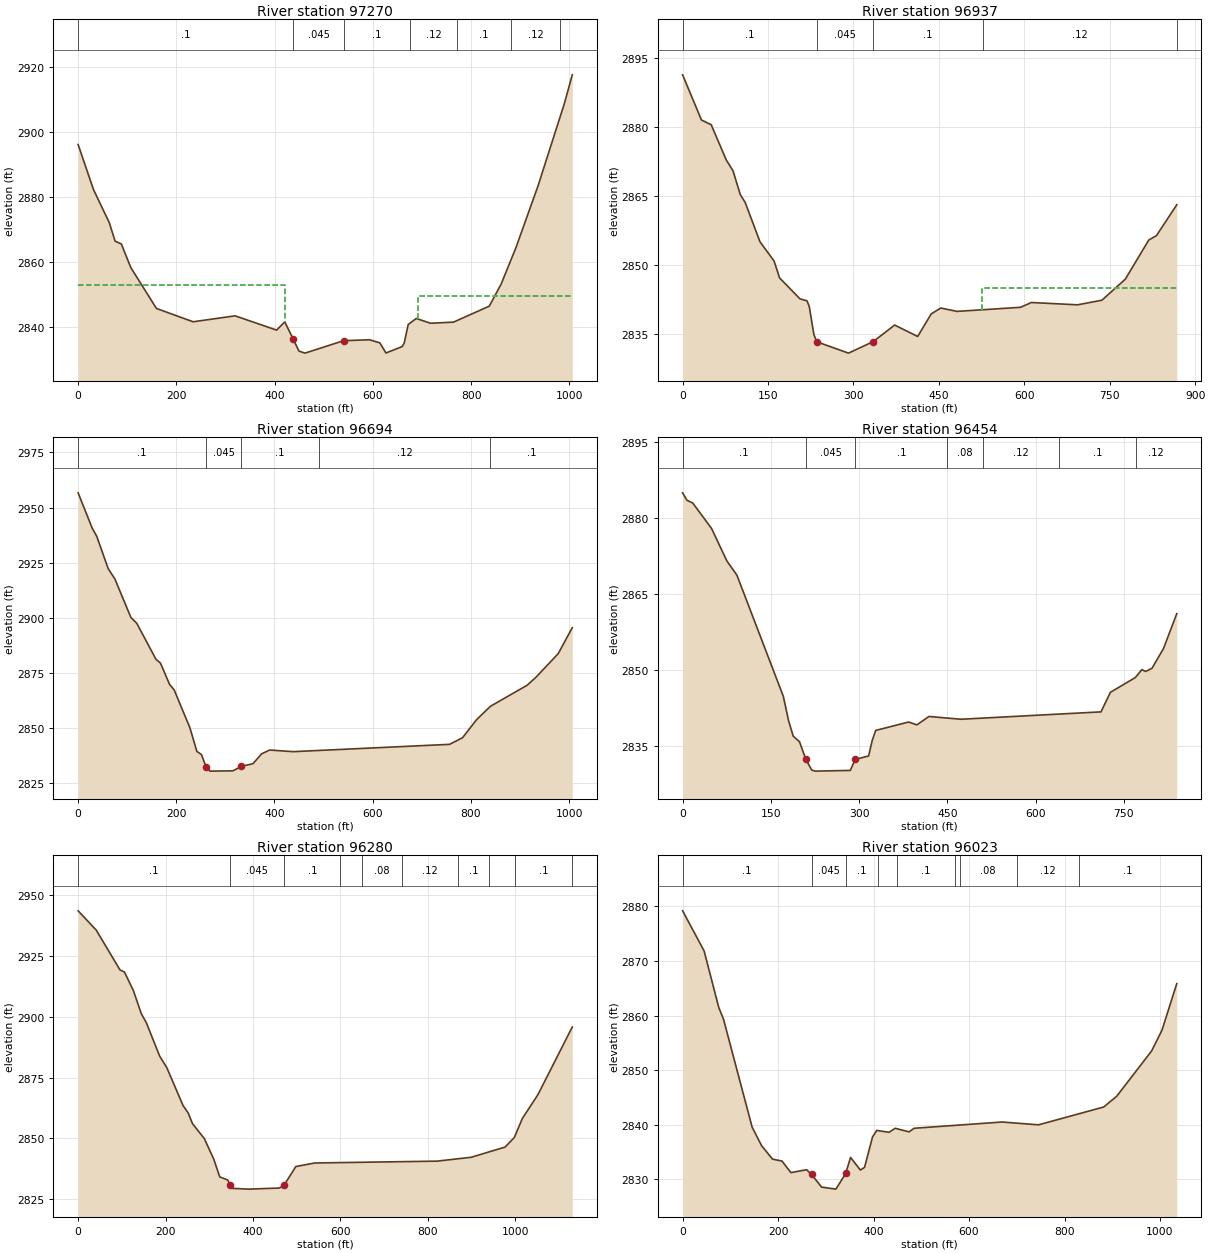
Type RM Length L Ch R = 1 ,97270   ,332.5,332.5,332.5
XS GIS Cut Line= 4
2361788.90335242674498.7641467642362173.58887178674511.663944354
2362539.17716102674601.7777616932362775.86741745 674541.34620686
#Sta/Elev= 30
       0 2896.19    31.3  2882.3    63.3 2872.18    75.3 2866.43    87.9 2865.59
   107.3 2858.29   159.4 2845.72     234 2841.62   319.5 2843.45     404 2839.05
   420.5  2841.6   438.12836.171   449.4  2832.6   461.7 2831.97   540.3  2835.8
   593.2 2836.08   614.1 2835.13   626.5 2832.01   659.5 2833.99   663.6 2835.02
   671.8 2840.79   688.3 2842.64   717.1 2841.17   763.9 2841.51   836.8 2846.43
   860.9 2853.22   890.4 2864.17   935.9  2883.4   989.7 2908.83  1005.7 2917.64
#Mann= 7 ,-1,0
       0      .1       0   438.1    .045       0   540.3      .1       0
   674.9     .12       0  771.43      .1       0  881.43     .12       0
  981.43      .1       0
#XS Ineff= 2 , 0
          420.58 2853.04  691.92         2849.65
Permanent Ineff=
       F       F
Bank Sta=438.1,540.3
XS Rating Curve= 0 ,0
Exp/Cntr=0.3,0.1

Type RM Length L Ch R = 1 ,96937   ,243.7,243.7,243.7
XS GIS Cut Line= 4
2361941.10788396674884.649247214 2362104.9711207674824.319634438
2362423.66712187674875.3732720742362747.19221357674695.099154409
#Sta/Elev= 30
       0 2891.36    33.1 2881.54    50.2 2880.52    76.7 2872.84    88.5 2870.52
   101.3 2865.32   109.8 2863.65   135.9 2855.07   160.6  2850.9   170.2 2847.24
   206.1 2842.67   218.4 2842.25   222.4 2841.01   230.5 2834.93  235.44 2833.35
   291.3 2830.88   334.72833.383   372.3 2836.98   412.8  2834.5   436.5  2839.4
   453.3 2840.68   481.9 2839.95   593.5 2840.84   612.4 2841.88   693.4 2841.38
   736.1 2842.37   777.3 2846.94   818.5 2855.45   832.2 2856.44   867.7 2863.12
#Mann= 5 ,-1,0
       0      .1       0  235.44    .045       0   334.7      .1       0
  527.38     .12       0  867.38      .1       0
#XS Ineff= 2 , 0
                          526.33         2845.12
Permanent Ineff=
       F       F
Bank Sta=235.44,334.7
XS Rating Curve= 0 ,0
Exp/Cntr(USF)=0,0
Exp/Cntr=0.3,0.1

Type RM Length L Ch R = 1 ,96694   ,239.8,239.8,239.8
XS GIS Cut Line= 2
2362027.46674948675223.9485684532362895.76301738674714.765236969
#Sta/Elev= 30
       0 2956.68    28.6 2940.68    37.9 2936.97    61.1 2922.33      75 2917.53
   107.5 2900.08   119.5 2897.44   158.5 2881.12   167.8 2879.33   186.3  2869.7
   195.6 2867.22   227.6 2850.07   241.9 2839.25   251.2 2837.86   260.5  2832.3
   268.5 2830.31   315.3 2830.45   332.8 2832.49   356.2 2833.69   373.8 2838.17
   390.3 2839.89   438.1 2839.15   756.7 2842.47     783 2845.47     812 2853.76
   840.1 2859.78   914.5 2869.29     932 2872.78   978.1 2883.69  1006.6 2895.45
#Mann= 5 ,-1,0
       0      .1       0   260.5    .045       0   332.8      .1       0
     490     .12       0     840      .1       0
Bank Sta=260.5,332.8
XS Rating Curve= 0 ,0
Exp/Cntr=0.3,0.1

Type RM Length L Ch R = 1 ,96454   ,173.9,173.9,173.9
XS GIS Cut Line= 2
2362267.32099685 675406.590227842362896.72041466674850.109035261
#Sta/Elev= 30
       0 2885.01     7.3 2883.55    17.2    2883    49.2 2877.96    75.3 2871.53
    92.3 2868.73   171.2 2844.77   180.1 2839.96     188 2836.89   198.7 2835.79
   209.4 2832.31   219.5 2830.19   225.4 2829.97     285 2830.11   293.5 2832.28
   316.2 2832.97   322.2 2835.97   328.2 2838.02   384.2 2839.68   398.3 2839.12
   418.8 2840.78   473.2 2840.23   711.3 2841.69   727.3 2845.56   769.6 2848.47
   780.7 2850.04   787.2 2849.68   797.9  2850.3   817.4 2854.18   840.1 2861.11
#Mann= 7 ,-1,0
       0      .1       0   209.4    .045       0   293.5      .1       0
     450     .08       0     510     .12       0     640      .1       0
     770     .12       0
Bank Sta=209.4,293.5
XS Rating Curve= 0 ,0
Exp/Cntr(USF)=0,0
Exp/Cntr=0.3,0.1

Type RM Length L Ch R = 1 ,96280   ,256.9,256.9,256.9
XS GIS Cut Line= 2
 2362315.7230332675656.0566026562363070.75566242674814.488324297
#Sta/Elev= 30
       0 2943.62    41.5 2935.68    95.8 2919.32     106 2918.45   126.5  2910.8
   144.4 2901.38   156.4 2897.45   186.6 2883.86   202.7 2879.19   240.3 2863.46
   251.6 2860.56   261.8 2856.04   288.7 2849.95   310.2 2841.55   324.1 2834.17
   342.4 2832.91   347.9 2830.77   353.6 2829.45   390.8 2829.15   460.6  2829.6
   471.4 2830.82   498.1 2838.44   541.3  2839.9   821.3 2840.66   899.1 2842.24
   976.8 2846.44     998 2850.38  1016.4 2858.21  1051.8 2867.93  1130.6 2895.83
#Mann= 10 ,-1,0
       0      .1       0   347.9    .045       0   471.4      .1       0
     600     .12       0     650     .08       0     740     .12       0
     870      .1       0     940     .12       0    1000      .1       0
    1130     .06       0
Bank Sta=347.9,471.4
XS Rating Curve= 0 ,0
Exp/Cntr=0.3,0.1

Type RM Length L Ch R = 1 ,96023   ,199.3,199.3,199.3
XS GIS Cut Line= 2
2362590.81998108675756.408655866 2363235.5706042 674946.63257563
#Sta/Elev= 30
       0  2879.2      45 2871.85    75.7 2861.49    85.7 2859.31   145.6 2839.53
   165.5 2836.12   188.4 2833.66   208.2  2833.3   226.9 2831.19   259.8 2831.72
     270 2830.86   291.2 2828.53   321.1 2828.16   341.6 2831.03   351.8 2833.98
   372.3 2831.66   381.1 2832.15   397.8 2837.73   406.7 2838.93   432.4 2838.58
   445.3 2839.32   474.5 2838.66   484.8 2839.32   669.4 2840.47   745.5 2839.95
     882 2843.22   909.1 2845.17   982.5 2853.51    1004 2857.28  1035.1 2865.85
#Mann= 9 ,-1,0
       0      .1       0     270    .045       0   341.6      .1       0
     410     .12       0     450      .1       0     570     .12       0
     580     .08       0     700     .12       0     830      .1       0
Bank Sta=270,341.6
XS Rating Curve= 0 ,0
Exp/Cntr(USF)=0,0
Exp/Cntr=0.3,0.1

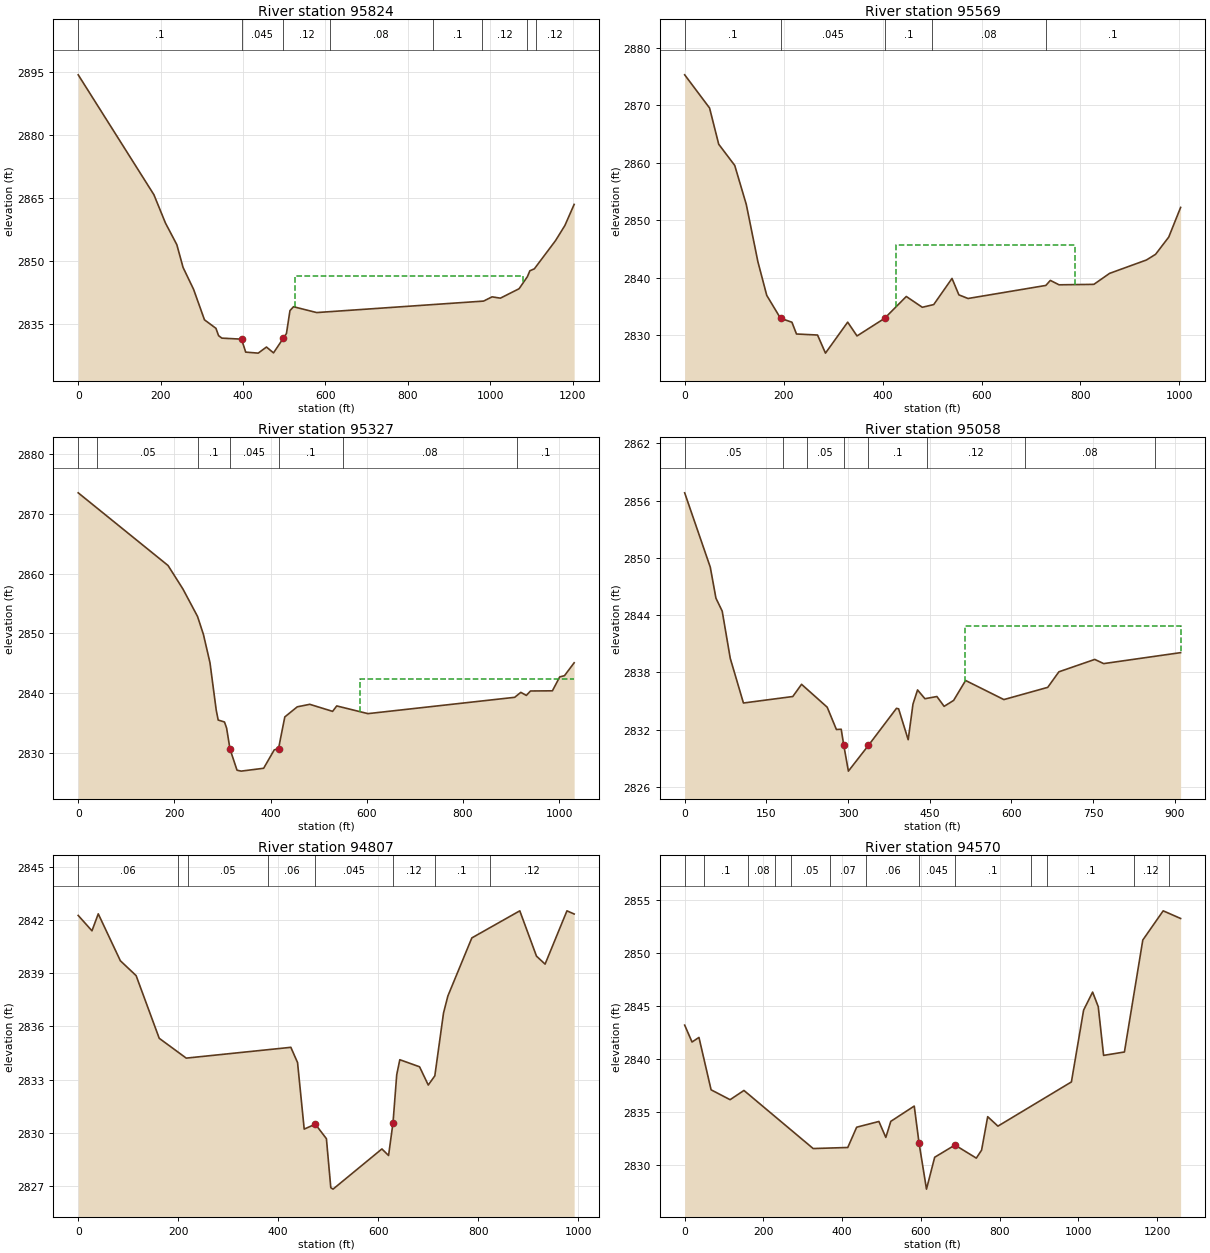
Type RM Length L Ch R = 1 ,95824   ,255.1,255.1,255.1
XS GIS Cut Line= 2
2362668.31769508675982.2667288282363406.08805977675031.597728281
#Sta/Elev= 30
       0  2894.3   183.7 2865.78   211.6 2859.06   239.3 2853.89   254.5 2848.46
   279.9 2843.28   306.4 2836.01   334.2 2833.99   340.6 2832.25   348.5 2831.66
   396.3 2831.41   406.4 2828.33   436.8 2828.09   456.8 2829.54   473.9 2828.15
   497.6 2831.62   505.3 2832.76   513.8  2838.2   522.4 2839.13   578.6 2837.74
   983.6 2840.47  1004.2 2841.48  1024.4 2841.17  1069.8 2843.41    1090 2846.29
  1095.9 2847.68  1106.8 2848.14  1158.1 2854.84  1180.9 2858.45  1203.4 2863.47
#Mann= 8 ,-1,0
       0      .1       0   396.3    .045       0   497.6     .12       0
     610     .08       0     860      .1       0     980     .12       0
    1090      .1       0    1110     .12       0
#XS Ineff= 1 ,-1
  526.17 1078.19 2846.39
Permanent Ineff=
       F
Bank Sta=396.3,497.6
XS Rating Curve= 0 ,0
Exp/Cntr=0.3,0.1

Type RM Length L Ch R = 1 ,95569   ,241.7,241.7,241.7
XS GIS Cut Line= 2
2363001.46472319676032.7303514912363504.21669717675165.387251334
#Sta/Elev= 30
       0 2875.31    50.3 2869.54    68.8 2863.23   101.2 2859.54   124.6 2852.73
     148 2842.78   165.9 2836.92   193.7 2832.94   216.8 2832.25     226  2830.2
   268.6 2830.02   284.6 2826.87   329.5 2832.26   348.4 2829.86   404.2 2832.93
     448 2836.73   480.3 2834.85   503.4 2835.32   540.4 2839.87   554.3 2837.01
   572.8 2836.38     730 2838.65   739.2 2839.53   756.8 2838.76   827.1 2838.84
   858.9 2840.75   933.4 2843.08   951.9 2844.07   978.5 2847.07  1002.5 2852.23
#Mann= 5 ,-1,0
       0      .1       0   193.7    .045       0   404.2      .1       0
     500     .08       0     730      .1       0
#XS Ineff= 1 ,-1
  426.85  789.262845.608
Permanent Ineff=
       F
Bank Sta=193.7,404.2
XS Rating Curve= 0 ,0
Exp/Cntr(USF)=0,0
Exp/Cntr=0.3,0.1

Type RM Length L Ch R = 1 ,95327   ,268.6,268.6,268.6
XS GIS Cut Line= 3
2363226.08287016 676222.742667752363495.89712822 675563.64041132
2363682.61899837 675304.89820566
#Sta/Elev= 30
       0 2873.52   186.8 2861.36   217.8 2857.42   248.1 2852.84   260.4 2849.82
     274  2845.1     287 2837.15   291.1  2835.5   304.2 2835.17   308.6 2834.15
   315.6 2830.66   330.2 2827.11   338.8 2826.95   385.6 2827.43   407.6  2830.5
   416.6 2830.73   429.6 2836.02   455.5 2837.71   481.5 2838.13     529 2836.95
   537.6 2837.86   602.5 2836.57   907.6  2839.3   920.4 2840.13   931.9 2839.62
   940.5 2840.36   986.1 2840.39  1001.3 2842.72  1011.2 2842.92  1031.3 2845.08
#Mann= 7 ,-1,0
       0      .1       0      40     .05       0     250      .1       0
   315.6    .045       0   416.6      .1       0     550     .08       0
  912.19      .1       0
#XS Ineff= 2 , 0
                          585.45         2842.34
Permanent Ineff=
       F       F
Bank Sta=315.6,416.6
XS Rating Curve= 0 ,0
Exp/Cntr=0.3,0.1

Type RM Length L Ch R = 1 ,95058   ,251.5,251.5,251.5
XS GIS Cut Line= 3
2363386.88649684676223.5470322472363555.85319457676109.004219721
2363847.67710244675465.634615379
#Sta/Elev= 30
       0 2856.82      47 2849.03    57.4 2845.78    68.9 2844.42    83.7 2839.47
   107.9 2834.79   198.5 2835.47   214.6 2836.75   261.7 2834.35   278.6 2832.01
   287.4 2832.04   292.1 2830.37   300.6 2827.65  337.27 2830.34   388.9 2834.23
   392.8 2834.18   410.4 2830.94   419.2 2834.68   427.6 2836.16   441.1 2835.24
   463.1 2835.47   476.4 2834.44   493.8 2835.06   515.8 2837.15   586.1 2835.15
   666.6 2836.43   687.1 2838.06     753 2839.36   769.3 2838.92   910.6 2840.07
#Mann= 8 ,-1,0
       0     .05       0     180     .06       0  224.13     .05       0
   292.1    .045       0  337.27      .1       0  444.13     .12       0
  624.13     .08       0  864.13     .12       0
#XS Ineff= 2 , 0
                          514.41         2842.81
Permanent Ineff=
       F       F
Bank Sta=292.1,337.27
XS Rating Curve= 0 ,0
Exp/Cntr(USF)=0,0
Exp/Cntr=0.3,0.1

Type RM Length L Ch R = 1 ,94807   ,236.5,236.5,236.5
XS GIS Cut Line= 4
 2363481.6163423      676430.5992363799.23051301676170.368336937
 2363913.0996577675934.169956104     2364039.121       675641.27
#Sta/Elev= 30
       0 2842.27    27.5  2841.4    40.1 2842.36    84.3 2839.71   115.8 2838.87
     162 2835.33     216 2834.21   425.2 2834.82   438.6 2833.96   451.9  2830.2
   474.1 2830.48   496.3 2829.66   505.1 2826.89   509.6 2826.81   607.3 2829.08
   620.6 2828.71   629.5 2830.56   636.9 2833.27   643.1 2834.12   682.6 2833.72
     700 2832.69   713.1 2833.21   730.5 2836.76   739.2 2837.72   787.1    2841
     883 2842.53   916.4 2839.97   933.6 2839.52   977.3 2842.53   991.7 2842.35
#Mann= 8 ,-1,0
       0     .06       0     200     .07       0     220     .05       0
     380     .06       0   474.1    .045       0   629.5     .12       0
  712.82      .1       0  822.82     .12       0
Bank Sta=474.1,629.5
XS Rating Curve= 0 ,0
Exp/Cntr=0.3,0.1

Type RM Length L Ch R = 1 ,94570   ,206.1,206.1,206.1
XS GIS Cut Line= 3
2363491.16512374676482.5487304782363982.92690119 676258.19658316
2364440.69592905675702.981673129
#Sta/Elev= 30
       0  2843.2    18.7 2841.61    36.3 2842.04    67.1 2837.11   115.4 2836.18
   150.6 2837.05   326.5 2831.58   414.4 2831.68     437 2833.59   493.5 2834.13
   511.1 2832.63   523.7 2834.14   583.3 2835.58   595.52832.098   614.4 2827.76
   635.2 2830.76   686.72831.911     741 2830.68   754.4 2831.43   769.9 2834.58
   795.9 2833.69   982.6 2837.85  1013.6 2844.61  1036.5 2846.31  1050.8 2844.94
  1064.4 2840.35  1117.3 2840.67    1164 2851.21  1215.8 2853.96  1260.1 2853.24
#Mann= 13 ,-1,0
       0     .06       0      50      .1       0     160     .08       0
     230     .07       0     270     .05       0     370     .07       0
     460     .06       0   595.5    .045       0   686.7      .1       0
  880.52     .12       0  920.52      .1       0 1140.52     .12       0
 1230.52      .1       0
Bank Sta=595.5,686.7
XS Rating Curve= 0 ,0
Exp/Cntr(USF)=0,0
Exp/Cntr=0.3,0.1

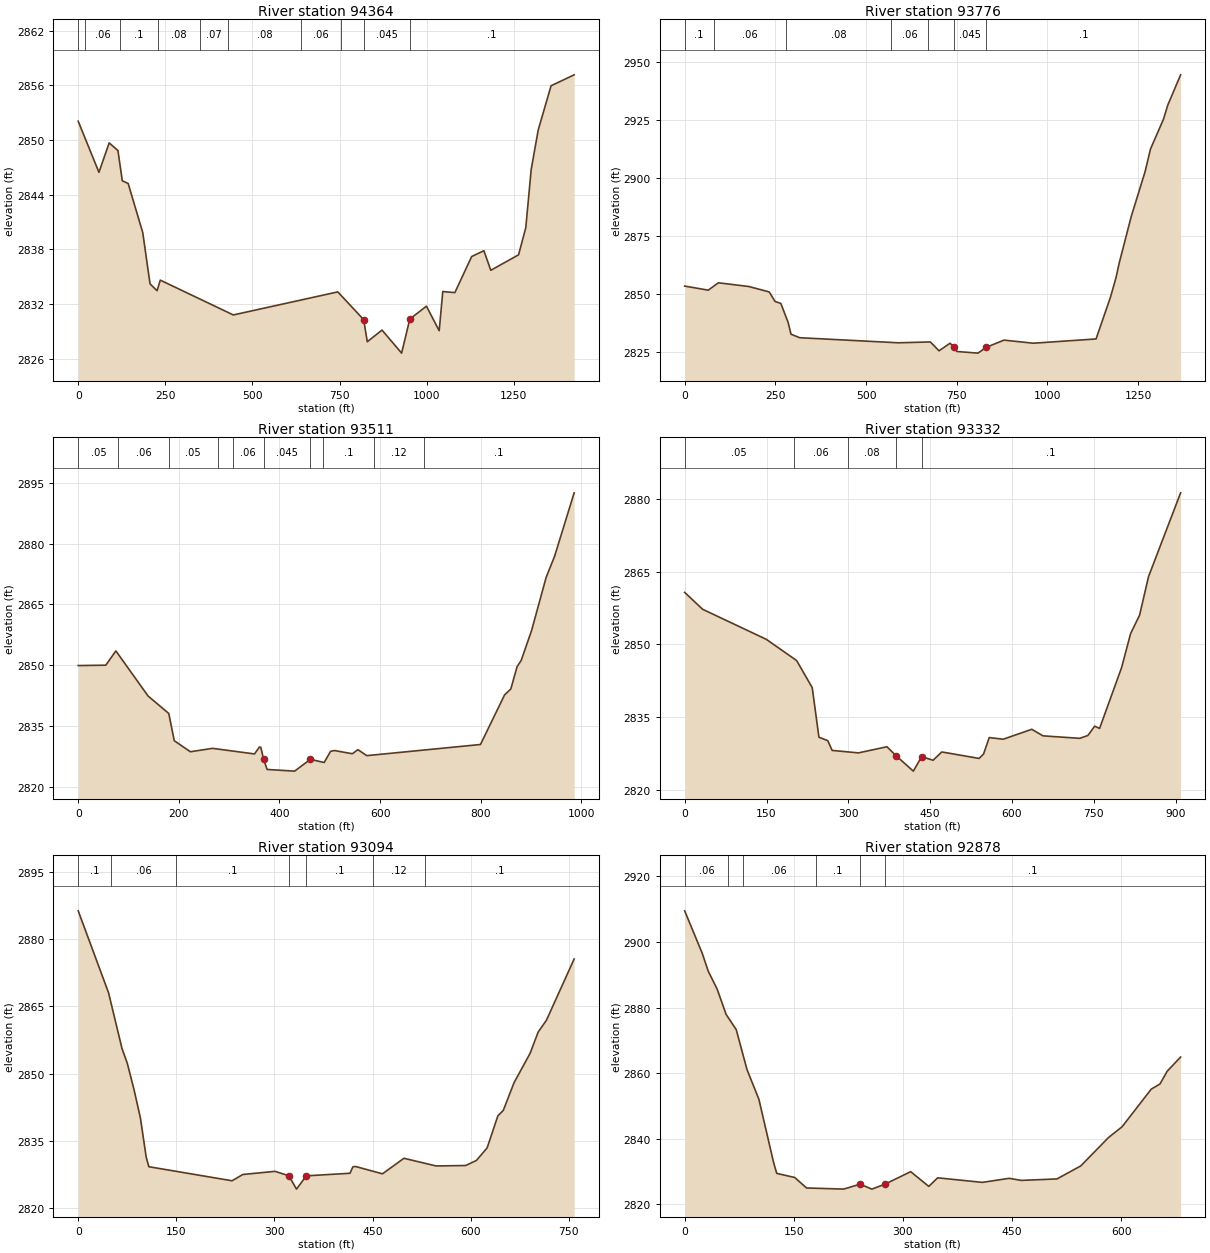
Type RM Length L Ch R = 1 ,94364   ,588.4,588.4,588.4
XS GIS Cut Line= 4
2363419.39494088676591.7314435422364034.24211513 676399.78442473
2364326.83514336676220.3900134492364663.33377239675943.790585131
#Sta/Elev= 30
       0 2852.07    59.5 2846.46    88.8 2849.69     114 2848.85   126.5 2845.53
   143.3 2845.24   185.2 2839.84   206.1 2834.22   226.2 2833.47   235.5 2834.63
     445 2830.81   744.9 2833.34     819 2830.29   829.4 2827.87   871.6 2829.15
   927.9 2826.62   951.4 2830.36   999.1 2831.77  1035.7 2829.08    1046 2833.38
  1080.6 2833.26  1128.9 2837.22  1163.9 2837.86  1183.8 2835.71  1263.5 2837.41
  1284.2  2840.4  1299.7 2846.79  1319.9 2851.12  1356.7 2855.96  1422.9 2857.16
#Mann= 10 ,-1,0
       0      .1       0      20     .06       0     120      .1       0
     230     .08       0     350     .07       0     430     .08       0
     640     .06       0  754.11     .05       0     819    .045       0
   951.4      .1       0
Bank Sta=819,951.4
XS Rating Curve= 0 ,0
Exp/Cntr=0.3,0.1

Type RM Length L Ch R = 1 ,93776   ,265.3,265.3,265.3
XS GIS Cut Line= 4
2363359.16275948676682.3590005912364090.68591221676668.230051805
2364180.25485723 676753.690762442364664.98762085676917.354570499
#Sta/Elev= 30
       0 2853.41      65 2851.65      93 2854.83     177 2853.22   233.1 2850.88
   249.1 2846.77   265.1 2845.91   285.1 2837.75   293.1 2832.62   317.1 2831.11
   589.1 2828.91   677.2 2829.28   701.1 2825.46   731.7 2828.74   741.9 2827.05
   750.3 2825.16   808.4 2824.45   831.5 2826.97   880.2 2830.07   960.9 2828.73
    1134 2830.57  1173.8 2848.64  1188.9 2856.98  1197.3 2863.03  1231.1 2883.53
  1269.1 2902.79  1284.2 2912.66  1319.8 2925.47  1331.6 2931.53  1367.1 2944.66
#Mann= 7 ,-1,0
       0      .1       0      80     .06       0     280     .08       0
     570     .06       0     670     .05       0   741.9    .045       0
   831.5      .1       0
Bank Sta=741.9,831.5
XS Rating Curve= 0 ,0
Exp/Cntr=0.3,0.1

Type RM Length L Ch R = 1 ,93511   ,178.4,178.4,178.4
XS GIS Cut Line= 4
2363553.35670961676866.7704560642363830.73754629676874.928715966
2364222.33402161676999.3421794792364509.91268318677074.806083577
#Sta/Elev= 30
       0 2849.93    54.8 2850.02    74.9 2853.54   138.9 2842.41     180 2838.11
   190.9 2831.39   222.9 2828.66   266.9  2829.5   350.4 2828.12   360.1 2829.81
   362.9 2829.77   368.42826.832   375.5 2824.29   430.1 2823.88   461.52826.786
   488.9 2826.01   501.5 2828.76   509.5 2828.96   544.8 2828.17     556 2829.18
   573.5  2827.7   799.5 2830.45   847.4 2842.68   859.8 2844.14   872.2 2849.62
   880.5 2851.21   901.2 2858.62   930.1 2871.71   946.7 2876.85   985.7 2892.55
#Mann= 10 ,-1,0
       0     .05       0      80     .06       0     180     .05       0
   277.5     .08       0   307.5     .06       0   368.4    .045       0
   461.5     .06       0   487.5      .1       0   587.5     .12       0
   687.5      .1       0
Bank Sta=368.4,461.5
XS Rating Curve= 0 ,0
Exp/Cntr(USF)=0,0
Exp/Cntr=0.3,0.1

Type RM Length L Ch R = 1 ,93332   ,238.6,238.6,238.6
XS GIS Cut Line= 3
2363535.39803274677052.5016841192364167.99869724677118.852366612
2364433.29083306677183.414016369
#Sta/Elev= 30
       0 2860.71      33 2857.23   149.6 2851.06   205.2  2846.7   233.8 2841.13
   246.1 2830.94   262.2 2830.24   270.3 2828.23   318.5 2827.72   370.8 2828.98
   387.42827.144   419.1 2823.97   434.5 2826.95   455.3  2826.2   471.3 2827.91
   539.7 2826.58   547.8 2827.47   558.3 2830.87     584 2830.53   636.3 2832.57
   656.8 2831.22   724.2 2830.71   739.2  2831.3   751.5 2833.21   760.6 2832.75
   800.9 2845.25   817.4 2852.23   833.9 2856.03   850.3 2863.95   909.1 2881.17
#Mann= 5 ,-1,0
       0     .05       0     200     .06       0     300     .08       0
   387.4    .045       0   434.5      .1       0
Bank Sta=387.4,434.5
XS Rating Curve= 0 ,0
Exp/Cntr=0.3,0.1

Type RM Length L Ch R = 1 ,93094   ,216,216,216
XS GIS Cut Line= 2
2363590.96008572677256.4260132532364329.73584356677426.389761222
#Sta/Elev= 30
       0 2886.29    46.4 2868.03    66.9 2855.64    75.1 2852.29    85.1  2846.6
    95.1 2840.14   103.9 2831.44     108 2829.29   235.2 2826.16   251.6 2827.56
   300.9 2828.26     322 2827.28   333.7  2824.3   348.7 2827.26   415.4 2827.83
   419.9 2829.27     424 2829.34   465.1 2827.71   497.9 2831.17   547.1 2829.46
   592.3 2829.56   608.7 2830.69   625.1 2833.49   641.5 2840.62   649.8 2841.84
   666.2    2848   690.8 2854.56   703.1 2859.29   715.7 2861.91   758.1 2875.56
#Mann= 7 ,-1,0
       0      .1       0      50     .06       0     150      .1       0
     322    .045       0   348.7      .1       0     450     .12       0
     530      .1       0
Bank Sta=322,348.7
XS Rating Curve= 0 ,0
Exp/Cntr(USF)=0,0
Exp/Cntr=0.3,0.1

Type RM Length L Ch R = 1 ,92878   ,286.7,286.7,286.7
XS GIS Cut Line= 3
2363556.57358059 677461.797329792364118.56396293677586.656044767
2364224.57617745677582.665695867
#Sta/Elev= 30
       0 2909.52    24.2 2896.52    32.4 2891.11    44.7  2885.6      57 2877.91
    70.9 2873.27    85.6 2861.14     102 2852.04   122.5 2832.51   126.6 2829.41
   151.2 2828.17   167.6 2824.96   218.5 2824.62   241.3 2826.12   257.3 2824.61
  275.28 2826.11   310.7 2829.94   335.6 2825.44   347.8 2828.06   409.3 2826.67
   446.2 2827.91   462.6 2827.27   511.8 2827.72   544.6  2831.7   582.5 2840.32
   601.3 2843.63   641.4 2855.11   653.4 2856.69   663.5 2860.62   681.8 2864.91
#Mann= 6 ,-1,0
       0     .06       0      60      .1       0      80     .06       0
     180      .1       0   241.3    .045       0  275.28      .1       0
Bank Sta=241.3,275.28
XS Rating Curve= 0 ,0
Exp/Cntr=0.3,0.1