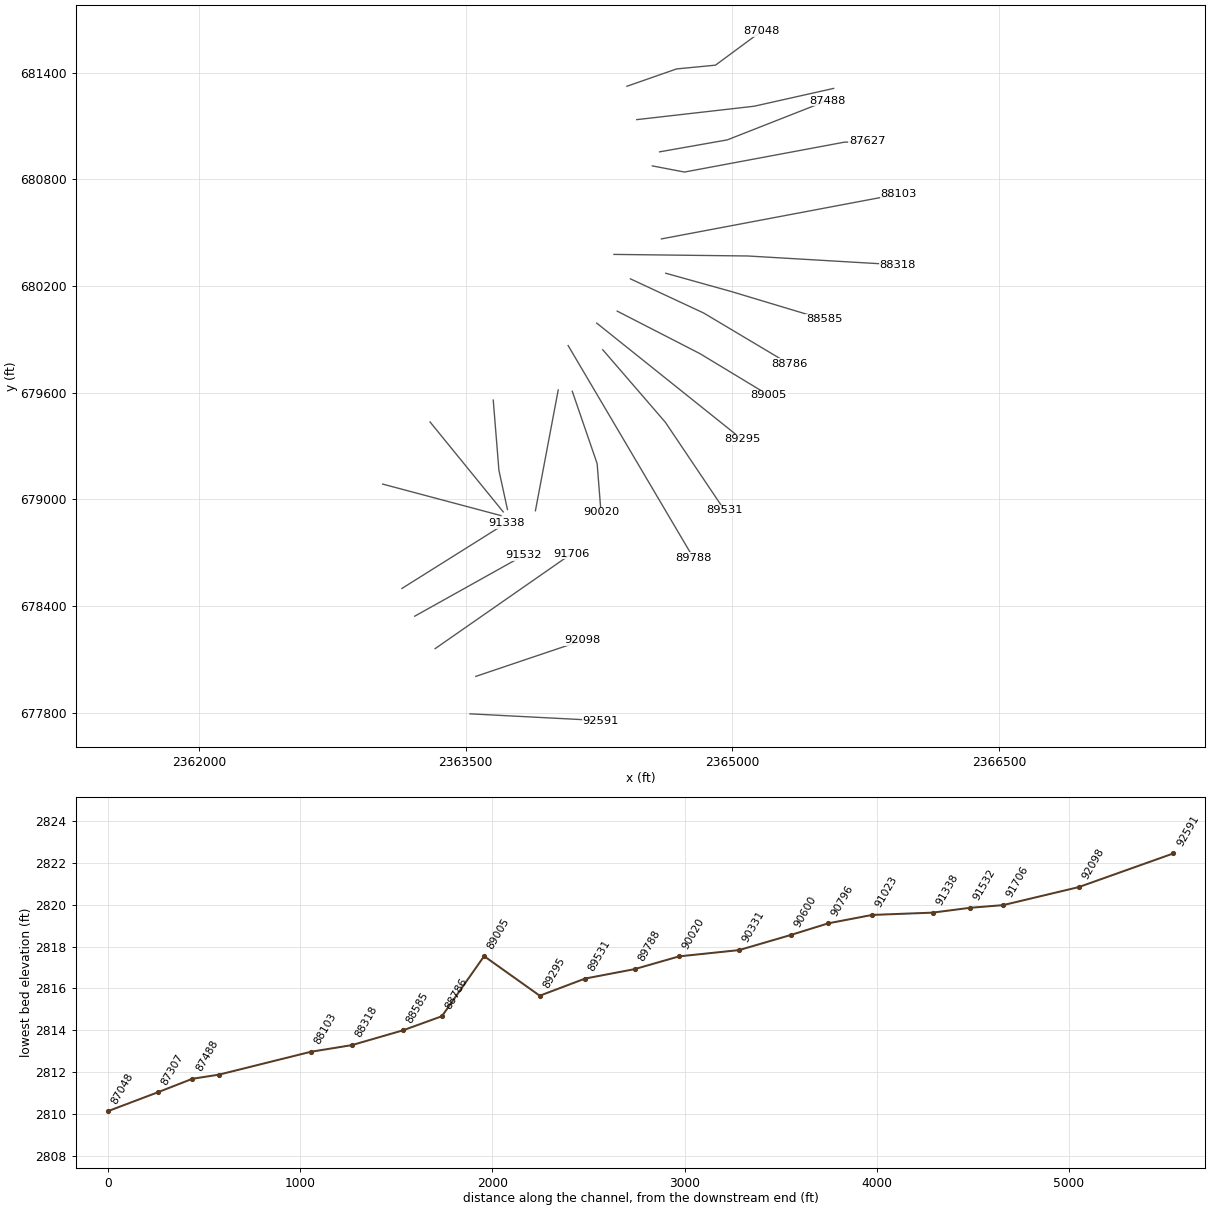
HEC-RAS study LAURELFK.prj: LAURELFK

--- LAURELFK.g01 (geometry) --- (continued)

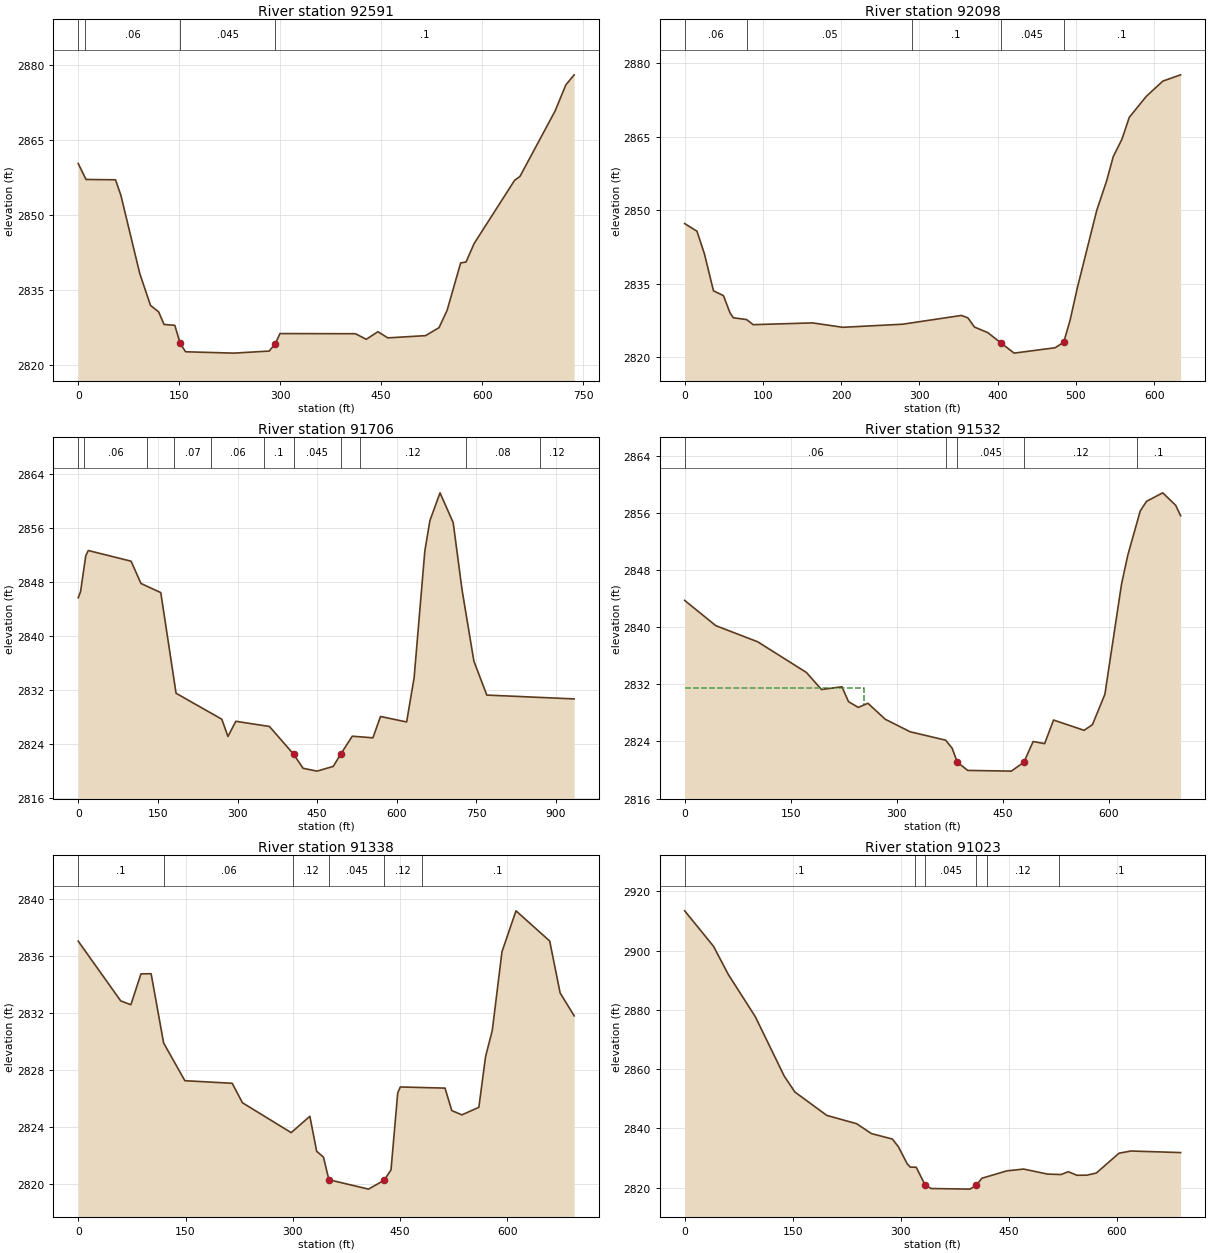
Type RM Length L Ch R = 1 ,92591   ,492.7,492.7,492.7
XS GIS Cut Line= 2
2363524.87913382677793.4648275482364260.58564842677755.470594399
#Sta/Elev= 30
       0 2860.27    11.6 2857.08    55.4 2857.02    63.4 2853.93    91.4 2838.34
   107.4 2831.97   119.5 2830.68   127.5 2828.17   143.5    2828   151.5 2824.38
   159.5 2822.72   231.2 2822.45   283.7 2822.86   292.9 2824.37   299.7 2826.35
   411.8 2826.32   427.9 2825.21   445.2 2826.72   459.9 2825.49     516 2825.94
     536 2827.53     548 2830.99   568.1 2840.44   576.1 2840.62   588.1  2844.3
   648.2 2856.91   656.2 2857.69   708.5 2870.77   724.3 2875.93   736.7 2877.95
#Mann= 4 ,-1,0
       0     .05       0      10     .06       0   151.5    .045       0
   292.9      .1       0
Bank Sta=151.5,292.9
XS Rating Curve= 0 ,0
Exp/Cntr(USF)=0,0
Exp/Cntr=0.3,0.1

Type RM Length L Ch R = 1 ,92098   ,392.7,392.7,392.7
XS GIS Cut Line= 2
2363557.25827326678004.1778318352364157.67102985 678206.72160977
#Sta/Elev= 30
       0 2847.28    15.7 2845.72    25.2 2841.13    36.8 2833.56    49.5 2832.58
      58 2829.04    62.2 2828.06    79.1 2827.69    87.5 2826.65   163.5 2827.01
     202 2826.11   278.4 2826.74   353.5 2828.53   361.9 2828.04   370.3 2826.16
   387.2 2825.03   403.6 2822.99     421 2820.84   473.4 2821.94   484.3 2823.06
   492.4 2827.51   501.8 2834.21   526.5 2849.96   539.2 2856.02   547.6 2860.94
   558.7 2864.49   568.1 2868.96   589.9 2873.26     611 2876.36   633.7 2877.64
#Mann= 5 ,-1,0
       0     .06       0      80     .05       0     290      .1       0
   403.6    .045       0   484.3      .1       0
Bank Sta=403.6,484.3
XS Rating Curve= 0 ,0
Exp/Cntr=0.3,0.1

Type RM Length L Ch R = 1 ,91706   ,173.5,173.5,173.5
XS GIS Cut Line= 2
2363328.53966647678160.2904763032364095.18976481678693.793574639
#Sta/Elev= 30
       0 2845.65     4.4 2846.54    14.2 2851.86      19 2852.64    99.6 2851.06
   118.2 2847.76   155.5 2846.41   184.3 2831.51   270.5 2827.66     282 2825.11
   296.8 2827.36   360.2 2826.59   405.5  2822.5   423.5  2820.4   449.7 2819.98
   480.3 2820.68   494.6 2822.52   516.1 2825.15     555 2824.91   569.3 2828.07
   618.5 2827.26   632.6  2833.8   652.8 2852.58   662.3 2857.06   681.4 2861.18
   706.2 2856.77   722.9 2846.81   745.2 2836.26   769.5 2831.24     934 2830.67
#Mann= 11 ,-1,0
       0      .1       0      10     .06       0     130     .05       0
     180     .07       0     250     .06       0     350      .1       0
   405.5    .045       0   494.6      .1       0     530     .12       0
     730     .08       0     870     .12       0
Bank Sta=405.5,494.6
XS Rating Curve= 0 ,0
Exp/Cntr=0.3,0.1

Type RM Length L Ch R = 1 ,91532   ,193.9,193.9,193.9
XS GIS Cut Line= 2
 2363213.8696104678342.8241874592363826.26756833678684.772285796
#Sta/Elev= 30
       0 2843.74    43.9 2840.21   103.4 2837.94   172.1 2833.66   193.5 2831.27
   222.5 2831.65   231.7 2829.57   245.5 2828.77   259.2 2829.34   283.8  2827.1
   318.8 2825.36   369.1 2824.18   378.3 2823.05   385.6  2821.1   400.3 2819.95
     462 2819.85   479.7 2821.09   492.8 2823.99   509.1  2823.7   521.7    2827
   564.9 2825.56   576.7 2826.35   594.3  2830.6   617.8    2846   626.7 2850.06
   644.3 2856.26   653.2  2857.6   676.1 2858.79   694.4 2857.05   701.4 2855.59
#Mann= 5 ,-1,0
       0     .06       0     370     .12       0   385.6    .045       0
   479.7     .12       0     640      .1       0
#XS Ineff= 2 , 0
          253.03 2831.44
Permanent Ineff=
       F       F
Bank Sta=385.6,479.7
XS Rating Curve= 0 ,0
Exp/Cntr(USF)=0,0
Exp/Cntr=0.3,0.1

Type RM Length L Ch R = 1 ,91338   ,314.7,314.7,314.7
XS GIS Cut Line= 2
2363141.87088704678498.9190359882363729.00437116678867.353928581
#Sta/Elev= 30
       0 2837.05    59.4 2832.85    73.6 2832.58    87.7 2834.75   101.9 2834.76
   119.4 2829.89   149.1 2827.24   215.2 2827.06   229.6 2825.69   297.7 2823.59
   323.8 2824.74   333.3 2822.28   342.8 2821.87   350.4 2820.28   405.8 2819.62
   427.7 2820.25   437.2 2820.97   446.6 2826.38   450.2  2826.8   512.7 2826.72
   522.2 2825.14   536.3 2824.84     560 2825.37   569.4 2828.94   578.8 2830.78
   592.3  2836.3   611.9 2839.18     659 2837.06   673.6 2833.41   693.2  2831.8
#Mann= 6 ,-1,0
       0      .1       0     120     .06       0     300     .12       0
   350.4    .045       0   427.7     .12       0     480      .1       0
Bank Sta=350.4,427.7
XS Rating Curve= 0 ,0
Exp/Cntr=0.3,0.1

Type RM Length L Ch R = 1 ,91023   ,227.5,227.5,227.5
XS GIS Cut Line= 2
  2363033.569704679085.7841465732363698.81418622678908.592859253
#Sta/Elev= 30
       0  2913.4      40 2901.45    60.6 2891.91    97.9 2877.75   138.2 2857.64
     153 2852.27   197.3 2844.38   238.6 2841.59   259.3 2838.24   288.3 2836.41
   296.6 2833.82     309 2828.01   313.1 2826.94   321.4  2826.9   333.9 2820.83
   342.1 2819.72   395.9 2819.51   404.7 2820.77   412.5 2823.18   447.2 2825.67
   470.5 2826.28   503.6 2824.59   522.4 2824.43   532.5 2825.39   544.5 2824.18
   558.3 2824.22   571.4 2824.94   602.9 2831.63   619.5 2832.37   688.4 2831.84
#Mann= 6 ,-1,0
       0      .1       0     320     .07       0   333.9    .045       0
   404.7     .07       0     420     .12       0     520      .1       0
Bank Sta=333.9,404.7
XS Rating Curve= 0 ,0
Exp/Cntr(USF)=0,0
Exp/Cntr=0.3,0.1

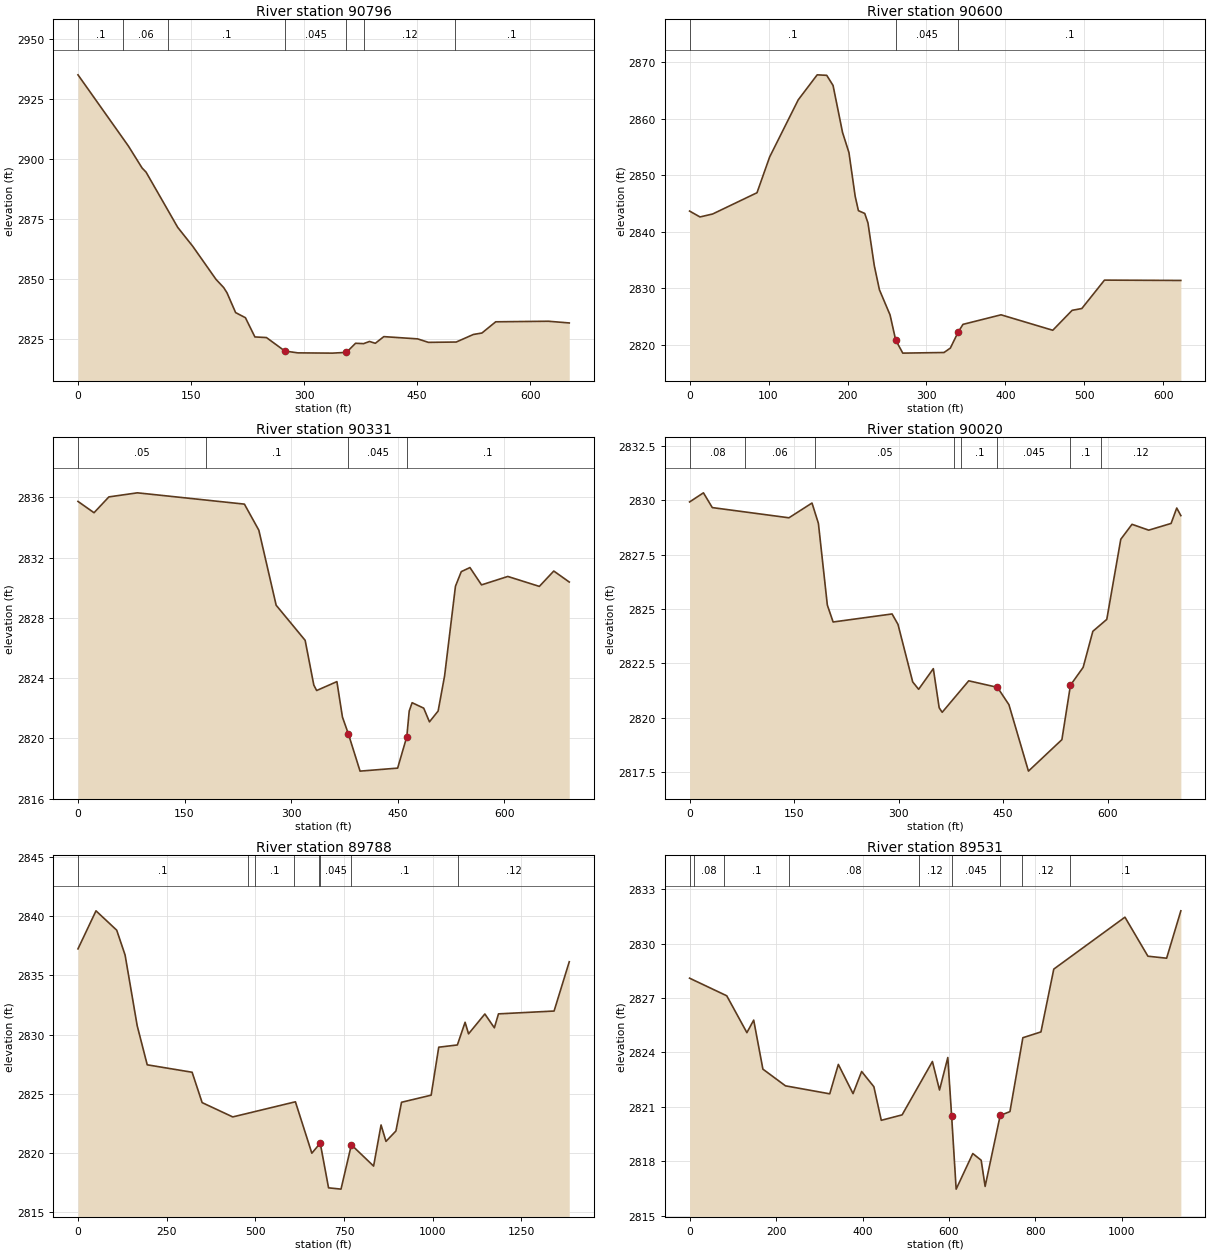
Type RM Length L Ch R = 1 ,90796   ,196,196,196
XS GIS Cut Line= 2
2363299.92573492679435.1824903122363711.52228341678929.521458279
#Sta/Elev= 30
       0 2934.95      67 2905.27    85.1 2896.16    90.3 2894.48   132.4 2871.45
   152.5  2863.5   183.1 2849.85   193.4 2846.39   197.8 2844.21   209.2 2835.98
   222.2 2833.86   234.8 2825.85   250.1 2825.59   274.52819.992   291.6 2819.22
   337.8 2819.11   356.32819.427   368.4 2823.21   379.1 2823.06   386.9 2823.97
   394.6  2823.2   405.9 2825.98   450.8 2825.04   465.1 2823.59     502 2823.73
   524.8 2826.88   536.1 2827.48   554.4 2832.15   624.3 2832.38     652 2831.67
#Mann= 7 ,-1,0
       0      .1       0      60     .06       0     120      .1       0
   274.5    .045       0   356.3      .1       0     380     .12       0
     500      .1       0
Bank Sta=274.5,356.3
XS Rating Curve= 0 ,0
Exp/Cntr=0.3,0.1

Type RM Length L Ch R = 1 ,90600   ,268.5,268.5,268.5
XS GIS Cut Line= 3
2363655.29351916679558.2942460922363687.33218811679162.737640915
 2363735.2944801678942.686074211
#Sta/Elev= 30
       0 2843.65    13.2 2842.61    29.2 2843.13    85.4 2846.89   101.4 2853.21
   137.6  2863.3   161.6 2867.72   173.7 2867.63   181.7 2865.84   193.7 2857.54
   201.8 2853.99   209.7 2846.27   213.8 2843.72   221.8 2843.23   225.9 2841.55
   233.9 2834.02   240.4 2829.75   253.9 2825.29     2612820.853     270 2818.55
   322.2 2818.66   330.2 2819.44   340.22822.286   346.2 2823.63   394.4 2825.32
   459.9 2822.59   484.4 2826.11   496.7 2826.43   525.4 2831.45   622.1 2831.39
#Mann= 3 ,-1,0
       0      .1       0     261    .045       0   340.2      .1       0
Bank Sta=261,340.2
XS Rating Curve= 0 ,0
Exp/Cntr(USF)=0,0
Exp/Cntr=0.3,0.1

Type RM Length L Ch R = 1 ,90331   ,311.8,311.8,311.8
XS GIS Cut Line= 2
2364020.81682125679615.3875434372363892.56593041678935.830072221
#Sta/Elev= 30
       0 2835.73    22.6 2834.98    43.5 2836.03    83.7  2836.3   234.3 2835.55
   254.6 2833.82     279 2828.84   319.8 2826.51     332 2823.54     336 2823.18
   364.5 2823.77   372.3 2821.42   380.8 2820.28   397.1 2817.83     450 2818.03
   462.92820.115   466.3 2821.82   470.4 2822.37   486.7 2822.01   494.8  2821.1
     507 2821.82   516.1 2824.15   531.4  2830.1   539.6 2831.07   551.8 2831.34
   568.1 2830.19   605.1 2830.75   649.5 2830.09   669.8 2831.11   691.6 2830.38
#Mann= 4 ,-1,0
       0     .05       0     180      .1       0   380.8    .045       0
   462.9      .1       0
Bank Sta=380.8,462.9
XS Rating Curve= 0 ,0
Exp/Cntr=0.3,0.1

Type RM Length L Ch R = 1 ,90020   ,231.5,231.5,231.5
XS GIS Cut Line= 3
  2364099.826047679608.0321513052364239.71390541679200.803052377
2364261.47423894678927.244573707
#Sta/Elev= 30
       0 2829.93    19.9 2830.35    32.6 2829.67   142.6  2829.2   175.7 2829.88
   184.9 2828.94   197.7 2825.18     206  2824.4   290.6 2824.77   299.1 2824.29
   320.2 2821.64   328.7  2821.3   349.8 2822.25   358.2 2820.45   362.5 2820.24
   400.6 2821.69   441.8 2821.39   458.3 2820.59   486.3 2817.53   534.3 2818.98
   546.6 2821.49   564.8 2822.31   578.7 2823.97   598.7 2824.52   618.8 2828.21
   634.9  2828.9   658.9 2828.63     691 2828.94   699.1 2829.65     705  2829.3
#Mann= 8 ,-1,0
       0     .08       0      80     .06       0     180     .05       0
     380     .08       0     390      .1       0   441.8    .045       0
   546.6      .1       0  590.59     .12       0
Bank Sta=441.8,546.6
XS Rating Curve= 0 ,0
Exp/Cntr(USF)=0,0
Exp/Cntr=0.3,0.1

Type RM Length L Ch R = 1 ,89788   ,257.4,257.4,257.4
XS GIS Cut Line= 2
2364076.67083964679864.9351773592364780.43334407678672.325898758
#Sta/Elev= 30
       0 2837.25    50.8 2840.47   109.2 2838.83   132.8 2836.73   166.9 2830.75
   195.2 2827.44   321.7 2826.81     350 2824.24   436.3 2823.03   612.9 2824.31
   659.2 2819.96   682.9 2820.81   706.3 2817.03   741.4 2816.92   770.6 2820.67
   833.3 2818.87   854.3 2822.35   868.2 2820.96   896.2 2821.84     912 2824.27
   995.5 2824.87  1016.9 2828.93  1069.4 2829.12  1091.2 2831.04  1100.9 2830.06
  1146.9 2831.74  1173.7 2830.57  1185.3 2831.75    1342 2831.99  1384.8 2836.16
#Mann= 8 ,-1,0
       0      .1       0     480     .08       0     500      .1       0
     610     .05       0     680     .08       0   682.9    .045       0
   770.6      .1       0    1070     .12       0
Bank Sta=682.9,770.6
XS Rating Curve= 0 ,0
Exp/Cntr=0.3,0.1

Type RM Length L Ch R = 1 ,89531   ,236.1,236.1,236.1
XS GIS Cut Line= 3
2364271.27598353679841.6011665572364623.79338672679433.128619999
2364956.72648974678937.925601226
#Sta/Elev= 30
       0 2828.09      86 2827.12   132.6 2825.09   148.3 2825.78   169.6 2823.08
   221.8 2822.16   324.2 2821.72   344.1 2823.34   378.1 2821.73     398 2822.95
   426.3 2822.11   443.4 2820.26   491.6 2820.56   561.7  2823.5   578.1 2821.93
   597.3 2823.72   606.1 2820.51   616.6 2816.47   655.1 2818.43   674.5 2818.06
   683.6 2816.62   718.5 2820.53     741 2820.74   770.9 2824.81   812.7 2825.13
   842.4 2828.59    1007 2831.45  1060.1  2829.3  1103.4 2829.19  1136.3  2831.8
#Mann= 9 ,-1,0
       0      .1       0      10     .08       0      80      .1       0
     230     .08       0     530     .12       0   606.1    .045       0
   718.5      .1       0  769.55     .12       0  879.55      .1       0
Bank Sta=606.1,718.5
XS Rating Curve= 0 ,0
Exp/Cntr(USF)=0,0
Exp/Cntr=0.3,0.1

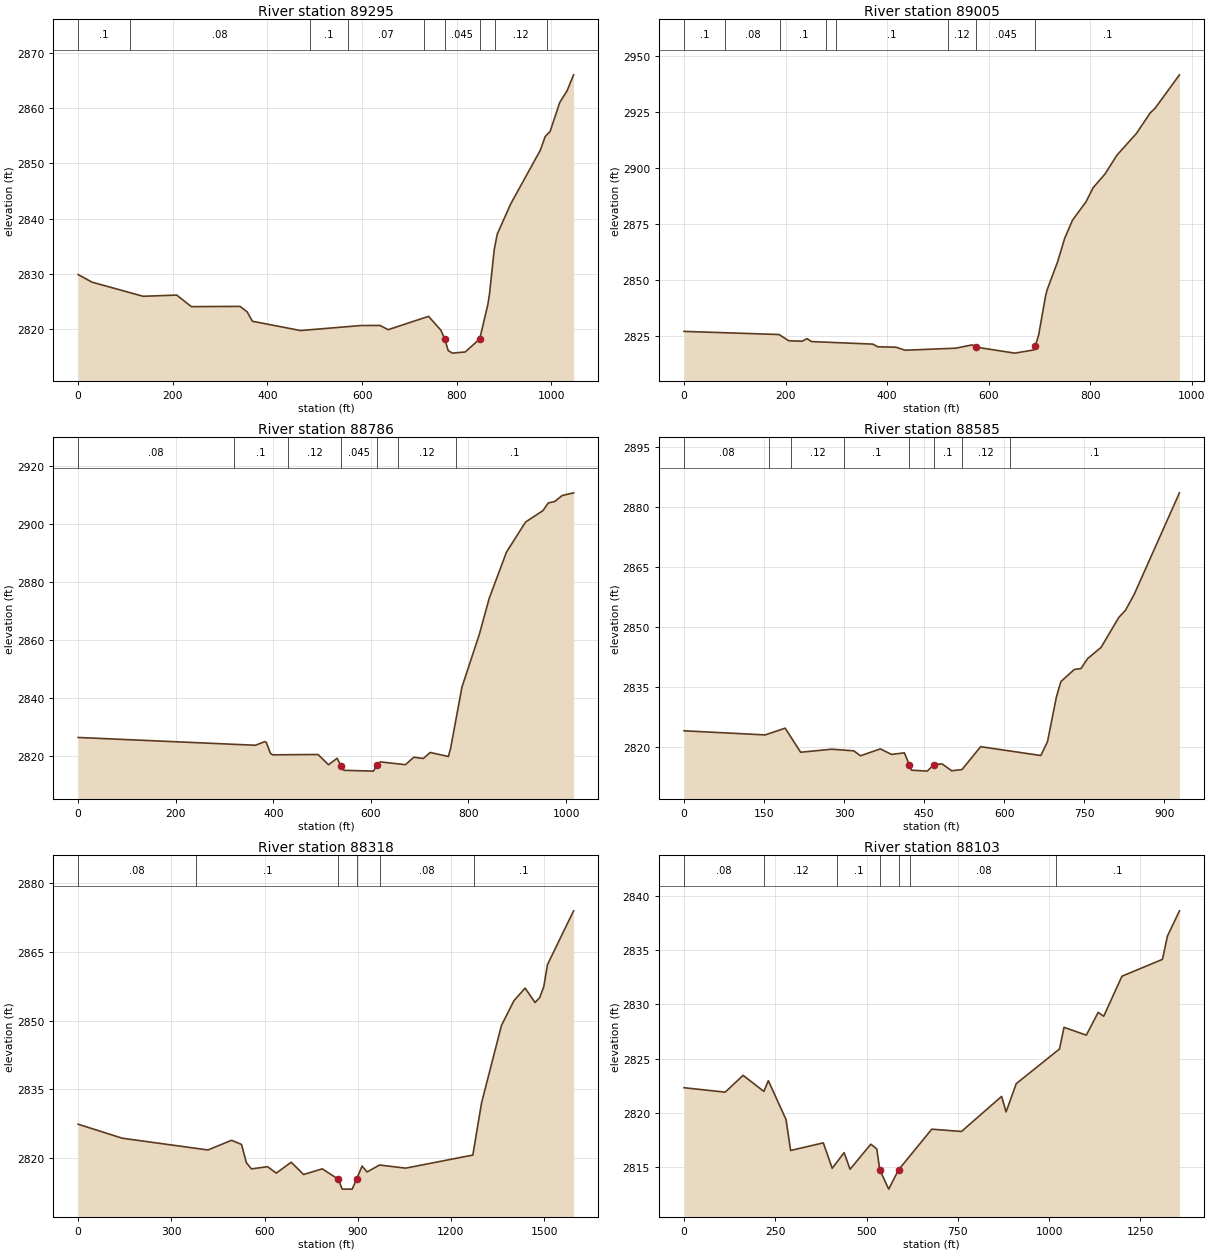
Type RM Length L Ch R = 1 ,89295   ,289.3,289.3,289.3
XS GIS Cut Line= 2
 2364237.3990936679991.2445260622365054.98562085679337.279379742
#Sta/Elev= 30
       0 2829.87    29.2  2828.5   137.2 2825.94   208.2 2826.16   239.2 2824.07
   342.1 2824.11     357 2823.13   368.3 2821.42   469.7 2819.74   598.2 2820.65
   638.1 2820.66   655.1 2819.89   740.5 2822.31   766.8 2819.77   774.7  2818.2
   782.1  2816.1     791 2815.65     818 2815.86   848.6 2818.21   865.7 2824.41
   869.2 2826.27   879.4 2834.46   885.7  2837.2   914.1 2842.66   976.8  2852.4
     987 2854.86   997.3 2855.77  1017.7 2861.02  1033.1 2863.12    1047 2866.03
#Mann= 9 ,-1,0
       0      .1       0     110     .08       0     490      .1       0
     570     .07       0     730      .1       0   774.7    .045       0
   848.6      .1       0     880     .12       0     990      .1       0
Bank Sta=774.7,848.6
XS Rating Curve= 0 ,0
Exp/Cntr=0.3,0.1

Type RM Length L Ch R = 1 ,89005   ,219.7,219.7,219.7
XS GIS Cut Line= 3
2364352.77553253680058.6872515282364817.57591561679819.890724444
2365205.62027212679585.358421058
#Sta/Elev= 30
       0 2827.22   187.1 2825.82   206.2 2823.05   232.4 2822.84   242.2 2823.97
   251.2 2822.68     372 2821.55   381.6 2820.37   417.5 2820.18   435.5 2818.83
   535.2 2819.74   567.7 2821.21   575.9 2820.19   651.5 2817.54   689.2 2818.96
   691.82820.539   698.5  2825.5   712.5 2843.34   715.8 2846.02   735.9 2858.16
   749.9 2868.65   765.3 2876.72     792 2884.91     806 2891.18   829.4 2897.28
   852.7 2905.61   891.3 2915.33   918.2  2924.4   928.4 2926.65     976  2941.4
#Mann= 8 ,-1,0
       0      .1       0      80     .08       0     190      .1       0
     280     .08       0     300      .1       0     520     .12       0
   575.9    .045       0   691.8      .1       0
Bank Sta=575.9,691.8
XS Rating Curve= 0 ,0
Exp/Cntr(USF)=0,0
Exp/Cntr=0.3,0.1

Type RM Length L Ch R = 1 ,88786   ,201,201,201
XS GIS Cut Line= 3
2364427.00261789680240.3152861372364839.37718957680047.911572273
2365320.76433294      679761.018
#Sta/Elev= 30
       0  2826.3   363.2 2823.61   382.5 2824.86   385.5 2824.62   394.1 2820.81
   398.6  2820.3   491.6 2820.42   513.1 2816.88   530.7 2819.11   538.5 2816.54
   544.5 2814.95     605 2814.67   612.3 2816.64     619 2817.87   670.6  2816.9
   688.1 2819.47   707.4 2819.03   721.4 2821.12   758.7 2819.73   763.3 2822.48
   786.6 2843.72   822.3 2861.98   842.5 2874.38   877.8 2890.32     917 2900.73
   952.6 2904.68   963.5 2907.33     977 2907.82   991.7 2909.87  1015.4 2910.82
#Mann= 7 ,-1,0
       0     .08       0     320      .1       0     430     .12       0
   538.5    .045       0   612.3      .1       0  655.05     .12       0
  775.05      .1       0
Bank Sta=538.5,612.3
XS Rating Curve= 0 ,0
Exp/Cntr=0.3,0.1

Type RM Length L Ch R = 1 ,88585   ,266.8,266.8,266.8
XS GIS Cut Line= 3
 2364625.6858492680271.8984364242364992.40908722680169.557067674
2365516.90860207680011.780790851
#Sta/Elev= 30
       0 2824.08   152.1 2823.05   189.5 2824.74   218.5 2818.72   276.7 2819.48
   318.2 2819.07   330.7 2817.84   367.9 2819.56   388.8 2818.18     413 2818.57
   422.32815.564   426.4 2814.24   455.7    2814   468.2 2815.61   483.6 2815.81
   501.6 2814.09   520.9 2814.39   555.9 2820.11   668.7  2817.9   681.2 2821.38
   697.9 2832.55   706.3 2836.38   731.4 2839.41   743.9 2839.64   756.4 2842.13
   781.5 2844.91   814.9 2852.43   827.4 2854.22   844.1 2858.31   928.5 2883.56
#Mann= 8 ,-1,0
       0     .08       0     160      .1       0     200     .12       0
     300      .1       0   422.3    .045       0   468.2      .1       0
  520.74     .12       0  610.74      .1       0
Bank Sta=422.3,468.2
XS Rating Curve= 0 ,0
Exp/Cntr(USF)=0,0
Exp/Cntr=0.3,0.1

Type RM Length L Ch R = 1 ,88318   ,214.4,214.4,214.4
XS GIS Cut Line= 3
2364334.35170172680377.8366159382365087.32896016680368.946801328
2365928.00670227680319.600198672
#Sta/Elev= 30
       0 2827.43   141.8 2824.38   417.9 2821.82   493.9 2823.93   525.9 2823.03
   541.9 2819.01   557.9  2817.7   609.9 2818.18   637.9 2816.78   685.9 2819.15
   725.9 2816.47   785.9 2817.71     838 2815.44     850 2813.29   882.3 2813.29
   896.82815.519   914.2 2818.31   930.2 2817.02   970.2 2818.54  1054.4 2817.86
  1270.8 2820.71  1298.8 2832.05  1362.9 2848.94    1403 2854.32  1439.1 2857.08
  1471.1 2853.94  1486.3 2855.02  1499.2 2857.38  1511.2  2862.2  1595.2 2873.91
#Mann= 6 ,-1,0
       0     .08       0     380      .1       0     838    .045       0
   896.8      .1       0  973.03     .08       0 1273.03      .1       0
Bank Sta=838,896.8
XS Rating Curve= 0 ,0
Exp/Cntr=0.3,0.1

Type RM Length L Ch R = 1 ,88103   ,476.5,476.5,476.5
XS GIS Cut Line= 2
2364601.31252657680464.9931172482365934.91011009680716.791262387
#Sta/Elev= 30
       0 2822.31   112.8  2821.9   161.7 2823.45   218.7 2821.97   230.9 2822.96
   279.4 2819.38   291.9 2816.53   381.5 2817.23   405.9 2814.89   438.5 2816.33
   454.8  2814.8   511.7 2817.11     528 2816.67   536.2 2814.75   560.7 2812.97
   587.9 2814.76   678.6 2818.49   760.1 2818.28     870 2821.51   882.2 2820.08
     910 2822.68  1028.7 2825.88  1040.9 2827.87    1102 2827.15  1134.6 2829.25
  1149.7 2828.89  1199.7 2832.58  1310.6 2834.13  1324.3 2836.27  1357.2  2838.6
#Mann= 7 ,-1,0
       0     .08       0     220     .12       0     420      .1       0
   536.2    .045       0   587.9      .1       0     620     .08       0
    1020      .1       0
Bank Sta=536.2,587.9
XS Rating Curve= 0 ,0
Exp/Cntr(USF)=0,0
Exp/Cntr=0.3,0.1

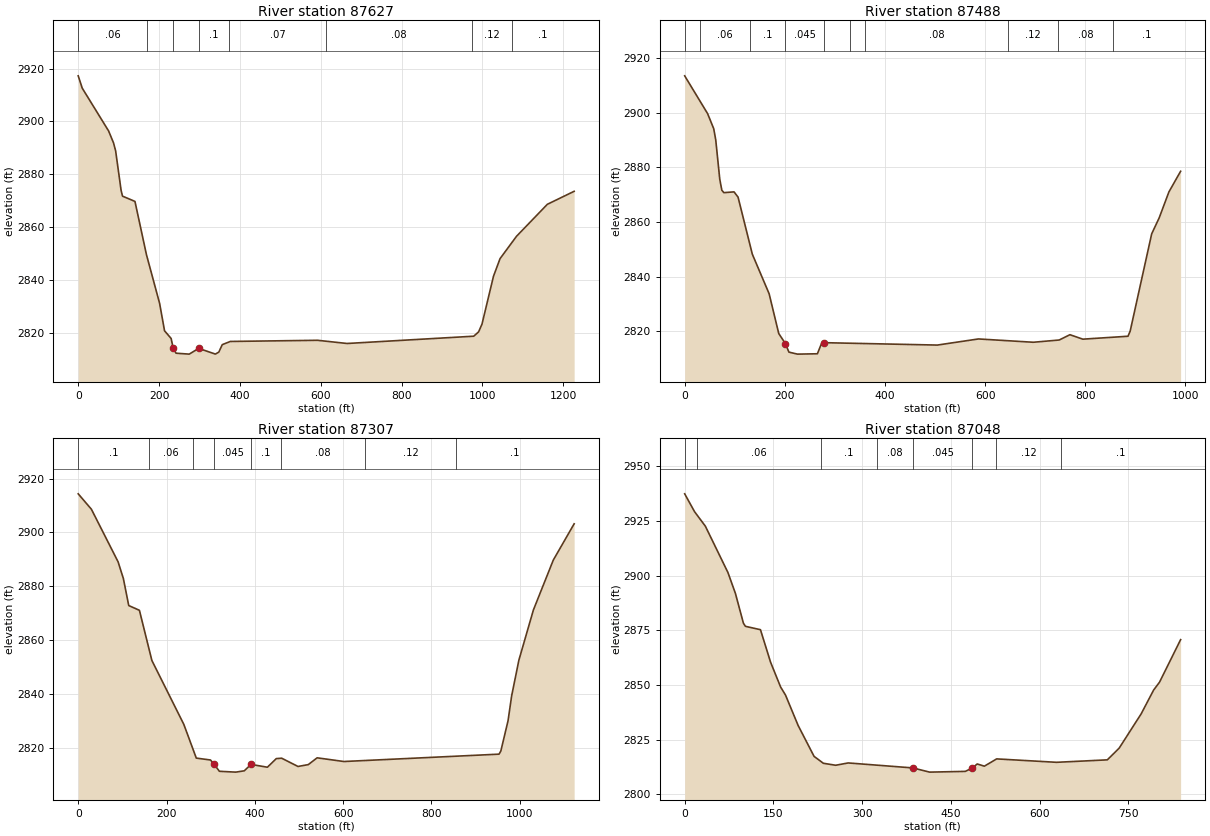
Type RM Length L Ch R = 1 ,87627   ,139.1,139.1,139.1
XS GIS Cut Line= 4
2364550.35579554680875.6511104082364730.93861535680841.106951486
2365629.40765388681009.0134571422365758.45231325681013.164626046
#Sta/Elev= 30
       0 2917.29      10 2912.61    75.2 2896.41    87.4 2891.89    92.6 2888.86
   106.2 2873.83   109.6 2871.72   140.4 2869.72   168.8 2849.58   201.4 2831.11
   213.6 2820.71   229.9 2817.81   235.12814.093   242.1 2812.23   274.6 2811.88
   298.1 2814.05   339.3  2811.9   347.9 2812.65   356.4 2815.47   376.4 2816.68
     592 2817.12   665.3 2815.91   978.6 2818.67   990.7 2820.33     999 2823.25
  1027.4 2841.36  1043.7 2848.06  1084.4 2856.51  1160.7 2868.63    1227 2873.55
#Mann= 8 ,-1,0
       0     .06       0     170      .1       0   235.1    .045       0
   298.1      .1       0  373.86     .07       0  613.86     .08       0
  973.86     .12       0 1073.86      .1       0
Bank Sta=235.1,298.1
XS Rating Curve= 0 ,0
Exp/Cntr=0.3,0.1

Type RM Length L Ch R = 1 ,87488   ,181.3,181.3,181.3
XS GIS Cut Line= 3
2364591.10099008680954.7861154162364971.59596496681021.932287453
2365533.94515577681242.955103741
#Sta/Elev= 30
       0 2913.44    45.8 2899.62      58 2894.12      62 2890.09    70.1 2875.63
    74.2 2871.62    78.3 2870.72    98.6 2871.01   106.6  2869.1   135.1 2848.23
   168.7 2833.75   187.9 2819.21   201.32815.498   208.2 2812.41   225.3 2811.68
   265.1 2811.81   273.2 2815.51   277.3 2815.87   504.6 2814.99   586.8 2817.23
   696.4 2816.02     748 2816.84   769.5 2818.78   795.3 2817.15   885.5 2818.22
   889.8 2820.06   932.8 2855.66   947.8  2861.5   967.2 2870.98   990.6 2878.54
#Mann= 10 ,-1,0
       0      .1       0      30     .06       0     130      .1       0
   201.3    .045       0   277.3     .08       0     330     .07       0
     360     .08       0  646.37     .12       0  746.37     .08       0
  856.37      .1       0
Bank Sta=201.3,277.3
XS Rating Curve= 0 ,0
Exp/Cntr(USF)=0,0
Exp/Cntr=0.3,0.1

Type RM Length L Ch R = 1 ,87307   ,258.9,258.9,258.9
XS GIS Cut Line= 3
2364462.49388217681135.9356333882365122.86756304681211.308482819
2365570.22001312681311.609348618
#Sta/Elev= 30
       0 2914.33    29.9  2908.6    90.3 2889.09   102.3 2882.88   114.4 2872.86
   138.6  2871.1   166.8 2852.49   239.2 2828.74   267.4 2816.24   299.6 2815.53
   307.7 2813.98   319.7 2811.34   356.8 2811.03   376.1 2811.52   391.3  2813.9
   428.4 2812.85   448.6 2816.05   460.7  2816.2   497.7 2813.13     521 2813.82
   541.1 2816.34   601.6 2814.97     953  2817.7   957.1 2818.87   973.4  2830.1
   981.6 2839.38     998 2852.63  1030.8 2871.21  1075.9 2889.75  1123.1  2903.2
#Mann= 8 ,-1,0
       0      .1       0     160     .06       0     260      .1       0
   307.7    .045       0   391.3      .1       0     460     .08       0
     650     .12       0  854.66      .1       0
Bank Sta=307.7,391.3
XS Rating Curve= 0 ,0
Exp/Cntr=0.3,0.1

Type RM Length L Ch R = 1 ,87048   ,234.8,234.8,234.8
XS GIS Cut Line= 4
 2364407.2030533681323.6368926572364686.39910281681421.107702842
 2364905.5658544681442.393453144 2365164.8609848681633.850684531
#Sta/Elev= 30
       0  2937.4    16.8 2929.19    34.9 2922.64    73.1 2901.42    85.8 2891.82
    99.3 2878.21   102.7 2876.81   128.1 2875.26   145.1 2860.46   162.1 2849.08
   170.5 2845.32   191.7  2831.5   218.7 2817.33   234.4 2814.18   255.2 2813.27
   276.4 2814.33   385.5 2812.06   414.1 2810.13   474.3 2810.47   486.4 2812.04
   494.4 2813.87   506.5 2812.85   527.3 2816.18   628.5 2814.62   714.3 2815.74
   734.3 2821.08   771.5 2836.77   792.6 2847.67   802.6 2851.29   838.2 2870.71
#Mann= 8 ,-1,0
       0      .1       0      20     .06       0     230      .1       0
  325.72     .08       0   385.5    .045       0   486.4      .1       0
  525.92     .12       0  635.92      .1       0
Bank Sta=385.5,486.4
XS Rating Curve= 0 ,0
Exp/Cntr(USF)=0,0
Exp/Cntr=0.3,0.1