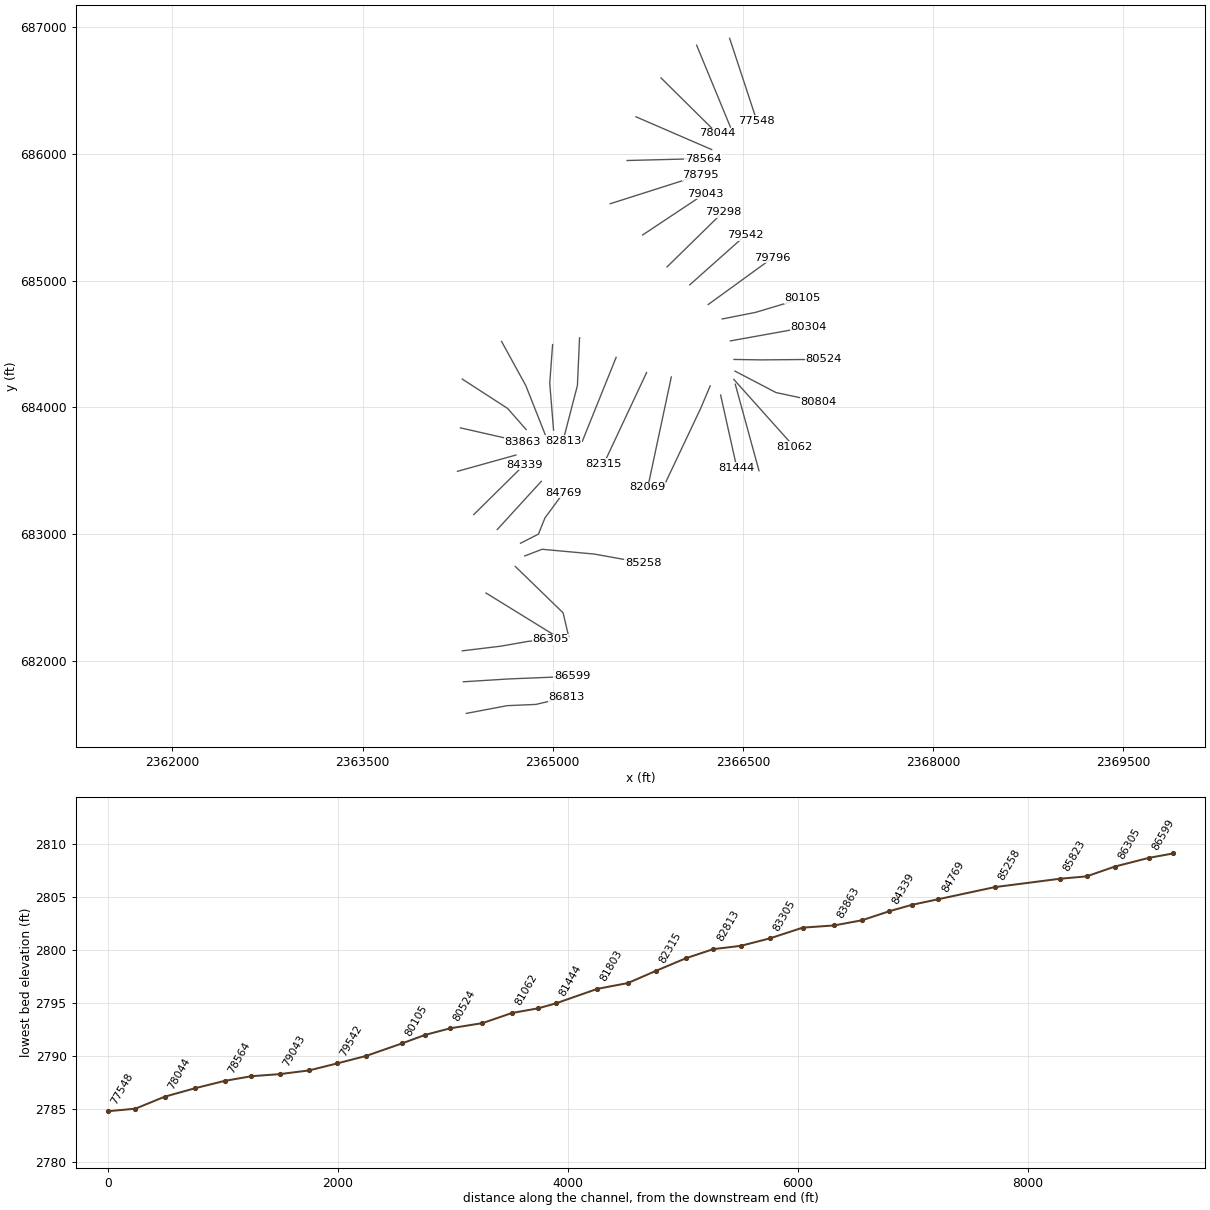
HEC-RAS study LAURELFK.prj: LAURELFK

--- LAURELFK.g01 (geometry) --- (continued)

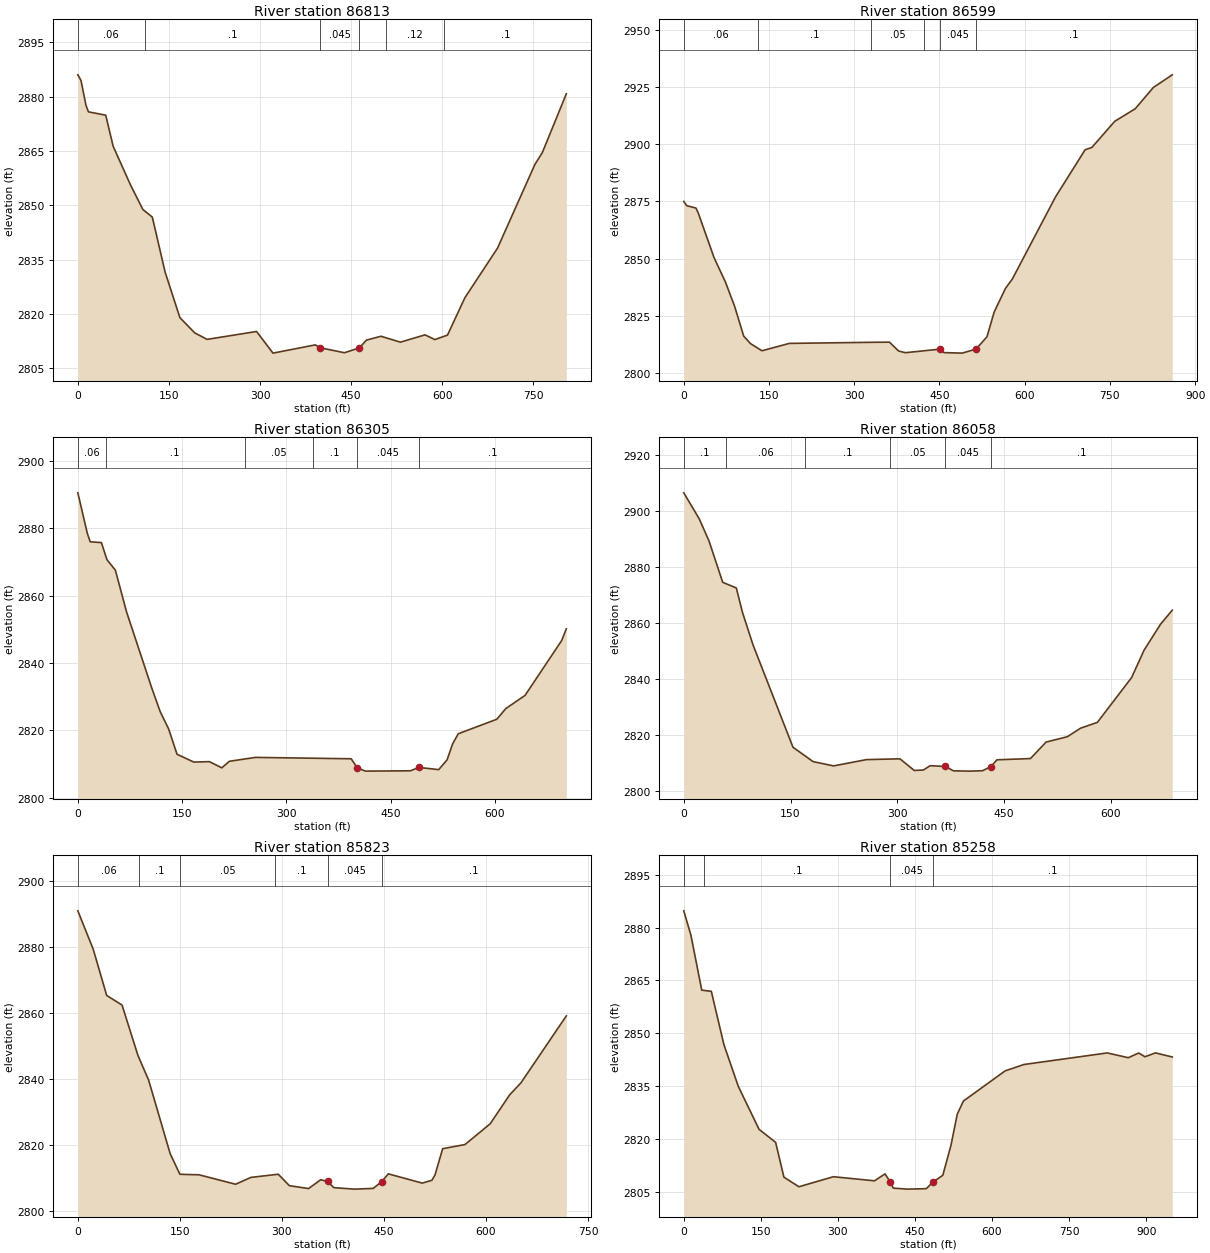
Type RM Length L Ch R = 1 ,86813   ,213.4,213.4,213.4
XS GIS Cut Line= 4
2364319.07819967681586.9901505692364640.98475122681647.933816694
2364866.62398342681657.6203112952365110.61256791681714.794549919
#Sta/Elev= 30
       0 2886.02     5.2 2884.47    13.3 2877.68    17.4  2875.8    45.9 2874.87
    58.1  2866.3    86.6 2855.64     107 2848.83   122.6 2846.71   143.6 2831.56
     168 2818.94   192.5 2814.72   212.8 2812.94   294.2 2815.12   321.2 2809.14
   390.9 2811.42   398.9 2810.62   438.9 2809.25   463.5 2810.59     475 2812.73
     499  2813.8     531 2812.17   571.5 2814.19   587.7 2812.88   608.5 2814.12
   637.2 2824.46   690.9 2838.16   752.3 2861.24   764.6 2864.54   804.1 2880.77
#Mann= 6 ,-1,0
       0     .06       0     110      .1       0   398.9    .045       0
   463.5      .1       0  507.62     .12       0  603.47      .1       0
Bank Sta=398.9,463.5
XS Rating Curve= 0 ,0
Exp/Cntr=0.3,0.1

Type RM Length L Ch R = 1 ,86599   ,294.6,294.6,294.6
XS GIS Cut Line= 3
2364294.83964182681836.1924127372364657.42897082681858.854245799
2365153.47131674 681878.99809741
#Sta/Elev= 30
       0 2874.96     5.3 2873.12    21.4 2872.09    25.4 2869.98    53.4 2850.38
    73.5 2839.67    89.5 2829.16   105.5 2816.14   117.6 2812.85   137.6 2809.75
   185.7 2812.97     330 2813.45     362 2813.51   378.1 2809.63   390.1 2808.91
   450.1 2810.44   458.1 2808.94   490.1 2808.72   514.4  2810.5   533.6 2815.85
   546.2 2826.63   566.2 2837.02   578.2 2841.07   654.3 2876.98   706.3 2897.53
   718.3 2898.58   758.4 2909.97   794.4 2915.44   826.4 2924.75   859.7 2930.28
#Mann= 6 ,-1,0
       0     .06       0     130      .1       0     330     .05       0
   423.3      .1       0   450.1    .045       0   514.4      .1       0
Bank Sta=450.1,514.4
XS Rating Curve= 0 ,0
Exp/Cntr(USF)=0,0
Exp/Cntr=0.3,0.1

Type RM Length L Ch R = 1 ,86305   ,246.7,246.7,246.7
XS GIS Cut Line= 4
 2364286.5455237682080.2206202582364592.15833235682117.263142773
2364806.80024487682155.2251540642364982.97415061682170.707560576
#Sta/Elev= 30
       0 2890.59    13.7 2878.51    17.8 2876.04    33.9  2875.8    41.9 2870.72
      54 2867.61    70.1  2855.2   106.2 2832.69   118.5 2825.55   130.6 2820.45
   142.7 2812.91   166.8 2810.59   189.2 2810.72   207.1 2808.88   217.9 2810.82
   255.5 2811.98   393.2 2811.57   401.7 2808.96   413.5  2807.9   478.5    2808
   490.7    2809   519.1 2808.34   531.2 2811.27   539.2 2816.03   547.3 2819.01
   602.7 2823.31   615.5 2826.47   643.3 2830.39   695.9 2846.67   702.7 2850.18
#Mann= 6 ,-1,0
       0     .06       0      40      .1       0     240     .05       0
  337.85      .1       0   401.7    .045       0   490.7      .1       0
Bank Sta=401.7,490.7
XS Rating Curve= 0 ,0
Exp/Cntr=0.3,0.1

Type RM Length L Ch R = 1 ,86058   ,234.8,234.8,234.8
XS GIS Cut Line= 2
2364473.61632487682536.1912562232365057.78802159682176.119908674
#Sta/Elev= 30
       0 2906.46    21.8 2897.13    35.4 2889.29    54.7 2874.47    73.8 2872.45
    82.5 2863.69    97.2 2852.16   153.4 2815.51   181.6 2810.38   210.4 2808.84
   256.7 2811.09   303.7 2811.37   323.8  2807.2   336.6 2807.37     346 2808.91
   367.4 2808.63   378.9 2807.07   402.1 2806.97   419.7 2807.11   431.4  2808.6
     440 2811.02     487 2811.46   508.9 2817.35   538.7 2819.26   557.5 2822.33
     581  2824.4   629.1 2840.42   646.7 2850.26   669.8 2859.51   686.2 2864.51
#Mann= 6 ,-1,0
       0      .1       0      60     .06       0     170      .1       0
     290     .05       0   367.4    .045       0   431.4      .1       0
Bank Sta=367.4,431.4
XS Rating Curve= 0 ,0
Exp/Cntr(USF)=0,0
Exp/Cntr=0.3,0.1

Type RM Length L Ch R = 1 ,85823   ,565.3,565.3,565.3
XS GIS Cut Line= 3
2364704.73619368682745.6784159952365081.44674928682380.074681028
2365125.96003475682192.235180029
#Sta/Elev= 30
       0 2891.08    22.6 2879.45    42.4 2865.43      65 2862.52    88.4 2847.22
   104.1 2839.74   135.7 2817.49     150 2811.24   178.2 2811.08   231.9 2808.22
   254.5  2810.3   294.6 2811.25   310.9 2807.79   339.2 2806.91   356.8 2809.57
   367.1  2809.1   376.2 2807.19   406.1 2806.74     434 2806.95   446.9 2809.04
   456.3 2811.37   506.3 2808.56   520.4 2809.42     525 2811.04   536.2 2818.99
     569 2820.25   606.1 2826.54   634.8 2835.34   651.3 2838.95     718 2859.24
#Mann= 6 ,-1,0
       0     .06       0      90      .1       0     150     .05       0
     290      .1       0   367.1    .045       0   446.9      .1       0
Bank Sta=367.1,446.9
XS Rating Curve= 0 ,0
Exp/Cntr=0.3,0.1

Type RM Length L Ch R = 1 ,85258   ,488.7,488.7,488.7
XS GIS Cut Line= 4
2364779.20025729682828.9469699692364915.97553509682881.345205947
2365326.87507403682843.6932344622365712.42036079682774.324816976
#Sta/Elev= 30
       0 2884.72    13.9 2877.83      35 2862.27    53.6 2861.94    78.1 2846.86
   106.2 2835.01   146.5 2822.88   178.8 2819.19   194.9 2809.34   224.1 2806.62
   291.3 2809.46   371.3  2808.3   391.7 2810.26  401.81    2808   407.8 2806.23
   435.9 2805.95     472 2806.08   485.3 2807.97   504.2 2809.87   520.2 2818.42
   532.3 2827.16   544.3 2830.88   625.4 2839.41     662 2841.22   824.2  2844.5
   865.2 2843.15   885.5 2844.47   897.7 2843.42   918.1 2844.51   950.8 2843.35
#Mann= 4 ,-1,0
       0     .06       0      40      .1       0  401.81    .045       0
   485.3      .1       0
Bank Sta=401.81,485.3
XS Rating Curve= 0 ,0
Exp/Cntr=0.3,0.1

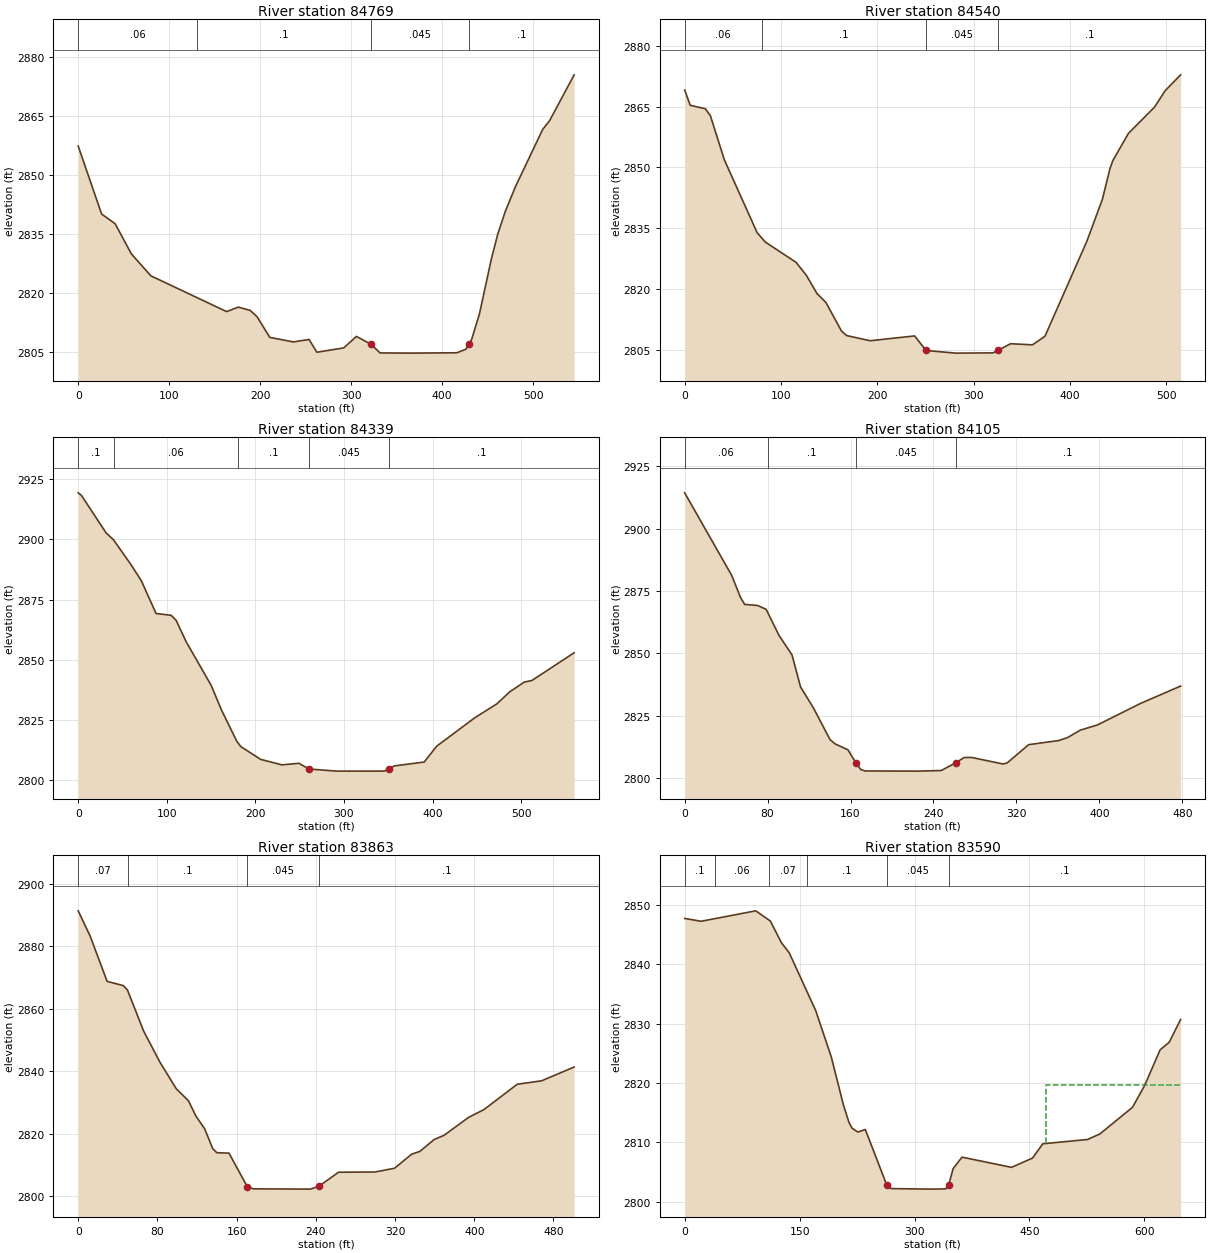
Type RM Length L Ch R = 1 ,84769   ,229.7,229.7,229.7
XS GIS Cut Line= 4
2364745.79402258682928.9799640482364886.92580575683000.771870999
2364938.53008329683128.5753746652365085.91585986683329.009475204
#Sta/Elev= 30
       0 2857.43    25.7 2840.17    40.6 2837.69    58.4 2830.04    79.8 2824.46
   163.1 2815.36     176 2816.51     189 2815.66   196.5 2814.08   210.5 2808.82
   236.4 2807.66   253.7 2808.28   262.3 2805.04   291.8 2806.14   305.7 2809.06
   321.7 2807.08   331.7 2804.86   366.3 2804.81   416.1  2804.9     426  2805.8
  429.72 2807.08   432.3 2808.26   440.9 2814.76   454.2 2828.92     461    2835
   469.4 2840.87   480.6 2847.17   510.4 2861.65   518.1 2863.92     545 2875.54
#Mann= 4 ,-1,0
       0     .06       0     130      .1       0   321.7    .045       0
  429.72      .1       0
Bank Sta=321.7,429.72
XS Rating Curve= 0 ,0
Exp/Cntr=0.3,0.1

Type RM Length L Ch R = 1 ,84540   ,200.9,200.9,200.9
XS GIS Cut Line= 2
2364562.17571797683036.9236268442364909.65715826683417.138826002
#Sta/Elev= 30
       0 2869.06     5.8 2865.31    21.4 2864.47    26.7 2862.76    41.2  2851.9
    75.2 2833.97    83.7 2831.64   115.6 2826.66   126.2 2823.51   137.5 2818.93
   146.7 2816.76   162.9 2809.71   168.3  2808.6   192.7 2807.33   238.8 2808.52
   250.7 2804.93   281.6 2804.28   320.1 2804.34   325.5 2804.96   338.5  2806.6
   361.2 2806.32   374.2 2808.43   417.8 2831.87   433.9 2842.21   441.7  2849.7
   444.7  2851.7   460.9  2858.4     488 2864.86   498.9 2868.87   515.1 2872.82
#Mann= 4 ,-1,0
       0     .06       0      80      .1       0   250.7    .045       0
   325.5      .1       0
Bank Sta=250.7,325.5
XS Rating Curve= 0 ,0
Exp/Cntr(USF)=0,0
Exp/Cntr=0.3,0.1

Type RM Length L Ch R = 1 ,84339   ,233.2,233.2,233.2
XS GIS Cut Line= 2
2364377.50798145 683155.46859193 2364775.8836645 683548.88492418
#Sta/Elev= 30
       0 2919.41     3.7 2918.31    31.4 2902.79    39.9 2899.85    59.4 2889.64
    71.2 2882.89    87.9 2869.21   104.9 2868.47   110.6 2866.35   121.8 2857.52
   150.2 2839.27   161.8 2829.03   178.9 2816.19   183.6 2813.85   206.1 2808.53
   230.1 2806.26   249.2 2806.93   260.5 2804.55   291.6 2803.66   345.3 2803.67
     351 2804.52   356.7 2805.82   390.6 2807.44   404.7 2814.03   447.9  2825.9
   472.6 2831.63   487.2 2836.65   503.7 2840.71   512.2 2841.36   559.9 2852.89
#Mann= 5 ,-1,0
       0      .1       0      40     .06       0     180      .1       0
   260.5    .045       0     351      .1       0
Bank Sta=260.5,351
XS Rating Curve= 0 ,0
Exp/Cntr=0.3,0.1

Type RM Length L Ch R = 1 ,84105   ,242.2,242.2,242.2
XS GIS Cut Line= 2
2364248.48611838683496.1729714332364709.27672398683624.590025453
#Sta/Elev= 30
       0 2914.39    45.4 2881.26    53.7 2872.59    57.8 2869.66    70.3 2869.24
    78.6 2867.68      91 2857.23   103.5 2849.44   111.8 2836.56     124 2828.32
   140.2 2815.48     145 2813.77   157.5 2811.36   165.1 2806.18   169.9 2803.46
   174.1 2802.89   223.9 2802.82   247.4 2803.06   261.3 2806.11   269.6 2808.28
   276.6 2808.32     307 2805.69   311.1 2806.11   331.8 2813.43   360.8 2815.08
   369.2 2816.25   381.7 2819.26   398.3 2821.35   439.8 2829.97   478.4 2836.92
#Mann= 4 ,-1,0
       0     .06       0      80      .1       0   165.1    .045       0
   261.3      .1       0
Bank Sta=165.1,261.3
XS Rating Curve= 0 ,0
Exp/Cntr(USF)=0,0
Exp/Cntr=0.3,0.1

Type RM Length L Ch R = 1 ,83863   ,273.5,273.5,273.5
XS GIS Cut Line= 2
2364271.67510967683838.984482264 2364760.1610153683728.040816139
#Sta/Elev= 30
       0  2891.3      12 2883.26    29.2 2868.75    45.4 2867.41    49.7 2866.02
    66.1 2852.84    82.5 2842.94      99 2834.43   111.3  2830.6   118.9 2825.69
   127.7 2821.63   135.9 2815.26     140 2813.97   152.3 2813.83   170.7 2803.15
   176.9 2802.42   234.3 2802.33   242.9 2803.21     263 2807.73   299.9 2807.81
   319.5 2809.01   336.9 2813.52   345.1 2814.39   359.6 2818.21   369.4 2819.51
   394.3 2825.27   409.7 2827.74   443.5 2835.87   468.1 2836.96   500.9 2841.37
#Mann= 4 ,-1,0
       0     .07       0      50      .1       0   170.7    .045       0
   242.9      .1       0
Bank Sta=170.7,242.9
XS Rating Curve= 0 ,0
Exp/Cntr=0.3,0.1

Type RM Length L Ch R = 1 ,83590   ,284.3,284.3,284.3
XS GIS Cut Line= 3
2364286.25584015684223.8696108822364643.80920625683992.215317355
2364789.85213043683826.028541564
#Sta/Elev= 30
       0 2847.75    21.4 2847.27    92.8 2849.03   111.9  2847.3   126.2 2843.67
   136.4 2841.97   171.1 2832.19   191.3 2824.43   207.2 2816.31   214.5 2813.34
   218.3 2812.42     226 2811.74   235.8 2812.17   263.6 2802.85   269.8 2802.21
   321.3 2802.12   340.7 2802.16   344.6 2802.82   350.4 2805.58     362 2807.51
   426.6 2805.79     454 2807.35   467.4 2809.76   525.9 2810.49   541.8 2811.41
   584.5 2815.91   600.5 2819.63   620.5 2825.59   632.5 2826.89   647.3 2830.72
#Mann= 6 ,-1,0
       0      .1       0      40     .06       0     110     .07       0
     160      .1       0   263.6    .045       0   344.6      .1       0
#XS Ineff= 2 , 0
                          472.15         2819.59
Permanent Ineff=
       F       F
Bank Sta=263.6,344.6
XS Rating Curve= 0 ,0
Exp/Cntr(USF)=0,0
Exp/Cntr=0.3,0.1

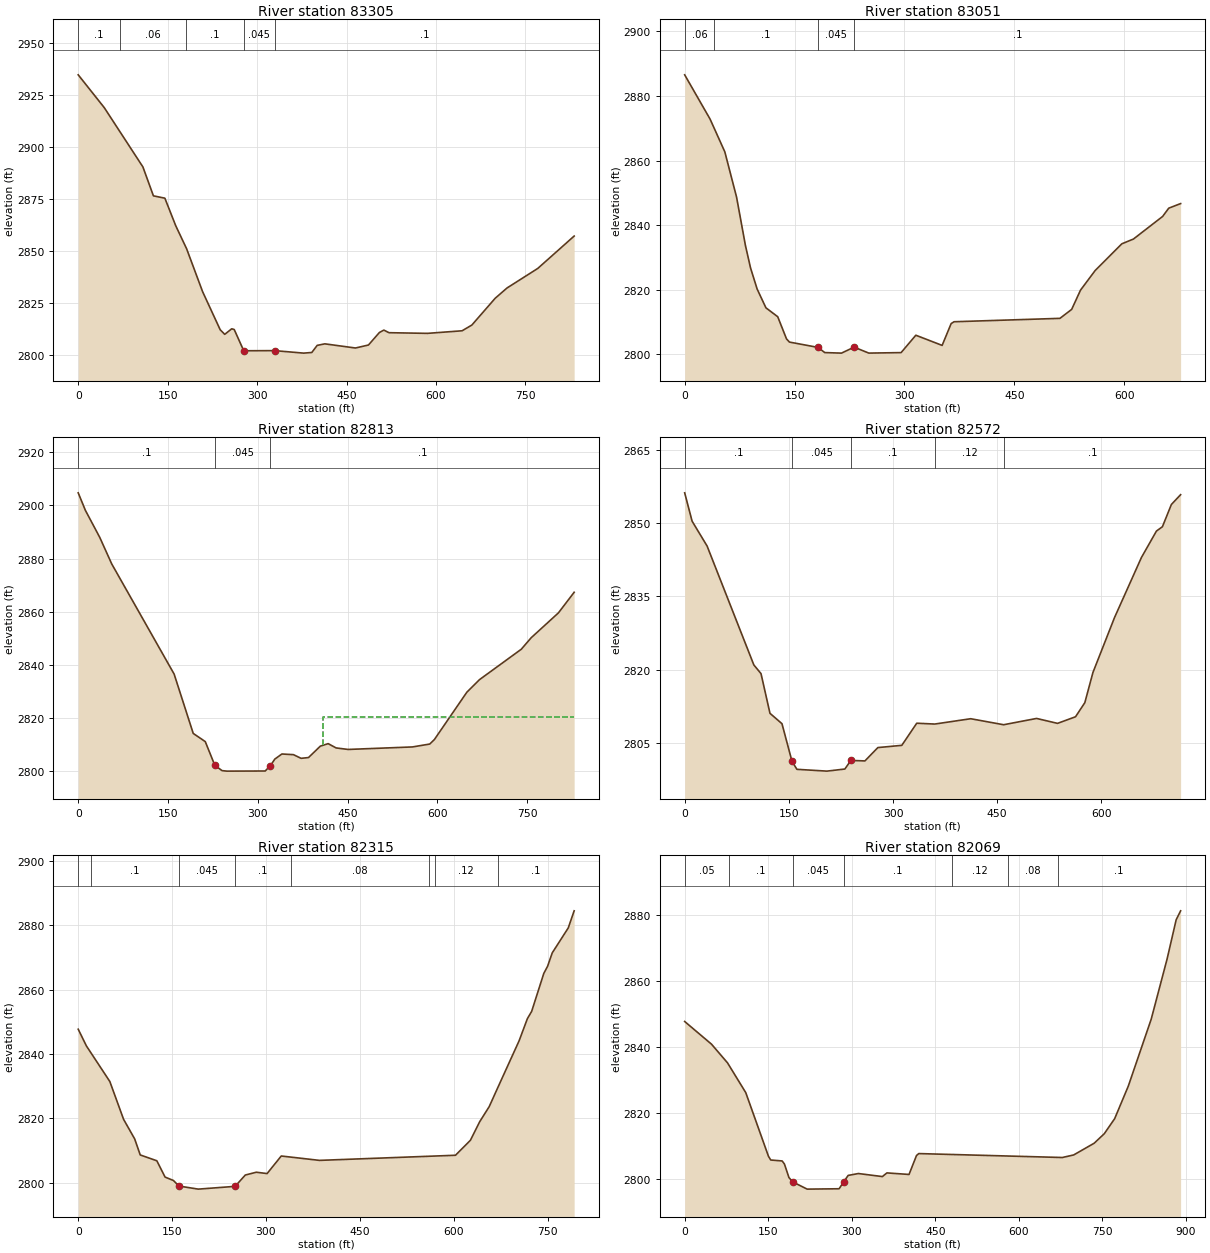
Type RM Length L Ch R = 1 ,83305   ,254,254,254
XS GIS Cut Line= 3
2364596.25647677684520.5388571092364787.49266706684172.344523227
2364947.26315292683768.438169333
#Sta/Elev= 30
       0 2934.88    43.7  2919.1   108.5  2890.6   126.1 2876.71   145.3 2875.59
   163.6  2862.3   181.8 2851.26   208.6 2830.64   238.1 2812.34   245.7 2810.14
   257.4 2812.81   261.6 2812.46   277.6 2802.24   329.4 2802.31     378 2801.11
   391.7 2801.42   400.7 2804.83   413.6 2805.57   464.9 2803.57   486.7 2805.01
     505 2811.01   512.5 2812.18   521.1 2810.93   585.6 2810.61   643.7 2811.85
   660.1 2814.61   699.2 2827.48     719 2832.41   770.6 2841.82   831.6 2857.38
#Mann= 5 ,-1,0
       0      .1       0      70     .06       0     180      .1       0
   277.6    .045       0   329.4      .1       0
Bank Sta=277.6,329.4
XS Rating Curve= 0 ,0
Exp/Cntr=0.3,0.1

Type RM Length L Ch R = 1 ,83051   ,238.8,238.8,238.8
XS GIS Cut Line= 3
2364998.84459089684495.8116076312364976.18275783684191.135852014
2365006.39853524683820.992578661
#Sta/Elev= 30
       0 2886.51    34.7  2872.8    54.8 2862.68    70.8  2848.7    82.9 2833.74
    89.9 2826.76    98.9 2820.23   110.9 2814.42     127 2811.66     139  2804.8
     143 2803.82     182 2802.17   191.2 2800.57     214  2800.4   231.3 2802.25
   251.3 2800.41   295.4 2800.56   315.5 2805.94   351.4 2802.79   363.7 2809.54
   367.7 2810.11   512.2 2811.16   528.2 2813.93   540.3  2819.9   560.3 2825.97
   596.7 2834.23   612.5  2835.7   652.4  2842.7   660.7 2845.25   676.9 2846.67
#Mann= 4 ,-1,0
       0     .06       0      40      .1       0     182    .045       0
   231.3      .1       0
Bank Sta=182,231.3
XS Rating Curve= 0 ,0
Exp/Cntr(USF)=0,0
Exp/Cntr=0.3,0.1

Type RM Length L Ch R = 1 ,82813   ,240.2,240.2,240.2
XS GIS Cut Line= 3
2365211.27851434684549.1349274312365194.52424283684173.725713272
2365081.02080919683735.627372746
#Sta/Elev= 30
       0 2904.69      12  2898.1      36 2887.94      56 2877.96   160.2 2836.57
   192.1 2814.26   212.2 2811.19   228.2 2802.26   240.2 2800.28   248.2 2800.09
   312.3 2800.14   321.1 2802.18   328.3  2804.6   340.2 2806.53   359.4 2806.28
   372.3  2804.9   384.6 2805.19   404.4 2809.48   417.5 2810.42   430.7 2808.81
   450.7 2808.24   558.2 2809.18   587.1 2810.27   594.8 2811.94   649.1 2829.75
   670.2 2834.47     740  2845.9   756.5 2850.21     802 2859.56   828.3 2867.31
#Mann= 3 ,-1,0
       0      .1       0   228.2    .045       0   321.1      .1       0
#XS Ineff= 2 , 0
                           409.4         2820.29
Permanent Ineff=
       F       F
Bank Sta=228.2,321.1
XS Rating Curve= 0 ,0
Exp/Cntr=0.3,0.1

Type RM Length L Ch R = 1 ,82572   ,257.9,257.9,257.9
XS GIS Cut Line= 2
2365499.92289971684395.0923495752365233.01686587683732.863227863
#Sta/Elev= 30
       0 2856.21    10.7  2850.4    32.3 2845.31    99.6 2820.96   109.9 2819.19
   122.8 2811.06   140.1 2808.93   154.52801.223   161.6 2799.59   204.8 2799.22
   230.6 2799.65   239.3 2801.41   259.5 2801.31   278.1 2804.04   312.6  2804.5
   334.1 2809.03     360 2808.86   411.8 2809.95   459.2 2808.72   506.6 2810.01
   536.8    2809   562.7 2810.35   576.1 2813.24   587.8 2819.43   618.8 2830.65
   657.6 2842.97   679.2 2848.38   687.8 2849.27   700.7 2853.82     714 2855.83
#Mann= 5 ,-1,0
       0      .1       0   154.5    .045       0   239.3      .1       0
     360     .12       0     460      .1       0
Bank Sta=154.5,239.3
XS Rating Curve= 0 ,0
Exp/Cntr(USF)=0,0
Exp/Cntr=0.3,0.1

Type RM Length L Ch R = 1 ,82315   ,245.1,245.1,245.1
XS GIS Cut Line= 2
  2365739.973164684274.8501528792365403.29951912 683557.51491522
#Sta/Elev= 30
       0 2847.72    13.1 2842.52    50.5 2831.48    72.5 2819.72    90.2 2813.65
    99.1 2808.66   125.6 2806.85   138.8 2801.78   152.1 2800.73   160.9    2799
   191.8 2798.04   250.7  2798.9     267 2802.42   284.6 2803.29   301.8 2802.87
   324.4 2808.33   385.5 2806.97   602.8 2808.56   626.6  2813.2   641.6 2819.02
   656.7 2823.67     670  2829.4   704.4 2844.09   717.7    2851   724.5 2853.25
   743.9 2865.05   749.9 2867.24   757.4 2871.43     783 2879.18   792.4 2884.49
#Mann= 8 ,-1,0
       0     .05       0      20      .1       0   160.9    .045       0
   250.7      .1       0     340     .08       0     560      .1       0
     570     .12       0     670      .1       0
Bank Sta=160.9,250.7
XS Rating Curve= 0 ,0
Exp/Cntr=0.3,0.1

Type RM Length L Ch R = 1 ,82069   ,266.2,266.2,266.2
XS GIS Cut Line= 2
2365935.14810573684240.3493370852365749.29589481683369.354373239
#Sta/Elev= 30
       0 2847.62    48.2 2840.75    76.9 2835.11   109.7 2826.09   150.5 2806.81
   154.6 2805.69     175 2805.41   179.1 2804.49   187.2  2800.4   193.9 2799.07
     220 2796.88   277.3 2796.99   285.5 2799.06   293.6 2801.03   311.9  2801.6
     355 2800.68   363.2 2801.79   402.9 2801.32   416.3 2807.05   420.4 2807.64
   678.1 2806.45   698.5 2807.22   735.4 2810.78   753.5 2813.65   772.2 2818.22
   796.7 2828.08   837.8 2848.33   866.2 2866.46   882.6  2878.4   890.6 2881.12
#Mann= 7 ,-1,0
       0     .05       0      80      .1       0   193.9    .045       0
   285.5      .1       0     480     .12       0     580     .08       0
     670      .1       0
Bank Sta=193.9,285.5
XS Rating Curve= 0 ,0
Exp/Cntr(USF)=0,0
Exp/Cntr=0.3,0.1

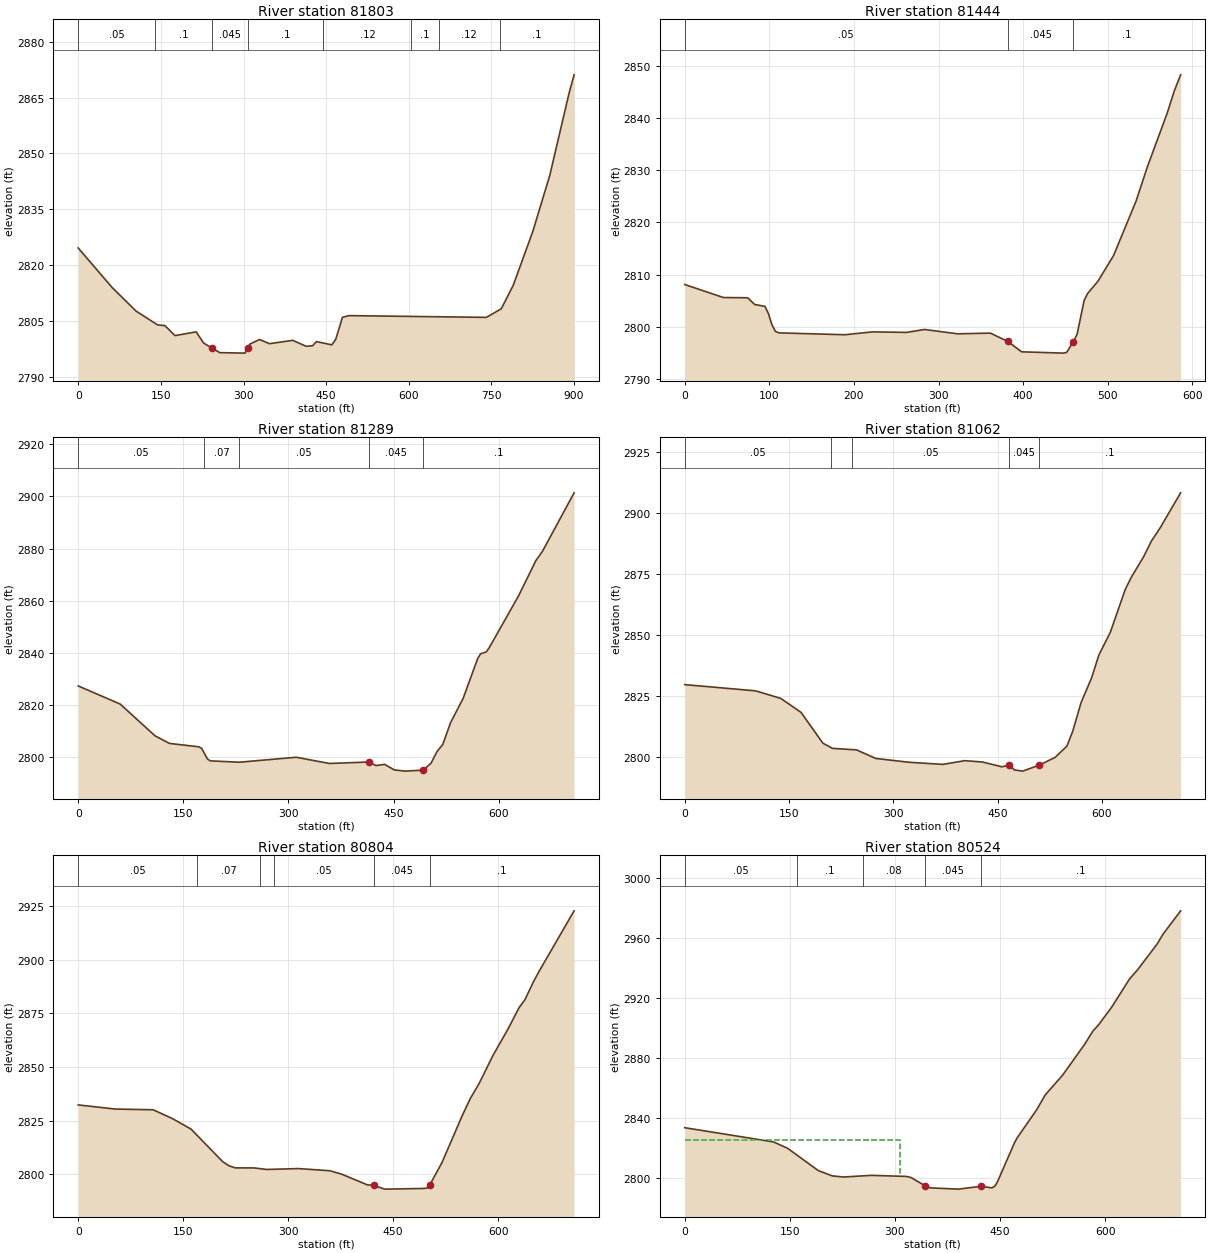
Type RM Length L Ch R = 1 ,81803   ,359.4,359.4,359.4
XS GIS Cut Line= 3
2366241.77763792684169.9696506372366165.76773454683990.593254342
2365864.08096039683353.239197365
#Sta/Elev= 30
       0 2824.59    61.7 2813.95   105.1 2807.62   144.2 2803.91   157.3 2803.73
   175.8 2801.04   214.1 2802.05   227.4 2799.08   242.22797.711   257.1 2796.46
   302.6 2796.33   308.2 2797.58   311.4 2798.74   329.1 2799.99   347.3 2798.87
   389.3 2799.77   413.6 2798.18   425.4 2798.31   432.3 2799.42   460.3 2798.56
   467.4 2800.05   479.6 2805.95   491.4 2806.41   740.8 2805.94   767.8 2808.24
   789.4 2814.51     825    2829   855.8 2844.07   890.9 2866.21     900 2871.14
#Mann= 8 ,-1,0
       0     .05       0     140      .1       0   242.2    .045       0
   308.2      .1       0  444.82     .12       0  604.82      .1       0
  654.82     .12       0  764.82      .1       0
Bank Sta=242.2,308.2
XS Rating Curve= 0 ,0
Exp/Cntr=0.3,0.1

Type RM Length L Ch R = 1 ,81444   ,154.5,154.5,154.5
XS GIS Cut Line= 2
2366323.98451172684097.8250061382366451.50327644683525.724254884
#Sta/Elev= 30
       0  2808.1    45.7 2805.61    74.4 2805.56    82.6 2804.28    94.9 2803.91
      99 2802.48   103.1 2800.38   107.2 2799.12   111.3 2798.84   189.2 2798.48
     222 2799.03   262.1 2798.93   283.4 2799.49   322.4 2798.66   361.3 2798.79
   381.8  2797.2   398.2 2795.21   447.4 2794.96   451.5 2795.11   459.4 2797.16
   463.8  2798.6     472    2805     476 2806.34   488.3 2808.71   506.9 2813.67
   533.4 2824.06   546.9 2830.68   570.2  2840.9   578.5 2845.12   586.1 2848.26
#Mann= 3 ,-1,0
       0     .05       0   381.8    .045       0   459.4      .1       0
Bank Sta=381.8,459.4
XS Rating Curve= 0 ,0
Exp/Cntr(USF)=0,0
Exp/Cntr=0.3,0.1

Type RM Length L Ch R = 1 ,81289   ,227.6,227.6,227.6
XS GIS Cut Line= 2
2366439.59593372684182.9636312752366626.84033225683500.492725022
#Sta/Elev= 30
       0 2827.22    59.9 2820.26   109.7 2808.04   130.4 2805.13   171.9 2803.84
   176.1 2803.27   184.4 2799.18   188.5 2798.43     230 2797.91   311.1 2799.82
   358.6 2797.43   415.12797.994   424.9 2796.63   437.4 2797.09   451.1 2794.96
   466.4 2794.49   492.42794.875   503.7  2797.6     512 2801.97   520.3 2804.74
   531.3 2813.03   549.4 2822.47   570.1 2837.73   574.2 2839.55   582.5 2840.32
   586.7 2841.96   628.2  2861.7   653.1 2875.33   662.7 2879.01   707.7 2901.41
#Mann= 5 ,-1,0
       0     .05       0     180     .07       0     230     .05       0
   415.1    .045       0   492.4      .1       0
Bank Sta=415.1,492.4
XS Rating Curve= 0 ,0
Exp/Cntr=0.3,0.1

Type RM Length L Ch R = 1 ,81062   ,257.5,257.5,257.5
XS GIS Cut Line= 2
2366428.04551561684221.273384491 2366903.6642342683689.699522533
#Sta/Elev= 30
       0  2829.6   102.1 2827.03   138.2 2823.93   167.3 2818.19   198.7 2805.54
   212.6  2803.4     247 2802.79   274.9 2799.25   322.2  2797.7   371.3 2796.82
   402.7 2798.34   427.9 2797.81   456.1 2795.84   467.1 2796.52   474.1 2794.54
   486.1 2794.05   510.1 2796.53   532.7 2799.69   549.7 2804.31   558.1 2810.43
   570.1  2822.2   585.2 2832.33   595.9 2841.89   612.1 2851.03   633.5 2868.58
   642.1 2873.59   660.1 2882.14   671.1 2888.49   684.1 2894.13   713.3 2908.41
#Mann= 5 ,-1,0
       0     .05       0     210     .07       0     240     .05       0
   467.1    .045       0   510.1      .1       0
Bank Sta=467.1,510.1
XS Rating Curve= 0 ,0
Exp/Cntr(USF)=0,0
Exp/Cntr=0.3,0.1

Type RM Length L Ch R = 1 ,80804   ,280.2,280.2,280.2
XS GIS Cut Line= 3
2366437.34533506684286.5570459842366760.88266612684117.505809714
2367096.84523721684045.554286017
#Sta/Elev= 30
       0 2832.32    52.8 2830.39     107 2830.06   134.1 2826.03   161.2 2821.07
   206.3 2805.94   215.3 2803.97   224.3    2803   251.4 2802.96   269.5 2802.25
   314.6 2802.66   359.7 2801.65   376.6 2800.04   413.4 2795.06     422 2794.88
   437.9 2793.09   495.2 2793.41   499.3 2793.71   502.42795.034   519.8 2805.46
   548.4 2827.06   560.1 2835.19   572.9  2842.3   592.7 2855.37   613.6 2867.33
   630.2 2877.73   638.4 2881.36   651.1 2890.07   658.8 2894.66   708.6 2922.73
#Mann= 6 ,-1,0
       0     .05       0     170     .07       0     260     .08       0
     280     .05       0     422    .045       0   502.4      .1       0
Bank Sta=422,502.4
XS Rating Curve= 0 ,0
Exp/Cntr=0.3,0.1

Type RM Length L Ch R = 1 ,80524   ,219.8,219.8,219.8
XS GIS Cut Line= 3
2366429.60669528684378.6118676812366643.75600939684375.157846485
2367137.29726019684379.379427946
#Sta/Elev= 30
       0 2833.57   126.6  2824.1   146.6 2819.91   190.6 2804.95   210.6 2801.44
   226.6 2800.68   266.6 2801.79   315.8 2801.07   322.6 2800.42   343.5 2794.69
   350.6 2793.44   390.6  2792.6   422.4 2794.46   438.6 2793.46   442.7 2794.66
   446.6 2797.79   470.4 2823.29   474.6 2826.93   502.2  2845.5   514.6  2855.5
   539.4 2868.69   570.6  2889.1   582.6  2898.1   590.6 2902.17   609.3 2913.96
   634.6 2932.64   646.6 2939.09   674.6 2956.36   682.6 2962.67   707.7 2978.23
#Mann= 5 ,-1,0
       0     .05       0     160      .1       0  254.18     .08       0
   343.5    .045       0   422.4      .1       0
#XS Ineff= 2 , 0
          307.38 2825.26
Permanent Ineff=
       F       F
Bank Sta=343.5,422.4
XS Rating Curve= 0 ,0
Exp/Cntr(USF)=0,0
Exp/Cntr=0.3,0.1

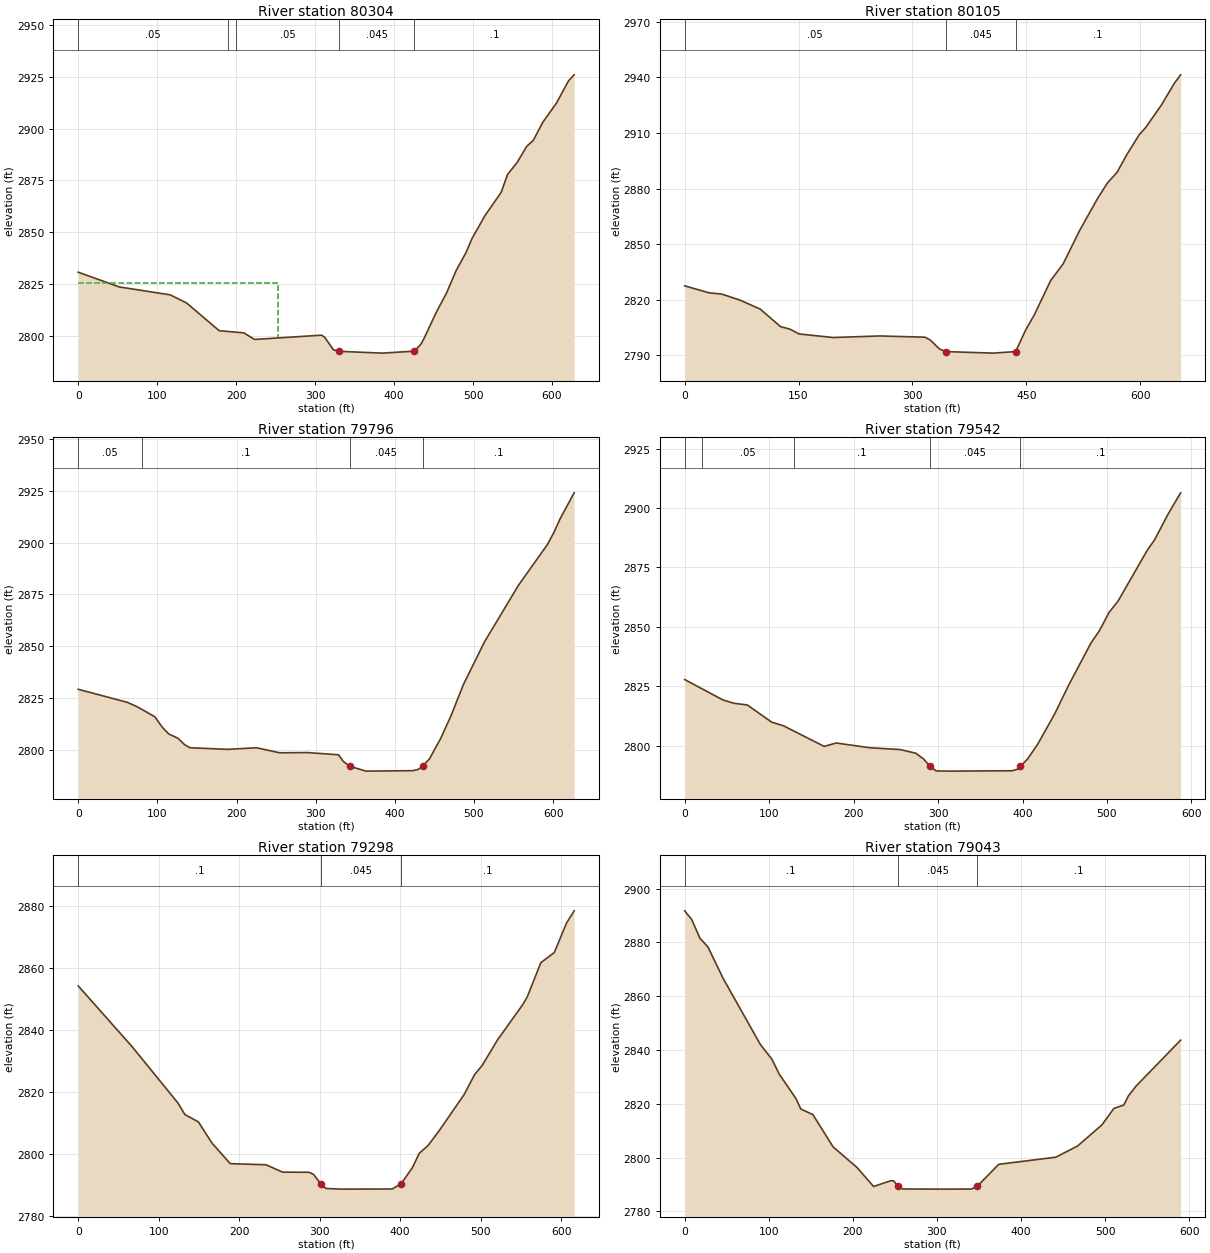
Type RM Length L Ch R = 1 ,80304   ,199.5,199.5,199.5
XS GIS Cut Line= 2
2366401.01187437684525.0361588282367019.22649031684636.024019922
#Sta/Elev= 30
       0 2830.89      52  2823.8   116.5    2820   137.2 2816.11   178.6 2802.75
   209.6 2801.73   223.4 2798.55     308  2800.6   312.1 2799.63   323.3 2793.55
   330.7 2792.83   385.1 2791.97   425.9 2792.92     434 2796.27   438.1 2799.13
   453.5 2811.62   466.5  2820.9   478.7 2831.74   490.9 2840.15     499 2847.29
   515.3 2858.18   535.6 2869.24   543.7 2877.86   555.9 2883.67   568.1 2891.48
   576.2 2894.19   588.4 2903.02   605.8 2912.28   620.9 2922.88   628.1 2925.82
#Mann= 5 ,-1,0
       0     .05       0     190      .1       0     200     .05       0
   330.7    .045       0   425.9      .1       0
#XS Ineff= 2 , 0
          252.52 2825.53
Permanent Ineff=
       F       F
Bank Sta=330.7,425.9
XS Rating Curve= 0 ,0
Exp/Cntr=0.3,0.1

Type RM Length L Ch R = 1 ,80105   ,308.4,308.4,308.4
XS GIS Cut Line= 3
2366336.34812301 684697.916938182366598.85373385684749.727256109
2366968.43400175684860.255934359
#Sta/Elev= 30
       0  2827.5    32.4 2823.69    48.7 2823.07    73.2 2819.74    99.5 2814.95
   126.2 2805.49   138.8 2804.11   150.7 2801.52   195.5  2799.6   256.7 2800.44
   316.4 2799.78   323.2 2798.36   335.7  2793.4   344.1    2792   406.4 2791.17
     436 2792.01     449  2803.5     461 2812.15   481.9 2830.21   498.6 2839.39
   520.5 2857.55   544.3 2874.94     557  2883.1   569.6 2888.79   582.1 2898.09
   598.8 2909.12   607.1 2912.88     628 2925.11   644.7 2936.64   653.3 2941.42
#Mann= 3 ,-1,0
       0     .05       0   344.1    .045       0     436      .1       0
Bank Sta=344.1,436
XS Rating Curve= 0 ,0
Exp/Cntr(USF)=0,0
Exp/Cntr=0.3,0.1

Type RM Length L Ch R = 1 ,79796   ,254.7,254.7,254.7
XS GIS Cut Line= 2
2366225.89962922684811.6660132812366733.10366242685179.531053125
#Sta/Elev= 30
       0 2829.39    62.1  2823.1    74.3 2821.01    96.7 2816.19   106.6 2810.95
   114.4  2807.9   125.9 2805.85   134.5 2802.69   141.2 2801.26   188.9 2800.47
   225.2 2801.25   254.7 2798.82   289.4 2798.93   328.9 2797.86   334.9 2794.67
   343.2 2792.32   363.5    2790   422.8 2790.22   429.5 2790.81   435.1 2792.38
   443.8 2795.89   458.1 2805.82   471.1 2816.72   486.7 2831.68   513.5 2852.32
   556.2 2879.39   592.7 2898.96   601.3 2905.04   608.9 2911.45   626.6 2923.91
#Mann= 4 ,-1,0
       0     .05       0      80      .1       0   343.2    .045       0
   435.1      .1       0
Bank Sta=343.2,435.1
XS Rating Curve= 0 ,0
Exp/Cntr=0.3,0.1

Type RM Length L Ch R = 1 ,79542   ,244.1,244.1,244.1
XS GIS Cut Line= 2
2366080.75055456684967.3305914142366519.41124636685357.634986483
#Sta/Elev= 30
       0 2827.83    44.9  2819.3    58.1 2817.86    74.2 2817.11   102.9 2809.92
   117.1 2808.34   165.2 2799.69   179.4 2801.12   218.7 2799.14   255.5 2798.34
   273.6 2796.82     283 2794.35   289.9 2791.47   297.6 2789.37   315.1 2789.28
   387.9 2789.44   393.9 2790.07   397.6 2791.26     406  2794.4     418 2800.62
   438.3  2813.5   454.3 2825.21   481.1 2843.23   491.1 2848.41   502.5 2856.08
   513.2 2860.88   547.7 2882.24   556.4 2886.62   572.1 2897.27   587.2  2906.4
#Mann= 5 ,-1,0
       0      .1       0      20     .05       0     130      .1       0
   289.9    .045       0   397.6      .1       0
Bank Sta=289.9,397.6
XS Rating Curve= 0 ,0
Exp/Cntr(USF)=0,0
Exp/Cntr=0.3,0.1

Type RM Length L Ch R = 1 ,79298   ,254.6,254.6,254.6
XS GIS Cut Line= 2
2365901.53529673685108.6514662972366341.73201737685539.883144546
#Sta/Elev= 30
       0 2854.17    67.3 2834.47   123.9 2816.41   132.5 2812.69   149.4 2810.29
   166.3 2803.45   188.9 2796.84   233.3 2796.48     254 2794.09   286.6 2794.06
   292.3 2793.41   301.82790.196   307.7 2788.84   326.6 2788.62   390.1 2788.66
   401.3 2790.39   415.2 2795.53   423.7 2800.16   434.9 2802.74   449.2 2807.73
   479.7  2819.2   492.3 2825.49   502.1 2828.58   520.9 2836.72   552.5 2848.19
   558.1 2850.73   574.8 2861.65   591.6 2864.95   606.6 2874.39   616.2 2878.38
#Mann= 3 ,-1,0
       0      .1       0   301.8    .045       0   401.3      .1       0
Bank Sta=301.8,401.3
XS Rating Curve= 0 ,0
Exp/Cntr=0.3,0.1

Type RM Length L Ch R = 1 ,79043   ,248.1,248.1,248.1
XS GIS Cut Line= 2
 2365709.1043317 685360.553142752366200.34290169 685686.76625564
#Sta/Elev= 30
       0 2891.73     8.4  2888.5    18.1 2881.55    27.7 2878.28    45.9 2866.51
    90.1 2841.99   103.7 2836.59   112.3  2831.1   132.5 2821.85   138.1 2818.05
   152.5 2815.96   176.5 2803.96   204.7 2796.39   224.6 2789.24     245 2791.39
   248.6 2791.33   253.4 2789.29   259.5 2788.32   308.5 2788.27     341  2788.3
   347.72789.267   373.4 2797.49   441.3 2800.14   467.2  2804.3   496.1 2812.15
   510.5  2818.3   522.1 2819.53   527.8 2823.01   536.5  2826.5   589.7 2843.66
#Mann= 3 ,-1,0
       0      .1       0   253.4    .045       0   347.7      .1       0
Bank Sta=253.4,347.7
XS Rating Curve= 0 ,0
Exp/Cntr(USF)=0,0
Exp/Cntr=0.3,0.1

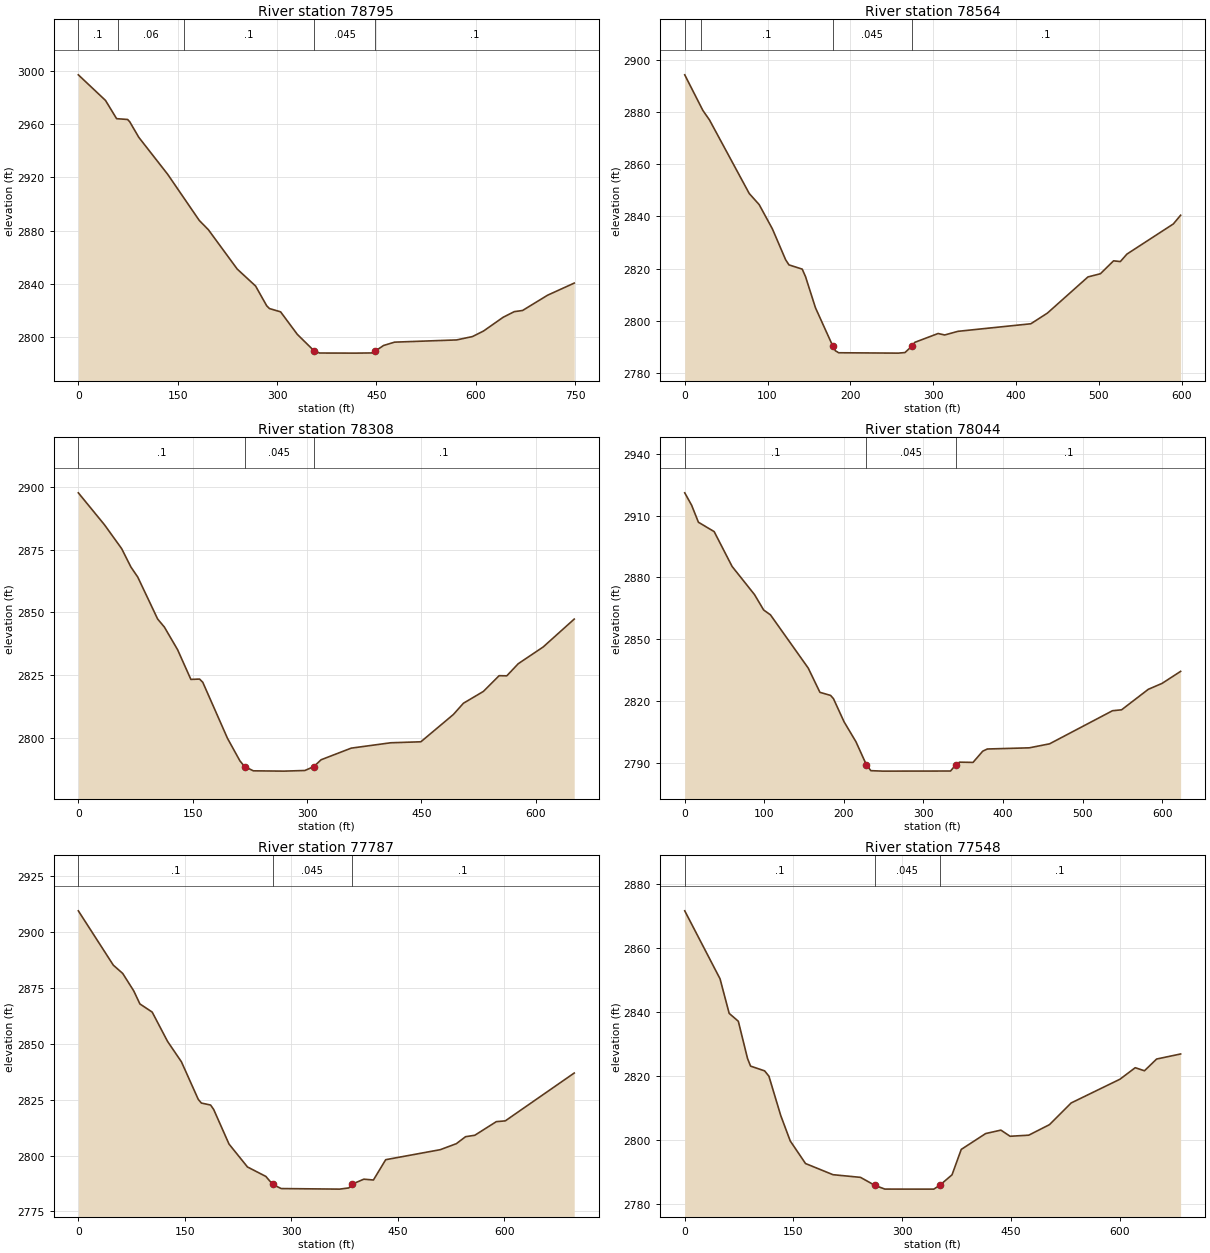
Type RM Length L Ch R = 1 ,78795   ,231,231,231
XS GIS Cut Line= 2
2365453.14623315685606.7693391252366166.55468736685833.969264561
#Sta/Elev= 30
       0 2997.11      41  2977.9    57.8 2964.18    74.4 2963.57    77.6 2961.85
    91.3 2950.16   134.9  2922.4   182.6 2887.73   196.3 2880.79   239.9 2851.21
   267.6 2838.49   284.4 2823.64   288.6 2821.54   305.4 2819.08   330.6 2802.18
   355.8 2789.85   364.2 2788.15   418.2 2788.07   442.9 2788.21   448.2 2789.56
   460.8  2793.8   477.5 2796.32   571.1 2797.98   595.1 2800.52   611.9 2804.71
   641.3 2814.97   658.1 2819.21   670.7  2820.1   708.4 2831.55   748.7 2840.67
#Mann= 5 ,-1,0
       0      .1       0      60     .06       0     160      .1       0
   355.8    .045       0   448.2      .1       0
Bank Sta=355.8,448.2
XS Rating Curve= 0 ,0
Exp/Cntr=0.3,0.1

Type RM Length L Ch R = 1 ,78564   ,255.9,255.9,255.9
XS GIS Cut Line= 2
 2365586.2946892685947.7367459522366184.99169638685963.087951264
#Sta/Elev= 30
       0 2894.19    21.9 2880.56    29.9 2876.91    77.9 2848.75    89.9  2844.5
   105.9 2835.18   121.9 2823.35   125.9 2821.42   141.9 2819.79   145.9  2816.9
   157.9 2804.99   178.8 2790.35   181.9 2788.56   185.9 2787.77     258 2787.63
     266 2787.85     274  2790.2     278 2791.78     306 2795.14     314 2794.58
     330 2795.98     418 2798.87     438 2802.95     487 2816.81     502 2818.02
   517.9 2822.97   526.1 2822.69   534.1 2825.56   590.1 2837.09   598.9 2840.43
#Mann= 4 ,-1,0
       0     .06       0      20      .1       0   178.8    .045       0
     274      .1       0
Bank Sta=178.8,274
XS Rating Curve= 0 ,0
Exp/Cntr(USF)=0,0
Exp/Cntr=0.3,0.1

Type RM Length L Ch R = 1 ,78308   ,264,264,264
XS GIS Cut Line= 2
2365656.68997584686292.3288892462366253.51160209686034.055076117
#Sta/Elev= 30
       0 2897.52    34.3 2884.82    56.8 2875.35    68.9 2868.07    77.9 2864.06
     104 2847.38   112.8  2844.2   130.2 2835.17   147.6 2823.38     159 2823.52
   163.2 2822.24   195.6 2799.98   211.9 2791.02     218 2788.77   229.5 2787.06
   269.6 2786.94   297.1 2787.19   308.9 2788.76   318.4 2791.46   357.9 2796.08
   409.6  2798.2   449.2  2798.6   491.8 2809.43     505 2813.91   531.2 2818.61
   551.8 2824.86   561.9 2824.81   576.9 2829.62   609.6 2836.27   650.3 2847.35
#Mann= 3 ,-1,0
       0      .1       0     218    .045       0   308.9      .1       0
Bank Sta=218,308.9
XS Rating Curve= 0 ,0
Exp/Cntr=0.3,0.1

Type RM Length L Ch R = 1 ,78044   ,256.8,256.8,256.8
XS GIS Cut Line= 2
2365853.83200794686599.1743956082366296.99674338686161.045623068
#Sta/Elev= 30
       0    2921     8.7 2914.96    17.2 2906.75      37  2902.2    59.5 2885.34
    87.7 2871.68    99.2 2864.21   107.7 2861.89   155.2 2836.07   169.9 2824.32
   183.3 2822.83   186.9 2821.26   200.2 2810.07   215.2 2800.36   228.3  2789.2
   233.9 2786.36   249.1 2786.14     334 2786.19   340.8 2789.25   345.3 2790.48
   362.3 2790.37   374.5  2795.8   380.2 2796.86     433 2797.43   458.5 2799.37
   537.6 2815.41     549 2815.85   582.6 2825.79   599.9 2828.66   623.2 2834.48
#Mann= 3 ,-1,0
       0      .1       0   228.3    .045       0   340.8      .1       0
Bank Sta=228.3,340.8
XS Rating Curve= 0 ,0
Exp/Cntr(USF)=0,0
Exp/Cntr=0.3,0.1

Type RM Length L Ch R = 1 ,77787   ,239.7,239.7,239.7
XS GIS Cut Line= 2
2366134.78052598686857.3462525142366401.23450866686211.745643575
#Sta/Elev= 30
       0 2909.42    49.3 2885.12    62.5 2881.43    78.1  2873.6    86.7  2867.8
     104 2864.15   125.7 2851.03   145.2 2841.92   168.9 2825.14   173.3 2823.48
   186.3 2822.59   190.6 2820.63   212.2 2805.16   238.2 2794.91   264.1 2790.68
   273.8 2787.07   285.8 2785.25     368    2785     381 2785.54   385.3 2787.18
   402.1 2789.45   415.6 2789.08   432.9 2798.16   509.7 2802.63   532.4 2805.32
   545.4 2808.44   558.4 2809.08   588.7 2815.17   601.3 2815.51   698.4  2836.9
#Mann= 3 ,-1,0
       0      .1       0   273.8    .045       0   385.3      .1       0
Bank Sta=273.8,385.3
XS Rating Curve= 0 ,0
Exp/Cntr=0.3,0.1

Type RM Length L Ch R = 1 ,77548   ,247.9,247.9,247.9
XS GIS Cut Line= 2
2366395.19801999686911.4040955792366609.22644335686261.764881124
#Sta/Elev= 30
       0 2871.74    48.7 2850.49    61.3 2839.69    73.9 2837.23    86.6  2825.6
    90.8 2823.21   110.2 2821.72   116.1 2820.06   132.4 2807.78   145.5 2799.83
   166.6 2792.76   204.5 2789.27   242.4 2788.44   262.3 2785.93   276.1 2784.77
   343.5 2784.76   351.9 2785.98   368.7 2789.24   381.4 2797.17   415.1 2802.13
   436.1  2803.2   448.8 2801.28   474.5 2801.62   503.1 2804.91     533 2811.69
   600.4 2819.12   621.4 2822.71   634.1 2821.75   650.9 2825.42     684    2827
#Mann= 3 ,-1,0
       0      .1       0   262.3    .045       0   351.9      .1       0
Bank Sta=262.3,351.9
XS Rating Curve= 0 ,0
Exp/Cntr(USF)=0,0
Exp/Cntr=0.3,0.1