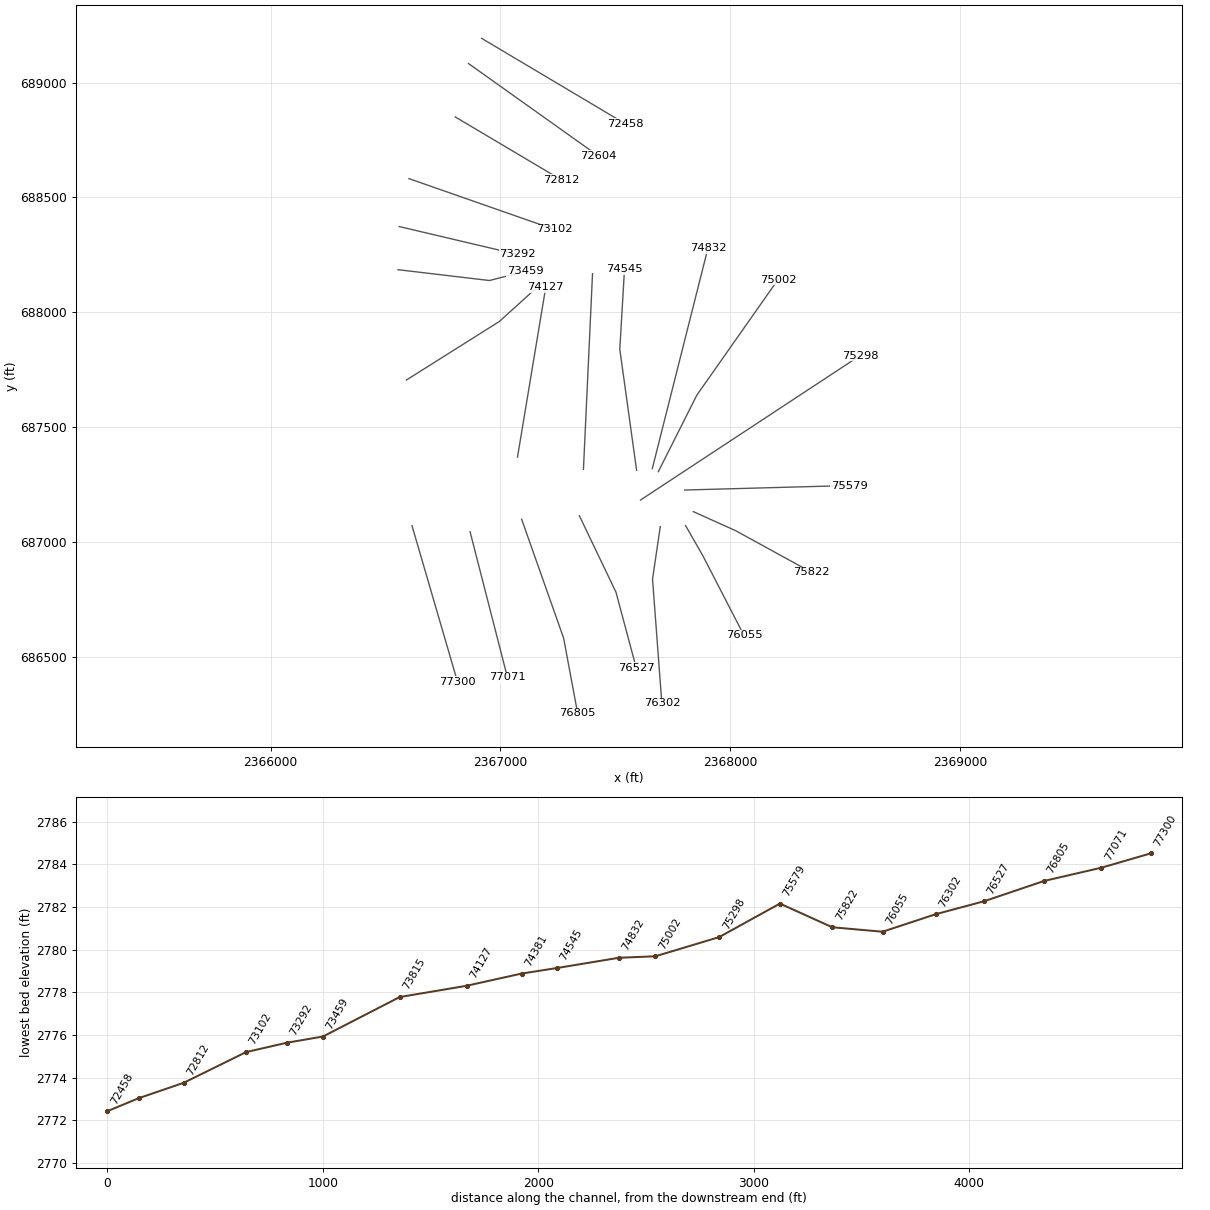
HEC-RAS study LAURELFK.prj: LAURELFK

--- LAURELFK.g01 (geometry) --- (continued)

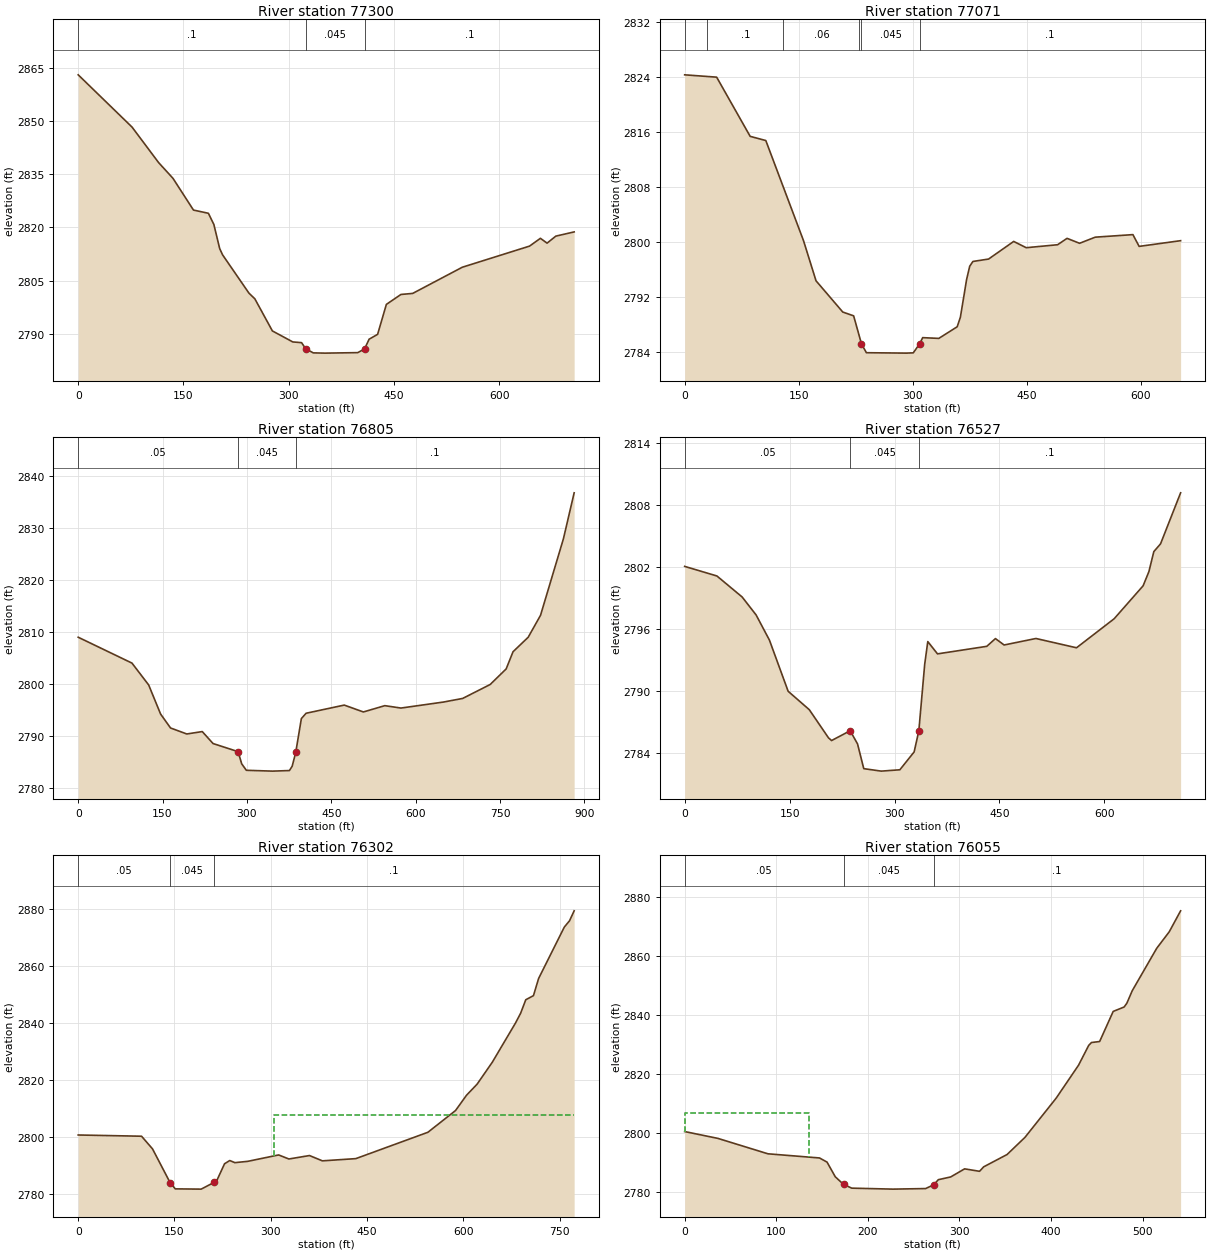
Type RM Length L Ch R = 1 ,77300   ,228.6,228.6,228.6
XS GIS Cut Line= 2
2366615.74688925687070.8908477652366813.62388925686392.182747486
#Sta/Elev= 30
       0  2863.1    76.8 2848.33   114.6 2838.32   135.1 2833.87   164.3 2824.91
   185.6    2824   193.4 2820.83   201.7 2814.02   205.9 2812.24   243.4 2801.45
   251.8 2799.85   276.8 2790.78   305.9 2787.67   318.4 2787.47   324.3 2785.74
   335.1 2784.58   351.8 2784.51   398.5 2784.65   408.2 2785.68   414.7 2788.44
   426.8 2789.81   439.3 2798.27   460.1 2801.08   476.8 2801.37   547.6 2808.77
   643.4 2814.73   658.9 2816.93   668.4 2815.57   680.9 2817.55     707 2818.74
#Mann= 3 ,-1,0
       0      .1       0   324.3    .045       0   408.2      .1       0
Bank Sta=324.3,408.2
XS Rating Curve= 0 ,0
Exp/Cntr=0.3,0.1

Type RM Length L Ch R = 1 ,77071   ,265.6,265.6,265.6
XS GIS Cut Line= 2
 2366868.4332081687044.6452232262367030.70312386686412.352103214
#Sta/Elev= 30
       0 2824.28    42.1 2823.94    86.2 2815.34   106.8 2814.73   156.4 2800.19
   172.9 2794.35   208.1 2789.81   222.4 2789.26   232.7 2785.19   239.2  2783.9
   291.8 2783.84   300.9 2783.88   309.2 2785.18   313.3 2786.09   334.5 2785.98
   358.7 2787.67   362.9 2789.05   371.1 2794.54   375.2 2796.47   379.4 2797.16
     400 2797.51   433.1 2800.07   449.6 2799.16   490.9 2799.59   503.3 2800.52
   519.8  2799.8   540.4 2800.69     590 2801.06   598.2 2799.35   652.8 2800.18
#Mann= 6 ,-1,0
       0     .05       0      30      .1       0     130     .06       0
     230      .1       0   232.7    .045       0   309.2      .1       0
Bank Sta=232.7,309.2
XS Rating Curve= 0 ,0
Exp/Cntr(USF)=0,0
Exp/Cntr=0.3,0.1

Type RM Length L Ch R = 1 ,76805   ,278.3,278.3,278.3
XS GIS Cut Line= 3
2367092.85881997687099.3095259782367275.66481313686581.540467179
2367336.64571969686254.390110754
#Sta/Elev= 30
       0 2808.95    95.6 2803.98   125.3 2799.78   146.5 2794.19   164.2 2791.51
   193.1 2790.36   220.6 2790.82   239.8 2788.52   284.32786.964   290.7 2784.63
     299 2783.38   345.6 2783.22   375.6 2783.33   380.5 2784.17   386.8  2786.8
   396.8 2793.31   405.2 2794.34   473.1 2795.91   507.1 2794.59   545.2  2795.8
   573.9 2795.34   649.3 2796.49   683.7 2797.19   732.6 2799.87     761 2802.86
   773.2 2806.16   800.2 2808.95   822.1 2813.16   862.8 2827.86   881.9  2836.7
#Mann= 3 ,-1,0
       0     .05       0   284.3    .045       0   386.8      .1       0
Bank Sta=284.3,386.8
XS Rating Curve= 0 ,0
Exp/Cntr=0.3,0.1

Type RM Length L Ch R = 1 ,76527   ,225.2,225.2,225.2
XS GIS Cut Line= 3
2367344.05192669687114.5891524312367503.52408528686781.656049415
2367591.27497555686453.467746877
#Sta/Elev= 30
       0 2802.09    46.1 2801.16    82.1 2799.13   102.1 2797.39   121.1 2794.96
   147.9    2790   178.1 2788.22   205.6 2785.49     210 2785.23   236.6 2786.18
   247.1  2784.9     256 2782.51     281 2782.27   307.6  2782.4     328 2784.13
   334.7 2786.17   343.1 2792.62   347.5 2794.81   361.4 2793.62   431.8 2794.35
   444.2  2795.1   456.6 2794.48   502.1 2795.11   560.1 2794.21   613.9 2797.02
   655.3 2800.21   663.6 2801.59   670.6 2803.52   680.2 2804.27   708.9 2809.21
#Mann= 3 ,-1,0
       0     .05       0   236.6    .045       0   334.7      .1       0
Bank Sta=236.6,334.7
XS Rating Curve= 0 ,0
Exp/Cntr(USF)=0,0
Exp/Cntr=0.3,0.1

Type RM Length L Ch R = 1 ,76302   ,246.6,246.6,246.6
XS GIS Cut Line= 3
2367696.11511343687066.7893375792367662.53780133 686838.63217875
2367703.07881461686297.967926954
#Sta/Elev= 30
       0 2800.63    98.7  2800.2   115.8 2795.76   143.1 2783.98   151.2 2781.75
   191.6 2781.66   211.9 2784.04   215.9 2784.63     228 2790.54   236.1 2791.68
   244.1 2790.94   264.2  2791.4   312.3 2793.64   328.3 2792.22   360.4 2793.43
   380.5 2791.57   432.6 2792.35   544.9 2801.58     588 2809.21   605.1 2814.57
   621.6 2818.45   645.2 2826.11   681.3 2839.83   689.4  2843.3   697.4 2848.02
   709.4 2849.47   717.4 2855.46   757.5  2873.5   765.6  2875.7   772.8 2879.19
#Mann= 3 ,-1,0
       0     .05       0   143.1    .045       0   211.9      .1       0
#XS Ineff= 2 , 0
                           304.7         2807.63
Permanent Ineff=
       F       F
Bank Sta=143.1,211.9
XS Rating Curve= 0 ,0
Exp/Cntr=0.3,0.1

Type RM Length L Ch R = 1 ,76055   ,233.4,233.4,233.4
XS GIS Cut Line= 3
2367806.13968116687072.0768226172367881.22130299686941.128208003
2368060.27776175686594.206319146
#Sta/Elev= 30
       0 2800.35    36.3 2798.03    90.9 2792.81   147.2  2791.4   155.4    2790
   164.4 2785.03   173.4 2782.45   182.4 2781.17   227.4 2780.84     263 2781.03
   271.82782.293   276.9 2784.04   290.4 2784.97   305.6 2787.71   321.9 2786.88
   326.4 2788.39     352 2792.58   371.5 2798.39   405.5 2811.65     430 2822.85
   441.1 2829.56   444.1 2830.52     453 2830.86   467.8 2841.06   479.7 2842.55
   482.7 2843.83   488.6 2848.08   515.3 2862.45     529 2868.05   541.4 2875.15
#Mann= 3 ,-1,0
       0     .05       0   173.4    .045       0   271.8      .1       0
#XS Ineff= 2 , 0
          135.91  2806.6
Permanent Ineff=
       F       F
Bank Sta=173.4,271.8
XS Rating Curve= 0 ,0
Exp/Cntr(USF)=0,0
Exp/Cntr=0.3,0.1

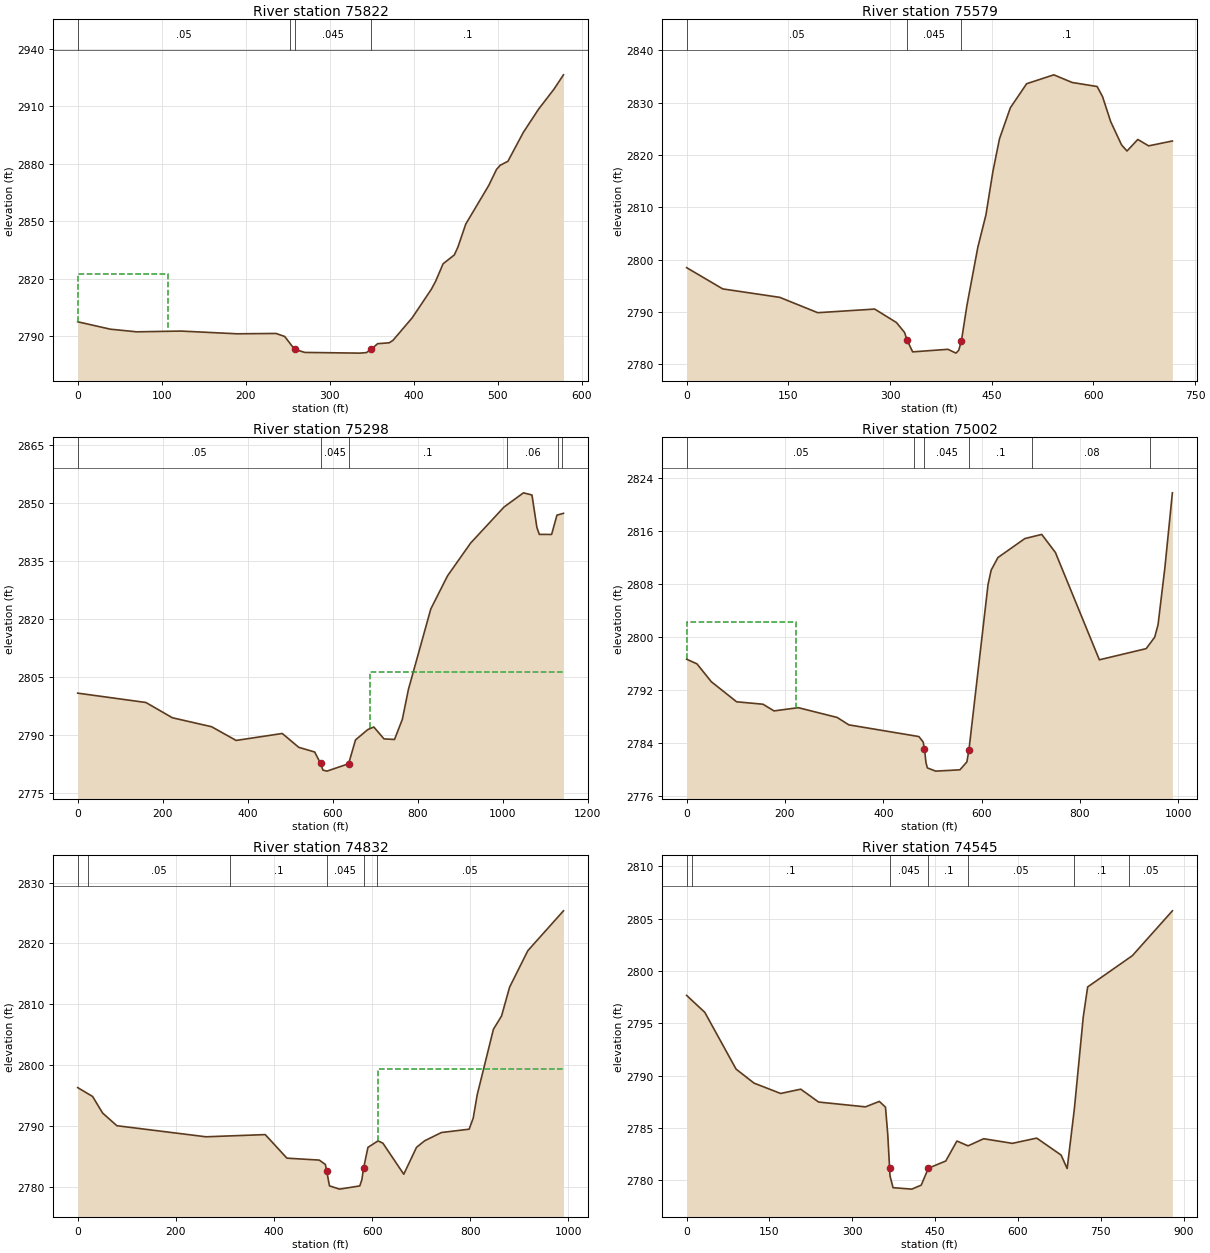
Type RM Length L Ch R = 1 ,75822   ,242.6,242.6,242.6
XS GIS Cut Line= 3
2367840.11728124687132.4748896632368024.74637078687049.294013281
2368354.09399336686868.488006641
#Sta/Elev= 30
       0 2797.44    38.8 2793.57    70.3 2792.18   122.9 2792.58   190.1 2791.15
     236 2791.33   246.4 2789.75   258.1 2783.08   270.3 2781.42   335.7 2781.05
   343.6 2781.32   349.5 2783.11     357 2785.99   370.7 2786.44   375.2 2787.69
   398.1 2799.48   420.9  2814.4   426.1 2818.65   434.9 2827.73   448.3 2832.38
   452.6  2836.5   461.9 2848.49   489.3 2868.71   498.5 2877.04     503 2879.26
   512.1 2881.32   530.4 2896.39   548.6 2908.58   566.9 2918.99   578.2  2926.5
#Mann= 4 ,-1,0
       0     .05       0   252.5      .1       0   258.1    .045       0
   349.5      .1       0
#XS Ineff= 2 , 0
          107.52 2822.61
Permanent Ineff=
       F       F
Bank Sta=258.1,349.5
XS Rating Curve= 0 ,0
Exp/Cntr=0.3,0.1

Type RM Length L Ch R = 1 ,75579   ,281.6,281.6,281.6
XS GIS Cut Line= 2
2367802.88410228687226.4994391592368519.10993734687246.083739336
#Sta/Elev= 30
       0 2798.48    53.3 2794.42   137.3 2792.81   193.4 2789.88   277.4 2790.57
   309.4 2788.01   321.4 2786.12   325.4 2784.58   333.4  2782.4   385.4 2782.89
   397.3 2782.16   401.4 2782.72   405.4 2784.57   413.4 2791.23   429.5 2802.36
   441.5 2808.57   451.8 2816.88   461.5 2823.09   477.5    2829   501.5 2833.59
   541.6 2835.29   568.6 2833.83   605.5 2833.06   613.5 2831.12   625.5 2826.35
   641.5 2821.92   649.5 2820.74   665.5 2822.95   681.5 2821.73   716.5 2822.66
#Mann= 3 ,-1,0
       0     .05       0   325.4    .045       0   405.4      .1       0
Bank Sta=325.4,405.4
XS Rating Curve= 0 ,0
Exp/Cntr(USF)=0,0
Exp/Cntr=0.3,0.1

Type RM Length L Ch R = 1 ,75298   ,296,296,296
XS GIS Cut Line= 2
2367610.13025898687182.8683309382368564.93891313687811.050816458
#Sta/Elev= 30
       0 2800.77   160.5 2798.35   222.7  2794.4     315 2792.08   372.8 2788.53
   481.3 2790.33   520.1 2786.75   557.6 2785.54   571.42782.574     577 2780.85
   586.4 2780.59   637.4  2782.5   653.6 2788.66   682.4 2791.33   696.7 2792.01
   720.7 2788.93   745.4 2788.78   763.8 2793.98   778.1 2801.72   830.8 2822.56
   870.2 2831.13   924.4 2839.59  1003.2 2848.94  1048.8  2852.6  1068.8 2852.04
  1080.4 2843.65  1086.1 2841.85    1115 2841.83  1127.6 2846.83  1142.9 2847.29
#Mann= 6 ,-1,0
       0     .05       0   571.4    .045       0   637.4      .1       0
    1010     .06       0    1130     .07       0    1140     .05       0
#XS Ineff= 2 , 0
                          688.59         2806.23
Permanent Ineff=
       F       F
Bank Sta=571.4,637.4
XS Rating Curve= 0 ,0
Exp/Cntr=0.3,0.1

Type RM Length L Ch R = 1 ,75002   ,169.6,169.6,169.6
XS GIS Cut Line= 3
2367687.73773614687306.4544038932367855.43530081 687639.58334991
2368208.95989658688142.676043895
#Sta/Elev= 30
       0 2796.62      21 2795.92      50 2793.23   101.6 2790.18   155.3 2789.81
   177.7  2788.8     227 2789.29   306.2 2787.81   329.8 2786.69   472.3 2784.92
   480.9 2784.11   483.7 2783.05   486.6 2781.03   489.5 2780.18   506.4 2779.69
   555.8 2779.89   569.9 2781.09   574.12782.914   612.9 2807.91   619.3  2810.1
     633    2812   687.8 2814.87   722.1  2815.5   749.9 2812.77   839.3 2796.53
   934.5 2798.22   951.8 2799.95   958.6 2801.82   972.6 2810.51   987.8 2821.79
#Mann= 6 ,-1,0
       0     .05       0  462.96      .1       0   483.7    .045       0
   574.1      .1       0  702.96     .08       0  942.96     .06       0
#XS Ineff= 2 , 0
          221.48 2802.23
Permanent Ineff=
       F       F
Bank Sta=483.7,574.1
XS Rating Curve= 0 ,0
Exp/Cntr(USF)=0,0
Exp/Cntr=0.3,0.1

Type RM Length L Ch R = 1 ,74832   ,287.1,287.1,287.1
XS GIS Cut Line= 2
2367661.52224142687319.8228819242367903.83277557688279.500442785
#Sta/Elev= 30
       0  2796.3    30.3 2794.85    50.9 2792.11    79.8 2790.04   261.3 2788.22
   382.1 2788.58   426.3 2784.71   492.3 2784.39   504.7 2783.67   507.3 2782.62
     513 2780.16   533.6 2779.62   574.8 2780.15     579 2781.16   582.52783.052
   591.4 2786.48     612 2787.55   621.9 2787.17   664.4 2782.07   690.4 2786.49
   706.9 2787.56   741.1 2788.92   797.6 2789.47   805.9 2791.28   814.1 2795.14
   847.1 2805.89   863.6 2808.06   880.1 2812.82   917.3 2818.81   989.8 2825.35
#Mann= 6 ,-1,0
       0      .1       0      20     .05       0     310      .1       0
   507.3    .045       0   582.5      .1       0     610     .05       0
#XS Ineff= 2 , 0
                          612.42         2799.44
Permanent Ineff=
       F       F
Bank Sta=507.3,582.5
XS Rating Curve= 0 ,0
Exp/Cntr(USF)=0,0
Exp/Cntr=0.3,0.1

Type RM Length L Ch R = 1 ,74545   ,164.3,164.3,164.3
XS GIS Cut Line= 3
2367593.18506552687312.5688401922367520.04017148687839.007480859
2367540.42132213688186.288970443
#Sta/Elev= 30
       0 2797.67    32.9 2796.05    89.5 2790.62     122 2789.28   170.2 2788.29
   206.6  2788.7   238.9 2787.47   323.7 2787.01   348.9 2787.53     360 2786.98
   364.1 2784.39  367.44 2781.15   368.1 2780.42   373.7 2779.28   407.6 2779.14
   424.7 2779.52   437.6 2781.14   469.1 2781.83   489.3 2783.74   509.5 2783.28
   537.7 2783.96   589.8 2783.52   633.8 2784.02   677.9  2782.4   688.9 2781.11
     702 2786.85     718 2795.59     726 2798.48   806.9 2801.47   879.4 2805.76
#Mann= 7 ,-1,0
       0     .05       0      10      .1       0  367.44    .045       0
   437.6      .1       0     510     .05       0   701.5      .1       0
   801.5     .05       0
Bank Sta=367.44,437.6
XS Rating Curve= 0 ,0
Exp/Cntr(USF)=0,0
Exp/Cntr=0.3,0.1

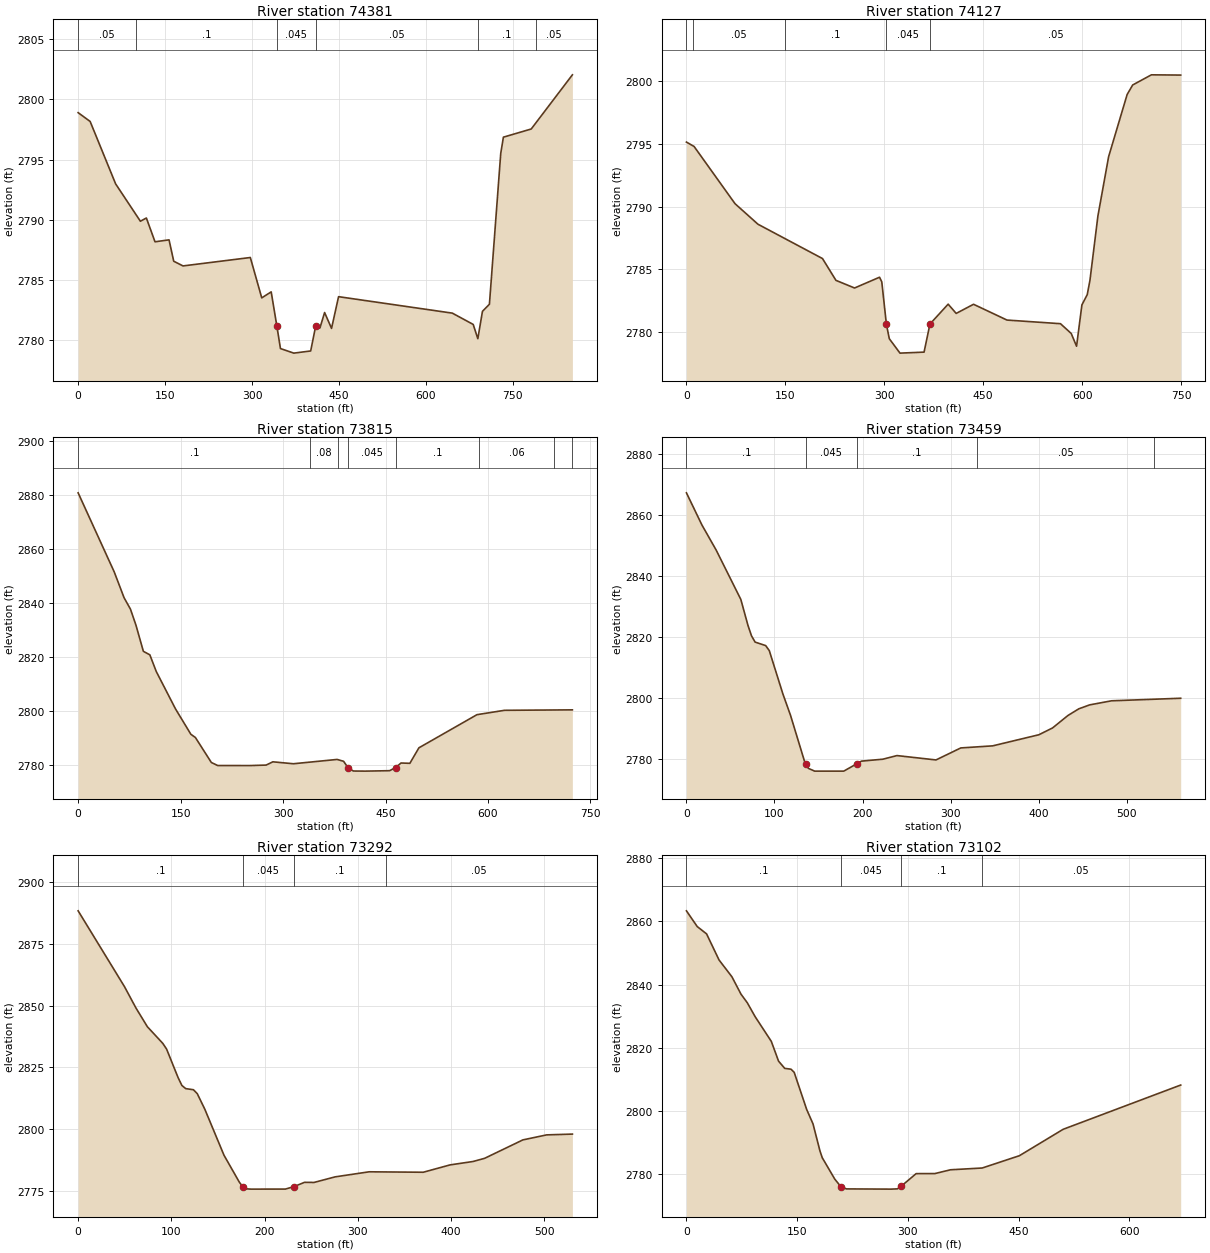
Type RM Length L Ch R = 1 ,74381   ,254,254,254
XS GIS Cut Line= 2
2367361.83691584687316.5062717892367401.36808001688168.124827035
#Sta/Elev= 30
       0  2798.9    20.7 2798.17    64.7 2792.97   107.4 2789.86   117.7 2790.13
   132.6 2788.15   156.8 2788.31   164.9 2786.53   180.9 2786.14     297 2786.84
   316.7 2783.48     333 2783.98   342.6 2781.18     349 2779.26     372 2778.88
   401.1 2779.06   409.8 2781.15   417.1 2780.98   425.1 2782.26   437.1 2780.94
   449.2 2783.58   645.4 2782.21   681.4 2781.27   689.4 2780.08   697.4 2782.36
   709.4 2782.95   728.9  2795.5   733.5 2796.86   781.5 2797.54   852.5 2802.05
#Mann= 6 ,-1,0
       0     .05       0     100      .1       0   342.6    .045       0
   409.8     .05       0     690      .1       0     790     .05       0
Bank Sta=342.6,409.8
XS Rating Curve= 0 ,0
Exp/Cntr=0.3,0.1

Type RM Length L Ch R = 1 ,74127   ,311.6,311.6,311.6
XS GIS Cut Line= 2
 2367074.7923351687369.721748051  2367197.796582688108.988557632
#Sta/Elev= 30
       0 2795.16    11.6 2794.81    73.7 2790.24   108.5  2788.6   206.3 2785.86
   226.7 2784.12   254.9 2783.51   292.8 2784.37   296.2    2784   303.2  2780.6
   307.6 2779.46   323.8 2778.31   360.3 2778.39   369.2 2780.63   396.8 2782.22
     409 2781.48   435.3 2782.21     486 2780.95   567.1 2780.66   583.4 2779.88
   591.5 2778.86   599.6 2782.16   607.7 2782.98   611.8 2784.12   623.9 2789.27
   640.1 2793.99   668.2 2798.96   676.6 2799.72     705 2800.53   749.4 2800.51
#Mann= 5 ,-1,0
       0      .1       0      10     .05       0     150      .1       0
   303.2    .045       0   369.2     .05       0
Bank Sta=303.2,369.2
XS Rating Curve= 0 ,0
Exp/Cntr(USF)=0,0
Exp/Cntr=0.3,0.1

Type RM Length L Ch R = 1 ,73815   ,356.4,356.4,356.4
XS GIS Cut Line= 3
 2366591.3389629687705.2406475762366995.11670322687959.548814514
2367177.86935405688124.754279855
#Sta/Elev= 30
       0 2880.84    52.8 2851.58    67.3 2841.97    76.6 2837.77    84.7  2831.8
    95.5 2822.15     105 2820.84   114.4 2814.66   142.5 2800.85     165 2791.44
   171.7 2790.22     195 2780.99   204.3 2779.85   251.5 2779.84   275.2 2780.02
   285.1 2781.23   315.1 2780.51   379.2 2782.11   388.6 2781.42     395 2779.09
   402.8 2777.82   420.2 2777.78   455.9 2777.94   464.6 2779.06   472.7 2780.79
   485.6 2780.67   498.9 2786.42   583.9 2798.69   624.2  2800.3   723.5 2800.47
#Mann= 8 ,-1,0
       0      .1       0     340     .08       0     380      .1       0
     395    .045       0   464.6      .1       0  587.19     .06       0
  697.19      .1       0  723.54     .05       0
Bank Sta=395,464.6
XS Rating Curve= 0 ,0
Exp/Cntr=0.3,0.1

Type RM Length L Ch R = 1 ,73459   ,166.9,166.9,166.9
XS GIS Cut Line= 3
2366554.75898623688185.4237367822366952.75651376 688138.32862697
2367108.25785033688178.186672612
#Sta/Elev= 30
       0 2867.23    17.5 2856.73    33.9 2848.38    61.8 2832.23    69.9 2823.71
    73.9 2820.31      78 2818.26      90 2817.11    94.1 2815.46   109.5 2801.29
   118.2 2794.24   134.3 2778.96   135.9  2778.2   138.4 2776.85   145.6 2775.93
   178.7 2775.93   193.2  2778.3   198.8 2779.21     223 2779.84   239.1 2781.03
   283.4  2779.6   311.6 2783.54   347.8 2784.22   400.2 2787.86   415.8  2790.1
   433.2 2794.17   445.6 2796.37     458 2797.67   482.8    2799   561.3 2799.84
#Mann= 5 ,-1,0
       0      .1       0   135.9    .045       0   193.2      .1       0
     330     .05       0  530.77      .1       0
Bank Sta=135.9,193.2
XS Rating Curve= 0 ,0
Exp/Cntr(USF)=0,0
Exp/Cntr=0.3,0.1

Type RM Length L Ch R = 1 ,73292   ,189.8,189.8,189.8
XS GIS Cut Line= 2
2366559.80934917688373.2724451672367075.85560723688251.655389521
#Sta/Elev= 30
       0 2888.41    49.7 2857.71      62 2849.06    74.3 2841.44    90.8 2834.71
    94.9 2832.39   107.2 2820.86   111.3 2817.65   115.4 2816.37   123.7 2815.91
   127.8 2814.33     136 2807.94   156.5 2789.36     173 2778.41   176.6 2776.66
   181.2 2775.73   185.3 2775.64   222.3 2775.66   231.6 2776.66   242.8 2778.39
   253.1 2778.35   275.7 2780.61   312.2 2782.66   370.2 2782.48     399 2785.46
   423.7 2786.84   436.1 2788.13   477.1 2795.59   502.6 2797.62   530.2 2797.94
#Mann= 4 ,-1,0
       0      .1       0   176.6    .045       0   231.6      .1       0
     330     .05       0
Bank Sta=176.6,231.6
XS Rating Curve= 0 ,0
Exp/Cntr=0.3,0.1

Type RM Length L Ch R = 1 ,73102   ,289.8,289.8,289.8
XS GIS Cut Line= 2
2366602.40582461688581.8636591482367234.49170335688360.806302649
#Sta/Elev= 30
       0 2863.38    14.6  2858.4    27.3 2856.07    44.2  2847.8    61.6 2842.49
    73.9 2836.98    82.4 2834.27      93 2829.87     115 2822.01   124.8 2815.75
   133.2 2813.46   141.7  2813.2     146 2812.19   162.9 2800.44   171.5 2795.86
   180.9 2787.29     184 2785.15     201 2778.36   209.1 2776.02   216.8 2775.27
   277.3  2775.2   285.8 2775.28   290.8  2776.1   311.2 2780.11   336.6 2780.13
   357.8 2781.33   400.7 2781.89   451.1 2785.79   510.4 2794.16   669.6 2808.18
#Mann= 4 ,-1,0
       0      .1       0   209.1    .045       0   290.8      .1       0
     400     .05       0
Bank Sta=209.1,290.8
XS Rating Curve= 0 ,0
Exp/Cntr(USF)=0,0
Exp/Cntr=0.3,0.1

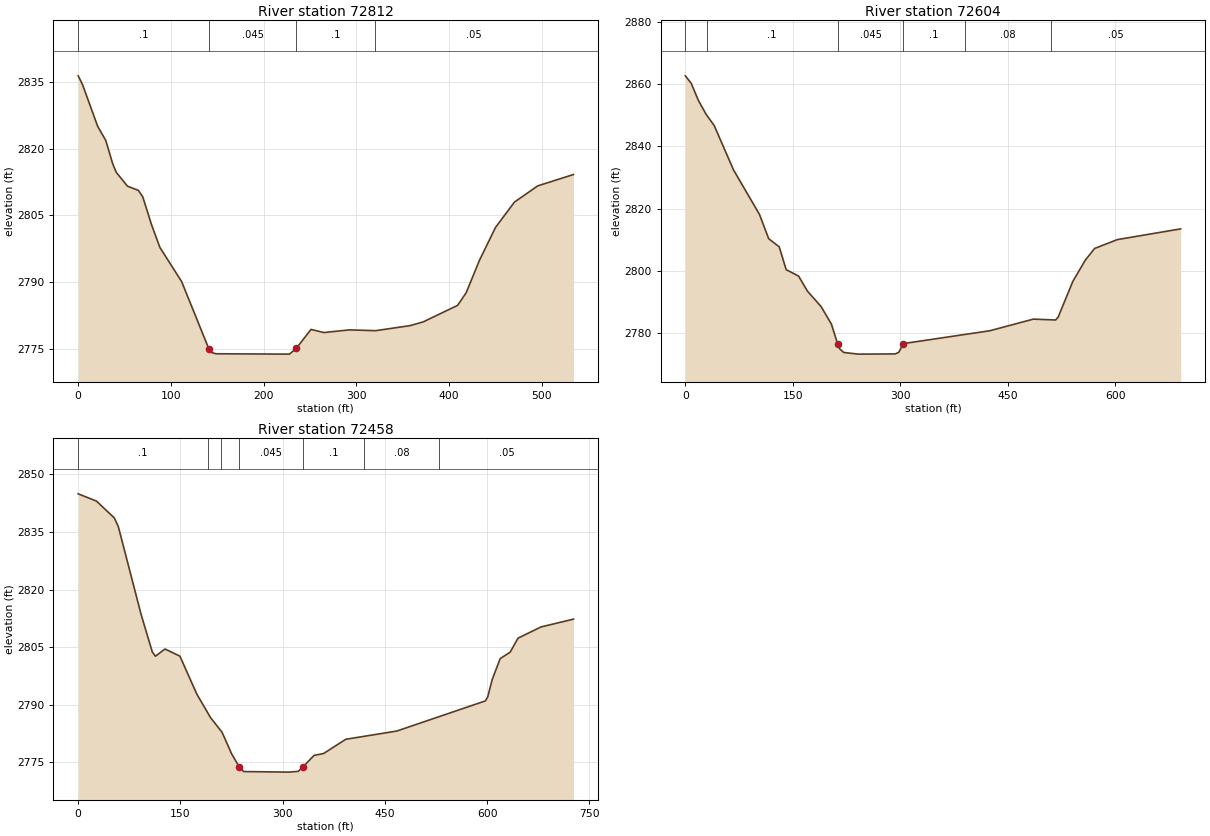
Type RM Length L Ch R = 1 ,72812   ,208.4,208.4,208.4
XS GIS Cut Line= 2
2366804.21328989688850.118387923 2367263.6726492688577.477703222
#Sta/Elev= 30
       0 2836.42     4.6 2834.49    21.1 2825.02    29.8 2821.86    37.2 2816.65
      41 2814.72    53.2 2811.57    64.9 2810.63    69.7 2809.16      79 2802.98
    88.2 2797.76   111.6  2790.1   140.8 2775.02   144.1  2774.1   148.8 2773.84
   227.9 2773.76   235.32775.056   251.1 2779.32   265.1 2778.62   292.6 2779.22
   320.9 2779.04   358.1 2780.18   372.1 2781.01   409.3 2784.74   418.6 2787.61
   432.9  2794.9   450.2 2802.29   470.6 2807.99   495.7 2811.64   534.3  2814.2
#Mann= 4 ,-1,0
       0      .1       0   140.8    .045       0   235.3      .1       0
     320     .05       0
Bank Sta=140.8,235.3
XS Rating Curve= 0 ,0
Exp/Cntr=0.3,0.1

Type RM Length L Ch R = 1 ,72604   ,145.9,145.9,145.9
XS GIS Cut Line= 2
2366861.45741425689082.6967324662367424.46286909688682.030273812
#Sta/Elev= 30
       0 2862.79     8.2 2860.38    18.1 2854.92    28.9 2850.41    40.3 2846.75
    67.2 2832.46   103.4 2818.11   116.3 2810.27     131 2807.64   140.7 2800.27
   157.9 2798.24   170.3 2793.38   189.5 2788.35   203.8 2782.71   212.4 2776.41
   215.3 2774.75     221 2773.58   241.1 2773.04     293 2773.11   297.9 2773.66
   304.2 2776.44   424.7 2780.57   485.5 2784.33   516.5 2784.05     520 2784.92
   540.7 2796.55   558.1 2803.38     571 2807.12   602.8 2809.98     691 2813.43
#Mann= 6 ,-1,0
       0     .06       0      30      .1       0   212.4    .045       0
   304.2      .1       0     390     .08       0     510     .05       0
Bank Sta=212.4,304.2
XS Rating Curve= 0 ,0
Exp/Cntr(USF)=0,0
Exp/Cntr=0.3,0.1

Type RM Length L Ch R = 1 ,72458   ,211,211,211
XS GIS Cut Line= 2
2366918.68392391689192.3908337512367543.32941035 688820.80757941
#Sta/Elev= 30
       0 2844.95    26.8 2843.06    53.2 2838.64    58.9 2836.42    92.3 2813.54
   108.8 2803.73   113.4 2802.64   127.4 2804.51   149.3 2802.65   173.9 2792.82
   194.1 2786.67   211.2 2782.79   225.2 2777.18   236.3 2773.82   242.7 2772.58
   308.9 2772.43   322.9 2772.63   330.3 2773.88   346.1 2776.79   360.1 2777.28
   392.7 2780.99   467.4 2783.13   597.5 2790.99   600.9 2792.02   607.5 2796.55
   619.2 2802.01   633.8 2803.68   645.4 2807.34   679.1 2810.26   726.8  2812.3
#Mann= 7 ,-1,0
       0      .1       0     190     .06       0     210      .1       0
   236.3    .045       0   330.3      .1       0     420     .08       0
     530     .05       0
Bank Sta=236.3,330.3
XS Rating Curve= 0 ,0
Exp/Cntr=0.3,0.1