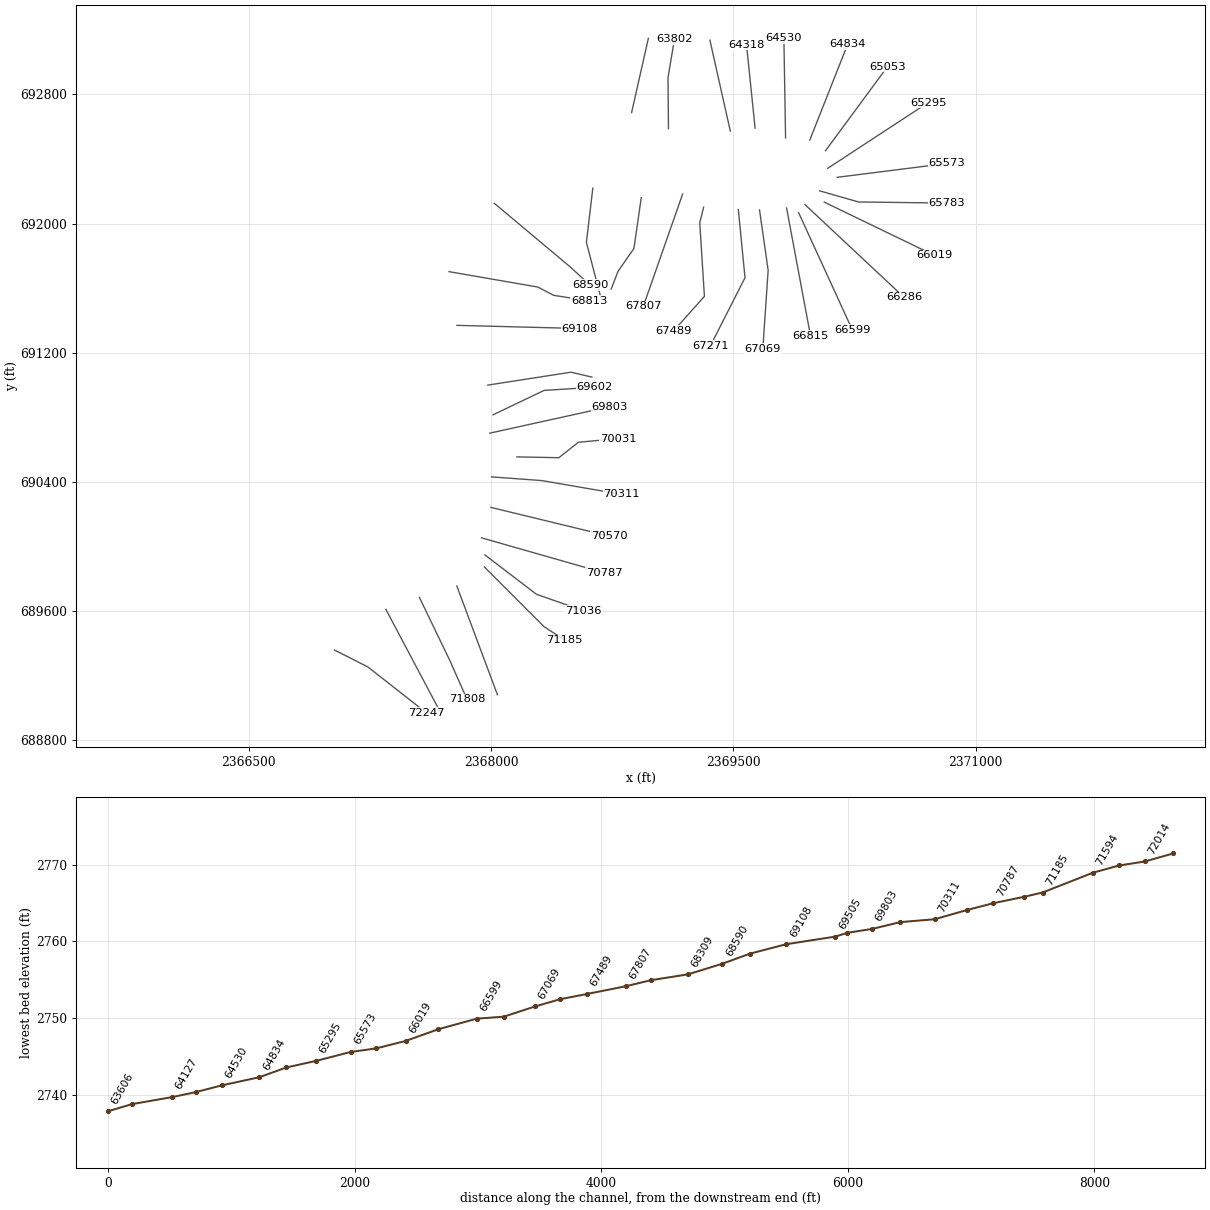
HEC-RAS study LAURELFK.prj: LAURELFK

--- LAURELFK.g01 (geometry) --- (continued)

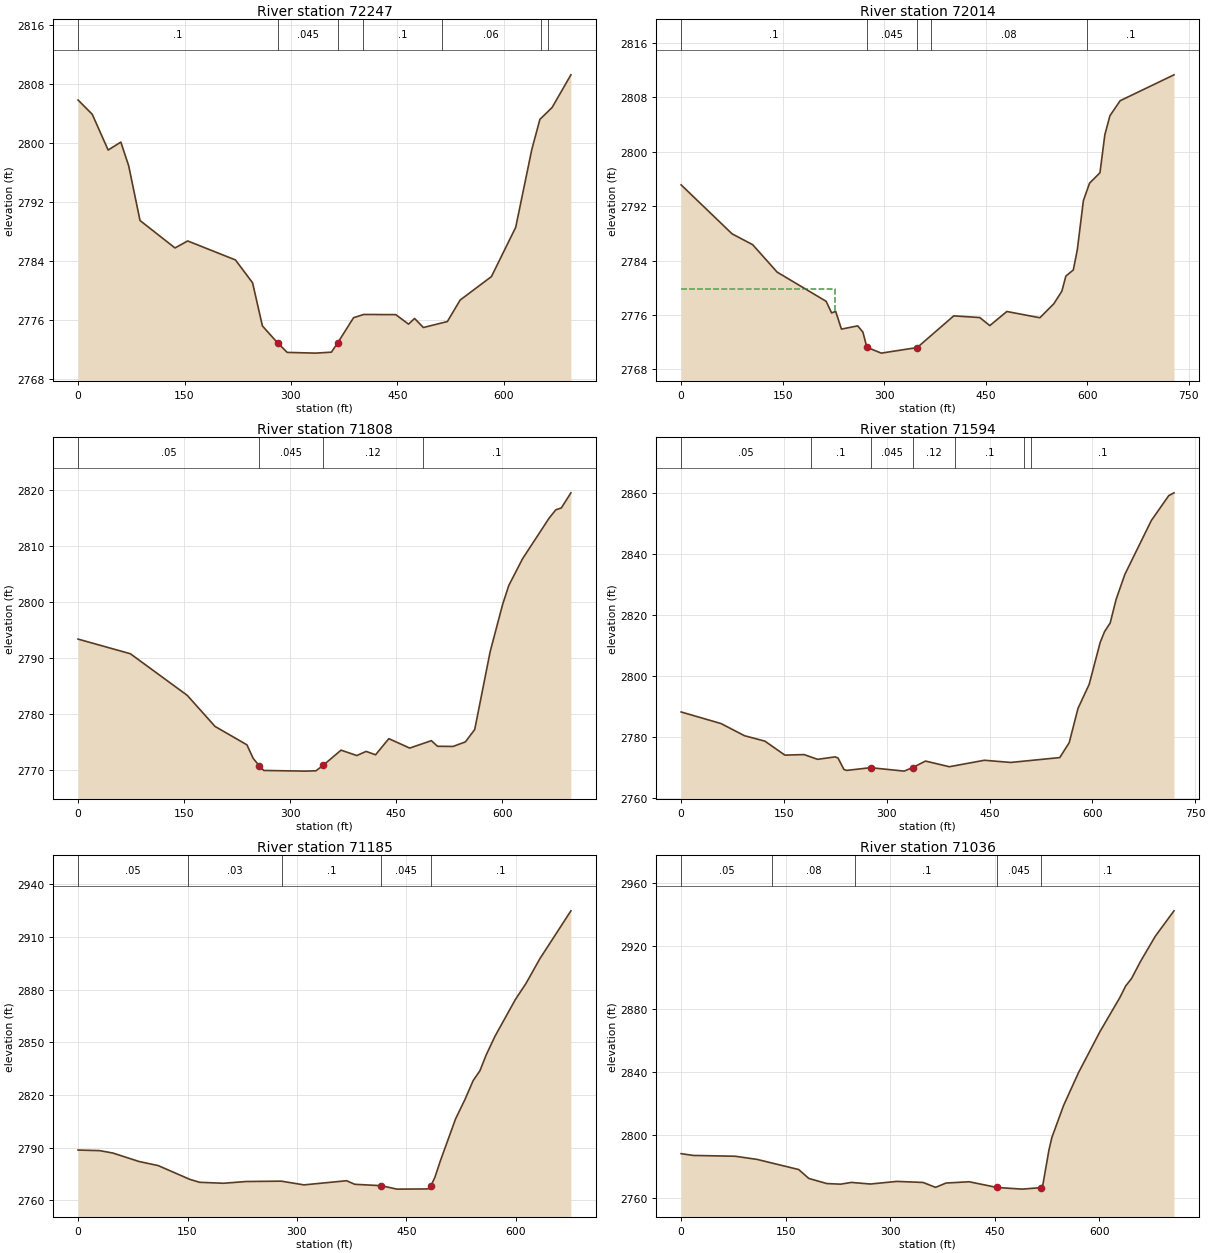
Type RM Length L Ch R = 1 ,72247   ,232.5,232.5,232.5
XS GIS Cut Line= 3
2367030.36649877689359.2975130292367237.40052922689254.226188268
2367601.10896109688968.854957112
#Sta/Elev= 30
       0 2805.84      20  2803.9    42.4 2799.04    60.3 2800.12    71.4 2796.88
    87.3 2789.47   136.6 2785.74   154.5 2786.69   221.8 2784.11   245.9 2781.01
   259.8 2775.14   281.5 2772.81   294.7 2771.55   334.6 2771.45     357 2771.58
   365.9 2772.85   388.2 2776.26   402.3  2776.7   447.7 2776.68   465.7 2775.39
   474.2 2776.16   486.6 2774.93   520.4 2775.74   538.4 2778.66   582.5 2781.85
   616.7 2788.54   639.4 2799.12   650.8 2803.21   667.9 2804.81   694.5 2809.26
#Mann= 7 ,-1,0
       0      .1       0   281.5    .045       0   365.9     .07       0
  402.17      .1       0  512.17     .06       0  652.17      .1       0
  662.17     .08       0
Bank Sta=281.5,365.9
XS Rating Curve= 0 ,0
Exp/Cntr(USF)=0,0
Exp/Cntr=0.3,0.1

Type RM Length L Ch R = 1 ,72014   ,206.6,206.6,206.6
XS GIS Cut Line= 2
2367348.87793781689610.5571378322367689.82720614 688966.85152072
#Sta/Elev= 30
       0 2795.14    75.4 2787.93   105.7 2786.35   141.9 2782.31   214.3 2778.02
   222.4 2776.31   228.4 2776.54   236.9 2773.93   260.9 2774.41   268.6  2773.5
   274.5 2771.26   295.8  2770.4   348.9 2771.22   402.9 2775.88   441.4 2775.63
   456.2 2774.45   481.4 2776.52   530.2  2775.6   550.9 2777.67   562.7 2779.51
   568.6 2781.73   579.6 2782.63   585.5 2785.59   594.5 2792.83   603.6 2795.39
     619 2796.92   626.2 2802.51   633.7  2805.3   648.8 2807.51   728.4 2811.32
#Mann= 5 ,-1,0
       0      .1       0   274.5    .045       0   348.9      .1       0
     370     .08       0     600      .1       0
#XS Ineff= 2 , 0
          227.86 2779.78
Permanent Ineff=
       F       F
Bank Sta=274.5,348.9
XS Rating Curve= 0 ,0
Exp/Cntr(USF)=0,0
Exp/Cntr=0.3,0.1

Type RM Length L Ch R = 1 ,71808   ,213.2,213.2,213.2
XS GIS Cut Line= 3
2367556.57294927689684.3608415612367742.18981932689299.343751219
2367852.01678527 689052.86807922
#Sta/Elev= 30
       0 2793.42      74 2790.81   154.5 2783.39   193.8 2777.85   238.9 2774.57
   247.8 2772.15   256.3 2770.84   262.7    2770   321.5 2769.88   336.6 2769.94
   346.6  2770.9   372.1 2773.62   394.3 2772.66   407.6  2773.4   420.9 2772.79
   439.7 2775.67   469.2 2773.99   499.9 2775.31   508.6 2774.31   530.5 2774.28
     548 2775.09   561.2  2777.3   583.1 2791.21   600.6 2799.56   609.4 2802.98
   628.9 2807.75   666.3 2814.96   675.9 2816.47   683.8 2816.81   697.3  2819.5
#Mann= 4 ,-1,0
       0     .05       0   256.3    .045       0   346.6     .12       0
  487.42      .1       0
Bank Sta=256.3,346.6
XS Rating Curve= 0 ,0
Exp/Cntr=0.3,0.1

Type RM Length L Ch R = 1 ,71594   ,409,409,409
XS GIS Cut Line= 2
2367787.90435119689755.7329048322368039.49354937689081.985560563
#Sta/Elev= 30
       0 2788.29    58.2  2784.5    92.5 2780.52   122.3 2778.74   151.4 2774.18
   179.4 2774.35   199.1  2772.8   224.8  2773.6     229  2773.2   237.6 2769.46
   241.8 2769.18   276.5 2770.07   325.5 2768.94   337.8 2770.09   356.6 2772.23
   391.3 2770.38   442.5 2772.49   480.9 2771.78   552.5 2773.37   566.3 2778.25
   579.1 2789.45   595.4 2797.31   611.5 2811.04   617.8 2814.54   626.1  2817.4
   634.7 2825.09   647.5 2833.29   686.1  2850.9   711.5 2859.04   719.2 2859.97
#Mann= 7 ,-1,0
       0     .05       0     190      .1       0   276.5    .045       0
   337.8     .12       0     400      .1       0     500     .12       0
     510      .1       0
Bank Sta=276.5,337.8
XS Rating Curve= 0 ,0
Exp/Cntr(USF)=0,0
Exp/Cntr=0.3,0.1

Type RM Length L Ch R = 1 ,71185   ,149.4,149.4,149.4
XS GIS Cut Line= 3
2367958.50303527689873.3966775592368327.45662254689504.276839636
2368455.82261912689420.061623758
#Sta/Elev= 30
       0 2788.63    29.6  2788.3    47.6 2786.94    83.4 2782.13   109.9 2779.76
     153 2771.95   166.5 2770.26   199.3  2769.7   230.4  2770.7   278.5  2770.9
   309.6 2768.78   367.9 2771.15   379.2 2769.11   415.4 2768.33   436.9 2766.36
   477.6 2766.46     481 2766.67  483.72 2768.39     489  2773.1   496.3 2782.23
   517.3 2806.37   530.4 2817.62   541.4  2828.2   550.7 2833.83   559.3 2842.85
   571.3 2853.45   599.3 2874.43   613.7 2883.48   632.8 2897.63   675.4 2924.97
#Mann= 5 ,-1,0
       0     .05       0     150     .03       0     280      .1       0
   415.4    .045       0  483.72      .1       0
Bank Sta=415.4,483.72
XS Rating Curve= 0 ,0
Exp/Cntr=0.3,0.1

Type RM Length L Ch R = 1 ,71036   ,249.2,249.2,249.2
XS GIS Cut Line= 3
2367962.16673277689947.7607530432368281.36628742689704.050087191
2368569.53527575689603.330829136
#Sta/Elev= 30
       0 2788.28    17.5 2787.16    77.5 2786.65   108.9 2784.65   168.6 2778.22
   183.1 2772.58   208.9 2769.34   228.7 2768.94   244.1 2770.05   271.5 2769.04
   309.5  2770.7     347 2770.03   364.9 2766.93     380 2769.66   413.1 2770.47
   453.2 2766.84   489.3  2765.8     516 2766.74     519 2768.96   527.5 2790.48
   531.7 2798.49   548.6  2818.9   569.8 2839.53   600.7 2865.65   629.2 2887.21
   637.6 2894.58   646.1 2899.38   658.8 2910.11     680 2926.09   706.9 2942.25
#Mann= 5 ,-1,0
       0     .05       0     130     .08       0     250      .1       0
   453.2    .045       0     516      .1       0
Bank Sta=453.2,516
XS Rating Curve= 0 ,0
Exp/Cntr(USF)=0,0
Exp/Cntr=0.3,0.1

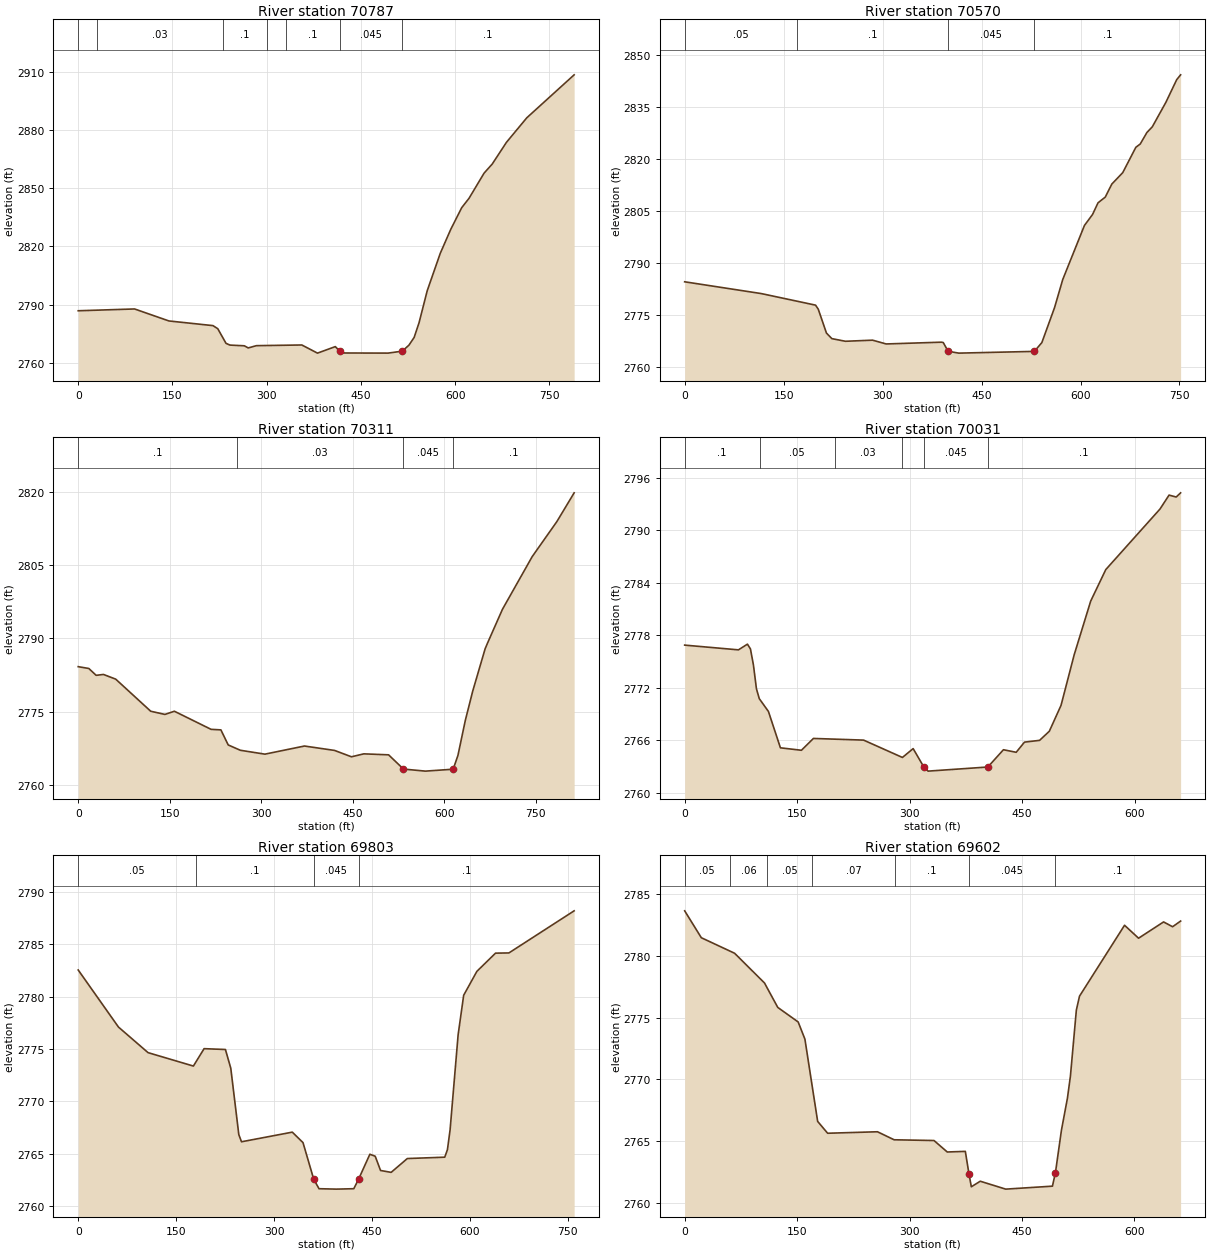
Type RM Length L Ch R = 1 ,70787   ,217.1,217.1,217.1
XS GIS Cut Line= 2
     2367941.878      690053.4652368701.07989577689836.903315587
#Sta/Elev= 30
       0 2786.82    89.7 2787.75   144.5 2781.56   214.5 2779.16   222.2 2777.56
   235.3 2770.01   241.6 2769.12   264.4 2768.75   270.7 2767.66   283.7 2768.82
     356 2769.17   380.9 2764.97   409.3 2768.33   416.3 2765.97   423.9 2765.04
   493.2 2764.98   515.82765.974   526.4 2769.04   534.8 2773.08   542.6 2780.64
   555.6 2797.16   576.4 2816.48     593 2828.77   610.5 2839.99   622.2 2844.85
   646.1  2857.8   659.1 2862.51   681.7 2873.69   714.1 2886.35   789.5 2908.52
#Mann= 7 ,-1,0
       0     .05       0      30     .03       0     230      .1       0
     300     .08       0     330      .1       0   416.3    .045       0
   515.8      .1       0
Bank Sta=416.3,515.8
XS Rating Curve= 0 ,0
Exp/Cntr=0.3,0.1

Type RM Length L Ch R = 1 ,70570   ,258.7,258.7,258.7
XS GIS Cut Line= 2
2367999.35171102690242.1054270272368729.87719383690064.914139709
#Sta/Elev= 30
       0  2784.6   116.1 2781.21   198.4 2777.88   202.5 2776.71   214.9 2769.84
   223.1 2768.24   243.7 2767.48   284.8  2767.8   305.4 2766.71     389 2767.22
   391.9 2767.12   399.32764.596   415.5 2764.07     530 2764.57   541.4 2767.11
   560.6 2777.16     573 2785.23   605.9 2800.81   618.2 2803.97   626.5 2807.33
   637.5 2808.98   647.4 2812.72     664 2816.02   683.8  2823.3   690.5 2824.26
   700.6 2827.57   708.8 2829.21   729.4 2836.27   745.8 2842.79   751.7 2844.17
#Mann= 4 ,-1,0
       0     .05       0     170      .1       0   399.3    .045       0
     530      .1       0
Bank Sta=399.3,530
XS Rating Curve= 0 ,0
Exp/Cntr(USF)=0,0
Exp/Cntr=0.3,0.1

Type RM Length L Ch R = 1 ,70311   ,280.2,280.2,280.2
XS GIS Cut Line= 3
2368002.85033294690431.1608578182368314.66547394690408.216286137
2368807.96664013690323.083396312
#Sta/Elev= 30
       0 2784.23    17.4 2783.86    29.4 2782.46    41.4 2782.64    61.5 2781.68
   118.9 2775.12   142.2 2774.47   157.7 2775.12   217.9 2771.42     234 2771.31
     246 2768.23     266 2767.14   306.2 2766.35     371 2768.01   420.4 2767.11
   448.1 2765.81   468.4 2766.41     509 2766.21   533.4  2763.3   569.3 2762.88
   614.9 2763.27   622.7 2766.08   634.9 2773.29     647 2779.25   667.3 2787.88
   671.4 2789.09   695.7 2795.95   744.5 2806.72     785 2813.89   813.3 2819.76
#Mann= 4 ,-1,0
       0      .1       0     260     .03       0   533.4    .045       0
   614.9      .1       0
Bank Sta=533.4,614.9
XS Rating Curve= 0 ,0
Exp/Cntr=0.3,0.1

Type RM Length L Ch R = 1 ,70031   ,227.5,227.5,227.5
XS GIS Cut Line= 4
2368160.50252391690554.925764622 2368419.8546134690549.889801719
2368540.71772307690645.573096871 2368787.4799053690668.234929934
#Sta/Elev= 30
       0 2776.88    71.7 2776.34    83.7 2776.99    87.7 2776.45    91.7 2774.61
    95.7  2771.9    99.5 2770.77   111.7 2769.31   127.7 2765.16   155.7 2764.88
   171.7 2766.23   238.6 2766.04   290.4 2764.06   304.7 2765.07   318.9 2762.98
   324.6  2762.5   404.3 2762.97   425.1 2764.94   442.1 2764.65   453.2 2765.81
   473.3 2766.01   486.3 2767.05   501.9    2770   519.5 2775.79   541.5 2781.91
   561.6  2785.5   633.9 2792.41     646    2794   655.5 2793.78   661.4 2794.26
#Mann= 6 ,-1,0
       0      .1       0     100     .05       0     200     .03       0
   289.4      .1       0   318.9    .045       0   404.3      .1       0
Bank Sta=318.9,404.3
XS Rating Curve= 0 ,0
Exp/Cntr(USF)=0,0
Exp/Cntr=0.3,0.1

Type RM Length L Ch R = 1 ,69803   ,201.3,201.3,201.3
XS GIS Cut Line= 2
2367991.91561967 690701.872666472368733.68367002690865.299572273
#Sta/Elev= 30
       0 2782.54    61.7 2777.09     107 2774.65   176.4 2773.37   192.8 2775.03
   225.5 2774.95   233.7 2773.16     246 2766.82   250.1 2766.14   327.9 2767.06
   344.3 2766.06   360.7 2762.57   368.8 2761.66   395.3 2761.62   422.1 2761.66
   429.3 2762.55   446.7 2764.95   454.9 2764.76   463.1  2763.4   479.3 2763.22
   504.1 2764.54   561.4 2764.67   565.5 2765.38   569.6 2767.29   581.9 2776.36
   590.4 2780.13   610.6 2782.41   639.2 2784.15   659.7 2784.17   759.6 2788.19
#Mann= 4 ,-1,0
       0     .05       0     180      .1       0   360.7    .045       0
   429.3      .1       0
Bank Sta=360.7,429.3
XS Rating Curve= 0 ,0
Exp/Cntr=0.3,0.1

Type RM Length L Ch R = 1 ,69602   ,96.6,96.6,96.6
XS GIS Cut Line= 3
2368012.10506597690815.4053575012368328.25162598690966.484244584
2368638.80267165690986.068544761
#Sta/Elev= 30
       0 2783.67    22.2 2781.49    66.6 2780.23   106.5 2777.82   124.2 2775.84
   151.4 2774.66   160.4 2773.27   177.4  2766.6   190.7 2765.64   257.2 2765.76
   279.4 2765.11   332.6 2765.05   350.3 2764.12   374.4 2764.17   379.2 2762.37
   382.4  2761.3   394.3 2761.75   428.3 2761.11   490.6 2761.35   494.6 2762.44
   502.6 2765.88   510.6 2768.48   514.6 2770.27   522.5 2775.62   526.7 2776.75
   586.8  2782.5   605.5 2781.45   638.9 2782.77   650.9 2782.38   661.6 2782.84
#Mann= 7 ,-1,0
       0     .05       0      60     .06       0     110     .05       0
     170     .07       0     280      .1       0   379.2    .045       0
   494.6      .1       0
Bank Sta=379.2,494.6
XS Rating Curve= 0 ,0
Exp/Cntr(USF)=0,0
Exp/Cntr=0.3,0.1

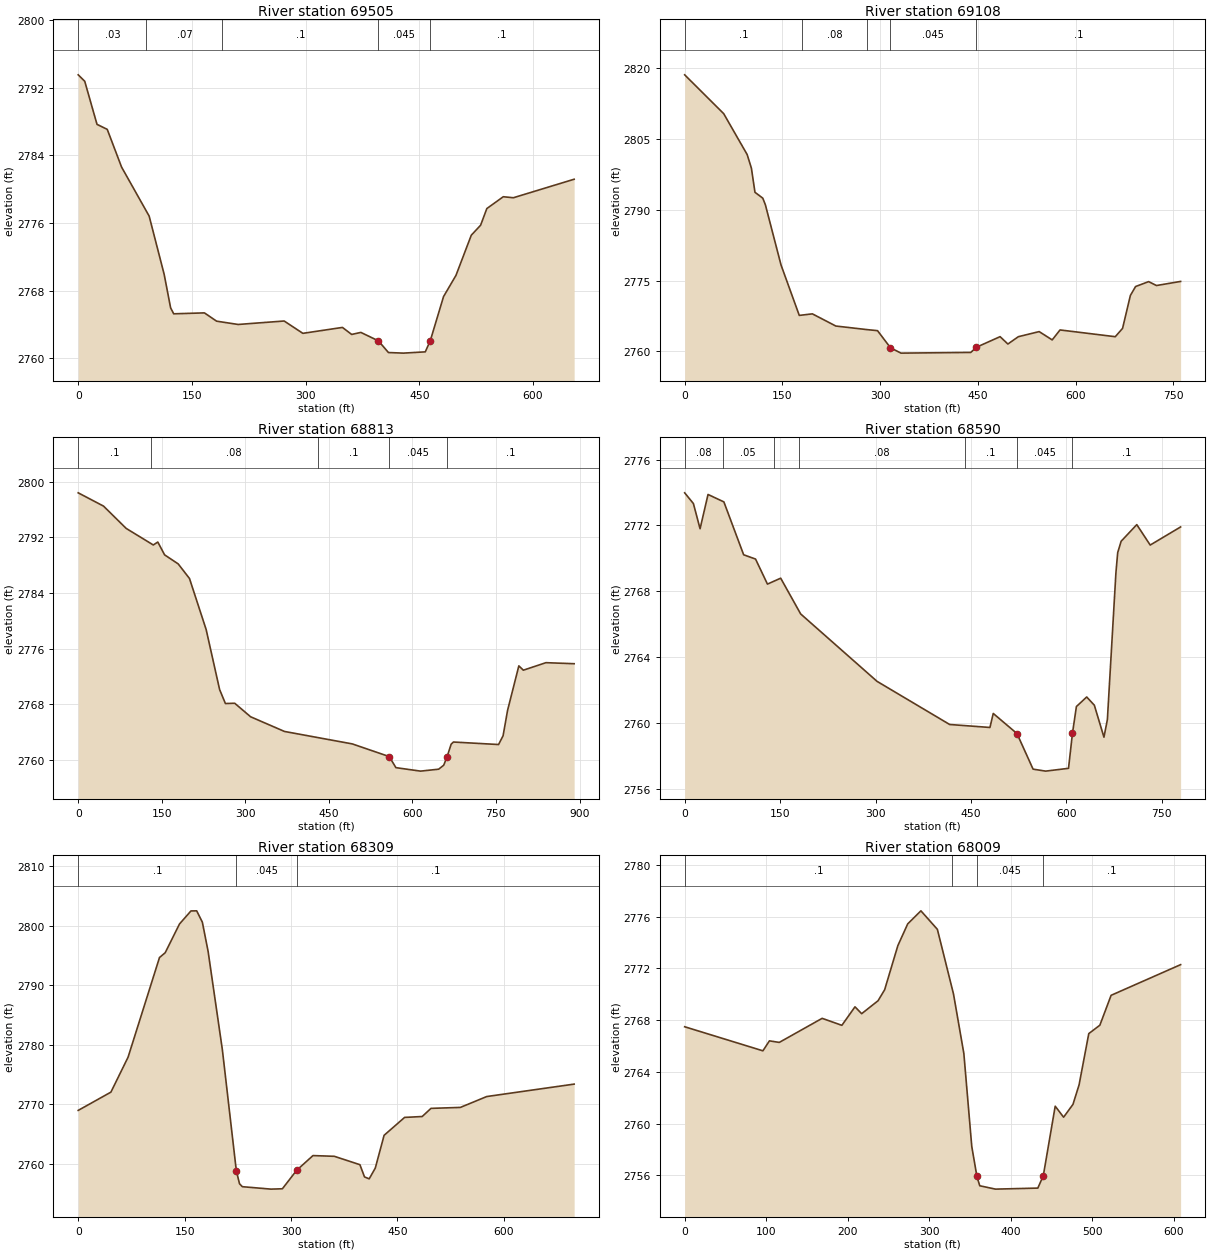
Type RM Length L Ch R = 1 ,69505   ,397.8,397.8,397.8
XS GIS Cut Line= 3
2367979.69702939690999.3042664042368494.69915774691079.339250488
2368624.26450146691048.988473733
#Sta/Elev= 30
       0 2793.54     8.6 2792.78    24.8 2787.68    38.3 2787.09    57.2 2782.63
    93.6 2776.83   113.4 2769.94   121.9 2765.98     126 2765.27   166.5 2765.38
   182.6  2764.4     211 2764.01   271.7 2764.42   296.4 2762.96   348.6 2763.66
   360.8 2762.83   372.9 2763.07   396.1 2762.07   409.3 2760.69     429 2760.62
   457.9 2760.77   464.5 2762.09     482 2767.31   498.4 2769.82   518.6 2774.57
   530.9 2775.75   539.1 2777.72   560.8 2779.12   574.1    2779   654.3 2781.19
#Mann= 5 ,-1,0
       0     .03       0      90     .07       0     190      .1       0
   396.1    .045       0   464.5      .1       0
Bank Sta=396.1,464.5
XS Rating Curve= 0 ,0
Exp/Cntr=0.3,0.1

Type RM Length L Ch R = 1 ,69108   ,295,295,295
XS GIS Cut Line= 2
2367788.28449252691369.3612768042368549.27444227691349.776976626
#Sta/Elev= 30
       0 2818.59    59.9 2810.36    95.9  2801.7   102.4 2798.82   107.9  2793.7
   119.9 2792.46   123.9 2791.04   147.9  2778.3   175.9 2767.62     196 2767.95
     232 2765.37     280 2764.61     296 2764.39   315.9 2760.76     332 2759.63
   439.2 2759.78   447.4 2760.85   484.1 2763.12   496.1 2761.56   512.1 2763.11
   544.1 2764.19   564.1 2762.43   576.1 2764.54   660.9 2763.11   672.1 2764.87
   684.1 2771.85   692.1 2773.74   712.1 2774.78   724.1 2773.95   761.2 2774.82
#Mann= 5 ,-1,0
       0      .1       0     180     .08       0     280      .1       0
   315.9    .045       0   447.4      .1       0
Bank Sta=315.9,447.4
XS Rating Curve= 0 ,0
Exp/Cntr(USF)=0,0
Exp/Cntr=0.3,0.1

Type RM Length L Ch R = 1 ,68813   ,223.1,223.1,223.1
XS GIS Cut Line= 4
2367739.32750368691701.9046597732368289.53833249691606.553513359
2368387.47872696691555.3356860712368606.24079322691520.572196324
#Sta/Elev= 30
       0 2798.38    45.5 2796.47    86.1 2793.27   134.8 2790.89   142.9 2791.31
   155.1 2789.47   179.5 2788.17   199.8 2786.07   229.7 2778.74   253.9 2770.11
   264.3 2768.11     281 2768.15   309.5 2766.21   370.3  2764.1   492.1 2762.31
   558.4 2760.49   570.4  2758.9   614.7  2758.4   647.2 2758.68   656.2 2759.25
   662.2 2760.45   669.6 2762.28   673.7 2762.58   754.7 2762.22   762.8 2763.48
   770.9 2767.14   791.1 2773.52   799.2  2772.9   839.7 2773.98   890.4 2773.83
#Mann= 5 ,-1,0
       0      .1       0     130     .08       0     430      .1       0
   558.4    .045       0   662.2      .1       0
Bank Sta=558.4,662.2
XS Rating Curve= 0 ,0
Exp/Cntr=0.3,0.1

Type RM Length L Ch R = 1 ,68590   ,280.6,280.6,280.6
XS GIS Cut Line= 3
2368020.49833748692124.7557122162368487.72378457691733.069708669
2368613.33837804691618.821383015
#Sta/Elev= 30
       0 2773.98    13.7 2773.33    24.2  2771.8    36.7 2773.88    61.6 2773.43
    92.7 2770.22   111.4 2769.96   130.1 2768.44   150.9  2768.8   182.3 2766.63
   302.3 2762.54   416.5 2759.92   479.8 2759.74     485 2760.59   522.3 2759.37
   547.6 2757.21   567.3 2757.09   603.3 2757.26   609.5 2759.38   615.7 2761.01
   631.9 2761.59   643.9 2761.09     659 2759.15   664.4 2760.22   677.8 2769.12
   680.6 2770.35     686 2771.04   710.6 2772.05   731.7 2770.81   779.5 2771.91
#Mann= 7 ,-1,0
       0     .08       0      60     .05       0     140     .03       0
     180     .08       0     440      .1       0   522.3    .045       0
   609.5      .1       0
Bank Sta=522.3,609.5
XS Rating Curve= 0 ,0
Exp/Cntr(USF)=0,0
Exp/Cntr=0.3,0.1

Type RM Length L Ch R = 1 ,68309   ,300.3,300.3,300.3
XS GIS Cut Line= 3
2368630.09330492 692218.958178752368590.16468284691883.598436653
2368681.55512362691533.957429852
#Sta/Elev= 30
       0 2768.94    46.1 2772.01    70.3 2777.89   114.6 2794.65   122.6 2795.45
   142.8 2800.29   158.9 2802.48     167  2802.5     175 2800.59   183.1 2795.69
   203.2 2779.15   222.9 2758.78   227.4  2756.6   231.4 2756.11   271.7  2755.7
   287.8 2755.76   307.9 2758.86   330.9 2761.34     361 2761.22   397.1 2759.81
   403.6 2757.75   410.2 2757.43   418.8 2759.25   431.2 2764.75   460.1 2767.76
   484.9 2767.91   497.3 2769.28   538.7 2769.44   575.9 2771.27   699.1 2773.36
#Mann= 3 ,-1,0
       0      .1       0   222.9    .045       0   307.9      .1       0
Bank Sta=222.9,307.9
XS Rating Curve= 0 ,0
Exp/Cntr=0.3,0.1

Type RM Length L Ch R = 1 ,68009   ,201.6,201.6,201.6
XS GIS Cut Line= 4
2368929.90195079 692160.117076252368884.57828467691845.369394828
2368786.37700806691704.3624335512368743.57132339691593.571249691
#Sta/Elev= 30
       0 2767.49      96 2765.63     104  2766.4   116.1 2766.28   168.7 2768.14
   192.9  2767.6     209 2769.03   217.2  2768.5   237.3  2769.5   245.4 2770.35
   261.6 2773.76   273.7 2775.44   289.9 2776.45   310.1 2775.02   329.9 2770.02
   342.6 2765.42   352.3 2758.24   358.6 2755.93   362.1  2755.2   381.4 2754.94
   433.4 2755.02   440.1 2755.98   454.7 2761.35     465  2760.5   476.5 2761.49
     484    2763   495.9 2766.96   509.5 2767.61   523.3 2769.92   608.6 2772.29
#Mann= 4 ,-1,0
       0      .1       0  327.99     .08       0   358.6    .045       0
   440.1      .1       0
Bank Sta=358.6,440.1
XS Rating Curve= 0 ,0
Exp/Cntr(USF)=0,0
Exp/Cntr=0.3,0.1

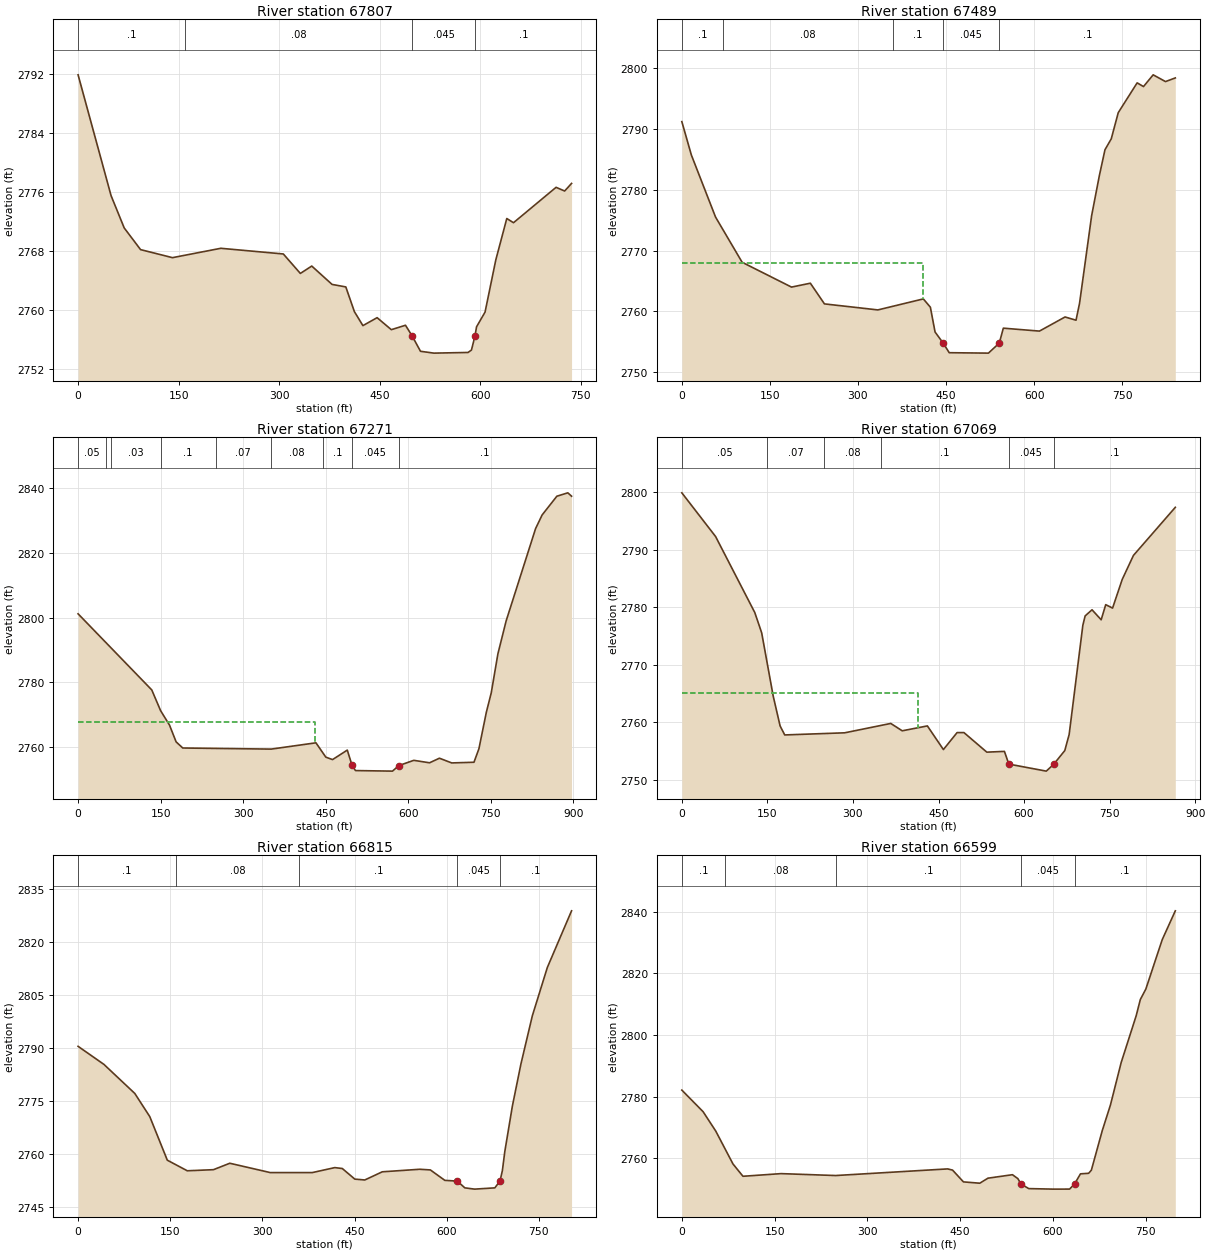
Type RM Length L Ch R = 1 ,67807   ,318,318,318
XS GIS Cut Line= 2
2369185.92029774692182.1220398432368942.84298008691487.380734923
#Sta/Elev= 30
       0 2791.91    49.2 2775.52    68.8 2771.14    93.2  2768.2   140.8 2767.11
   212.9 2768.38   306.1 2767.61   331.5 2764.97   348.5 2765.97   378.8 2763.48
   399.3 2763.14   412.1 2759.79   424.8 2757.89     446 2758.97   467.2 2757.34
   488.3 2757.94   498.1 2756.51   510.7 2754.41   530.7 2754.16   581.6 2754.25
   586.7 2754.58   591.9 2756.47   594.3 2757.73     607 2759.73     623  2766.8
   639.4 2772.42   649.4 2771.85   712.9 2776.65   725.7 2776.15     736 2777.18
#Mann= 4 ,-1,0
       0      .1       0     160     .08       0   498.1    .045       0
   591.9      .1       0
Bank Sta=498.1,591.9
XS Rating Curve= 0 ,0
Exp/Cntr=0.3,0.1

Type RM Length L Ch R = 1 ,67489   ,217.7,217.7,217.7
XS GIS Cut Line= 4
2369316.12718728692100.8962650492369292.08729851692003.718258385
2369321.05752345691548.589879497 2369131.3404669691336.737141651
#Sta/Elev= 30
       0 2791.18    16.2  2785.7    57.4  2775.5   102.7 2768.07   186.8 2763.99
   218.9 2764.63   242.9 2761.23   333.9 2760.24   411.3 2762.05   423.3 2760.69
   431.3 2756.61   445.2 2754.78   455.4 2753.21   522.2 2753.14  540.69 2754.79
   547.6 2757.24   609.1 2756.76   652.7 2759.08   671.4 2758.55   677.4 2761.33
     698 2775.74   711.1 2782.29   720.7 2786.56   731.4 2788.35   743.3 2792.65
   775.5 2797.55   786.3 2796.94   802.8 2798.87   823.8 2797.76   840.5 2798.36
#Mann= 5 ,-1,0
       0      .1       0      70     .08       0  360.11      .1       0
   445.2    .045       0  540.69      .1       0
#XS Ineff= 2 , 0
          410.97 2767.96
Permanent Ineff=
       F       F
Bank Sta=445.2,540.69
XS Rating Curve= 0 ,0
Exp/Cntr(USF)=0,0
Exp/Cntr=0.3,0.1

Type RM Length L Ch R = 1 ,67271   ,202.2,202.2,202.2
XS GIS Cut Line= 3
2369530.95882014692086.4402272362369572.37416979691664.386068557
2369358.31382125691243.092231874
#Sta/Elev= 30
       0 2801.18   133.9  2777.6     150 2771.16   166.1 2766.72   178.1 2761.52
   190.2 2759.62   350.9 2759.28   432.2 2761.23   450.1 2756.79   462.3 2756.03
   489.1 2758.97   497.92754.205     504 2752.63   571.3 2752.46   582.62754.171
     610  2755.8   638.6 2755.04   656.5 2756.46   678.9    2755   719.3 2755.21
   728.3  2759.4   741.7 2770.64   750.7 2776.72   762.8 2788.81   777.7 2798.96
   831.2 2827.55   843.1 2831.79   869.9  2837.6   889.8 2838.65   896.6 2837.61
#Mann= 9 ,-1,0
       0     .05       0      50     .08       0      60     .03       0
     150      .1       0     250     .07       0     350     .08       0
  444.08      .1       0   497.9    .045       0   582.6      .1       0
#XS Ineff= 2 , 0
          431.32 2767.76
Permanent Ineff=
       F       F
Bank Sta=497.9,582.6
XS Rating Curve= 0 ,0
Exp/Cntr=0.3,0.1

Type RM Length L Ch R = 1 ,67069   ,253.9,253.9,253.9
XS GIS Cut Line= 3
2369662.25770893692083.7528658332369715.63235224 691710.89698667
2369682.77840475691223.427976339
#Sta/Elev= 30
       0  2799.9    59.2  2792.3   127.9 2779.09     140 2775.56   160.2 2764.56
   172.3 2759.37   180.4 2757.81   285.5 2758.18   366.3 2759.81   386.4 2758.53
   430.5 2759.38   458.6 2755.27   482.6 2758.22   494.6 2758.22   534.7 2754.82
   565.6 2754.95   573.32752.742     639 2751.52   652.12752.722   671.4 2755.09
   679.1  2757.9   703.1 2776.89   707.1  2778.5   719.2 2779.57   735.2 2777.83
   743.2 2780.46   755.2 2779.86   772.1 2784.84   791.8 2789.02   865.2 2797.38
#Mann= 6 ,-1,0
       0     .05       0     150     .07       0     250     .08       0
     350      .1       0   573.3    .045       0   652.1      .1       0
#XS Ineff= 2 , 0
          414.43 2765.05
Permanent Ineff=
       F       F
Bank Sta=573.3,652.1
XS Rating Curve= 0 ,0
Exp/Cntr(USF)=0,0
Exp/Cntr=0.3,0.1

Type RM Length L Ch R = 1 ,66815   ,216.8,216.8,216.8
XS GIS Cut Line= 2
2369829.83518539692095.858258437 2369977.5966093691306.470549532
#Sta/Elev= 30
       0 2790.59      42 2785.49    92.3 2777.26   116.7  2770.7   145.2 2758.38
   177.7 2755.38   220.3 2755.69   246.9 2757.51   312.8 2754.87   381.2 2754.87
   417.8 2756.28     430 2756.02   450.4 2753.02   466.6 2752.78   495.1 2755.09
   556.2 2755.81   573.3 2755.62   596.9 2752.67   617.2 2752.46   629.4 2750.55
   645.3 2750.19   678.3 2750.55   686.7 2752.52   690.5 2755.41   694.5 2760.87
   706.7 2773.61   720.7  2785.6   739.3 2799.25   763.7 2812.91   803.1 2828.93
#Mann= 5 ,-1,0
       0      .1       0     160     .08       0     360      .1       0
   617.2    .045       0   686.7      .1       0
Bank Sta=617.2,686.7
XS Rating Curve= 0 ,0
Exp/Cntr=0.3,0.1

Type RM Length L Ch R = 1 ,66599   ,312.9,312.9,312.9
XS GIS Cut Line= 2
2369904.36077247692066.9517625492370236.73432406691341.773104554
#Sta/Elev= 30
       0 2782.08    34.4 2775.06    54.8 2768.79    82.7  2758.1    98.8 2754.11
   160.4 2754.97   248.6 2754.35   429.6  2756.5   437.6 2756.12   455.2 2752.29
   481.6 2751.86   494.8 2753.49   534.4 2754.62   543.2 2753.35   548.2 2751.59
   560.8 2750.11   600.4 2749.94   626.8 2749.95   634.8 2751.59   644.4  2754.9
   657.6 2755.08     662 2756.09   679.6 2768.91   692.8 2777.22   710.2 2791.03
   734.4 2806.17   741.2  2811.5     750 2814.84   776.6 2830.93   797.7 2840.26
#Mann= 5 ,-1,0
       0      .1       0      70     .08       0     250      .1       0
   548.2    .045       0   634.8      .1       0
Bank Sta=548.2,634.8
XS Rating Curve= 0 ,0
Exp/Cntr(USF)=0,0
Exp/Cntr=0.3,0.1

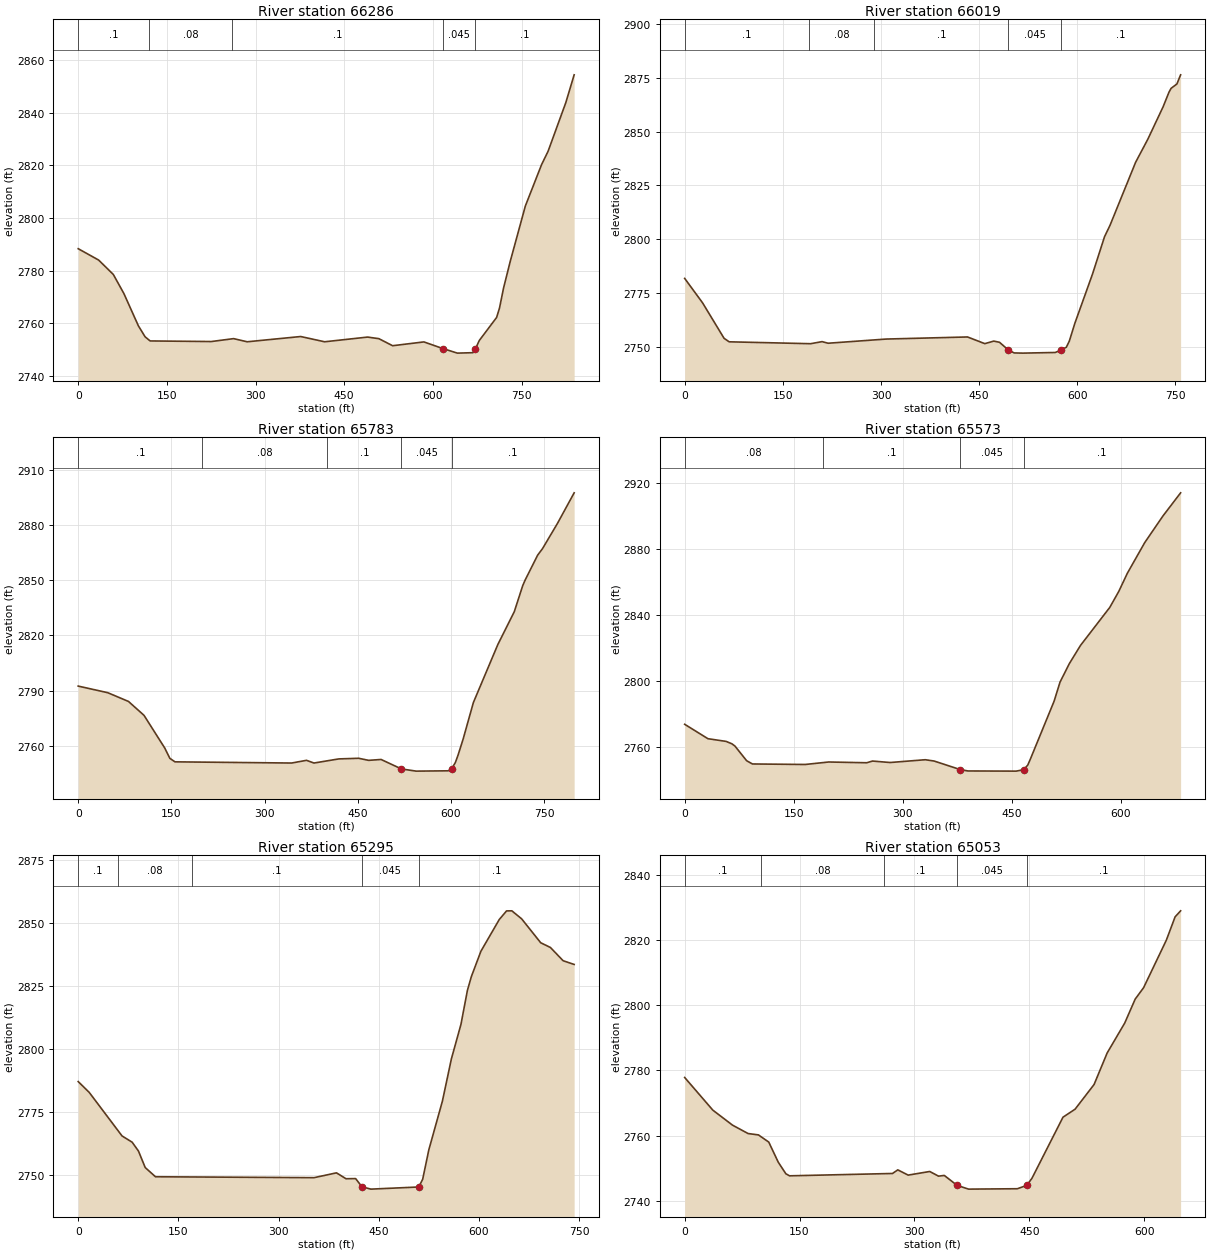
Type RM Length L Ch R = 1 ,66286   ,266.1,266.1,266.1
XS GIS Cut Line= 2
2369943.83115883692116.8222385152370556.38105312691543.495364141
#Sta/Elev= 30
       0 2788.32    34.6 2783.99    59.4 2778.51    77.2 2771.28   101.9 2758.91
   113.2 2754.76   121.7  2753.2   225.1 2752.97   262.9 2754.08   285.8 2752.88
   376.4 2754.88   416.9 2752.88   489.6 2754.67   508.7 2754.06   531.9 2751.38
   584.8 2752.83   616.9  2750.3   641.5 2748.56   667.9 2748.73   671.72750.039
   678.5 2753.36   707.8 2762.13   712.7  2765.7   719.5 2773.27   731.2 2783.77
   756.5 2804.61   783.9 2820.33   794.9 2825.41   824.8 2843.88     839 2854.52
#Mann= 5 ,-1,0
       0      .1       0     120     .08       0     260      .1       0
   616.9    .045       0   671.7      .1       0
Bank Sta=616.9,671.7
XS Rating Curve= 0 ,0
Exp/Cntr=0.3,0.1

Type RM Length L Ch R = 1 ,66019   ,236.3,236.3,236.3
XS GIS Cut Line= 2
2370062.99360391692132.4192802852370745.36657723691802.563710155
#Sta/Elev= 30
       0 2781.76    27.3 2770.42    60.2 2753.92      68 2752.29   192.4 2751.41
     210 2752.37   219.2 2751.63   307.9 2753.57   432.3 2754.54   458.6 2751.44
   472.3 2752.61   481.1 2752.08   494.4 2748.56   503.5 2747.12   516.7 2747.03
   566.4 2747.33   575.52748.508   583.3 2749.79   587.8 2752.61   596.3 2760.92
   623.3 2783.82   641.6 2801.12     650 2806.43   689.2 2835.77   707.7  2846.4
   731.1 2861.49   740.1 2868.29   743.3 2870.09   752.2 2872.12   757.9 2876.38
#Mann= 5 ,-1,0
       0      .1       0     190     .08       0     290      .1       0
   494.4    .045       0   575.5      .1       0
Bank Sta=494.4,575.5
XS Rating Curve= 0 ,0
Exp/Cntr(USF)=0,0
Exp/Cntr=0.3,0.1

Type RM Length L Ch R = 1 ,65783   ,209.9,209.9,209.9
XS GIS Cut Line= 3
2370034.37852604692202.2343686342370275.37338664692133.365124656
2370823.01334288692126.463157986
#Sta/Elev= 30
       0 2792.41    47.6 2788.81    80.9 2784.05   105.9 2776.48   139.2 2758.72
   147.5 2753.04   155.8 2751.13   343.5 2750.48   367.5 2751.96   379.5 2750.48
   419.5 2752.73   451.5 2753.07   467.5 2751.94   487.5 2752.42   520.3 2747.26
     544 2746.07   595.5 2746.24   601.12747.314   607.2 2750.83   611.5 2754.88
   619.5 2763.42   636.1 2783.46   675.5 2815.09     702 2833.02   715.5 2847.14
   719.5 2850.25   739.5 2863.75   747.5 2867.39   771.5 2881.11   798.3 2897.74
#Mann= 5 ,-1,0
       0      .1       0     200     .08       0  400.64      .1       0
   520.3    .045       0   601.1      .1       0
Bank Sta=520.3,601.1
XS Rating Curve= 0 ,0
Exp/Cntr=0.3,0.1

Type RM Length L Ch R = 1 ,65573   ,277.9,277.9,277.9
XS GIS Cut Line= 2
2370143.56901036692286.0161488192370820.90602077692371.627518165
#Sta/Elev= 30
       0 2773.91      32  2765.2    57.1 2763.56    65.1 2762.09    69.2 2760.74
    85.3 2751.88    93.3 2749.92   165.9 2749.61   198.2 2751.11   250.6 2750.65
   258.6 2751.68   282.8  2750.8   331.2 2752.48   343.3  2751.7   379.2 2746.55
   389.9 2745.69   456.2 2745.59   466.72746.445   472.3 2749.26   475.9 2752.89
   508.6 2787.95   516.7 2799.41   529.5 2810.58   544.9 2821.61   585.2 2844.59
   597.6 2854.27   609.4 2865.25   633.3 2883.76   658.4 2899.88   682.7 2913.86
#Mann= 4 ,-1,0
       0     .08       0     190      .1       0   379.2    .045       0
   466.7      .1       0
Bank Sta=379.2,466.7
XS Rating Curve= 0 ,0
Exp/Cntr(USF)=0,0
Exp/Cntr=0.3,0.1

Type RM Length L Ch R = 1 ,65295   ,242.7,242.7,242.7
XS GIS Cut Line= 2
     2370084.683      692341.8182370705.91921123692748.574921585
#Sta/Elev= 30
       0 2787.05    16.5 2782.76    65.6 2765.52    80.7 2763.05    90.2 2759.54
   100.3    2753   115.7 2749.34   353.2 2748.98   386.7 2750.89     401 2748.56
   415.4 2748.61   424.9 2745.34   438.3 2744.44     510 2745.29   515.8 2748.36
     525 2760.02   545.3 2779.27   558.8 2796.06   573.1 2809.71   582.8 2823.21
   588.6 2828.58     603  2838.7   630.5 2851.27   641.4 2854.67   649.3  2854.7
     664 2851.52   692.5 2842.06   707.1 2840.17   726.1 2834.93   742.6 2833.46
#Mann= 5 ,-1,0
       0      .1       0      60     .08       0     170      .1       0
   424.9    .045       0     510      .1       0
Bank Sta=424.9,510
XS Rating Curve= 0 ,0
Exp/Cntr=0.3,0.1

Type RM Length L Ch R = 1 ,65053   ,218.5,218.5,218.5
XS GIS Cut Line= 2
2370071.01587779692450.8586652742370455.32245797692972.041561684
#Sta/Elev= 30
       0 2777.82    36.8  2767.8    62.5  2763.2    82.8 2760.63    96.3 2760.21
   109.8 2758.01   122.2 2751.84   132.1  2748.3   136.9 2747.66   271.4 2748.38
   278.3 2749.49   291.8 2747.88     320 2748.99   331.5 2747.56     339 2747.78
   355.7 2744.74   370.7 2743.58   434.4  2743.7   446.8 2744.74   453.5 2746.92
     494 2765.64   509.8  2768.1   534.6 2775.67   551.7 2785.35   574.6 2794.51
   588.3 2801.87   599.3 2805.38     629 2819.96   640.4 2827.09   647.6 2828.94
#Mann= 5 ,-1,0
       0      .1       0     100     .08       0     260      .1       0
   355.7    .045       0   446.8      .1       0
Bank Sta=355.7,446.8
XS Rating Curve= 0 ,0
Exp/Cntr(USF)=0,0
Exp/Cntr=0.3,0.1

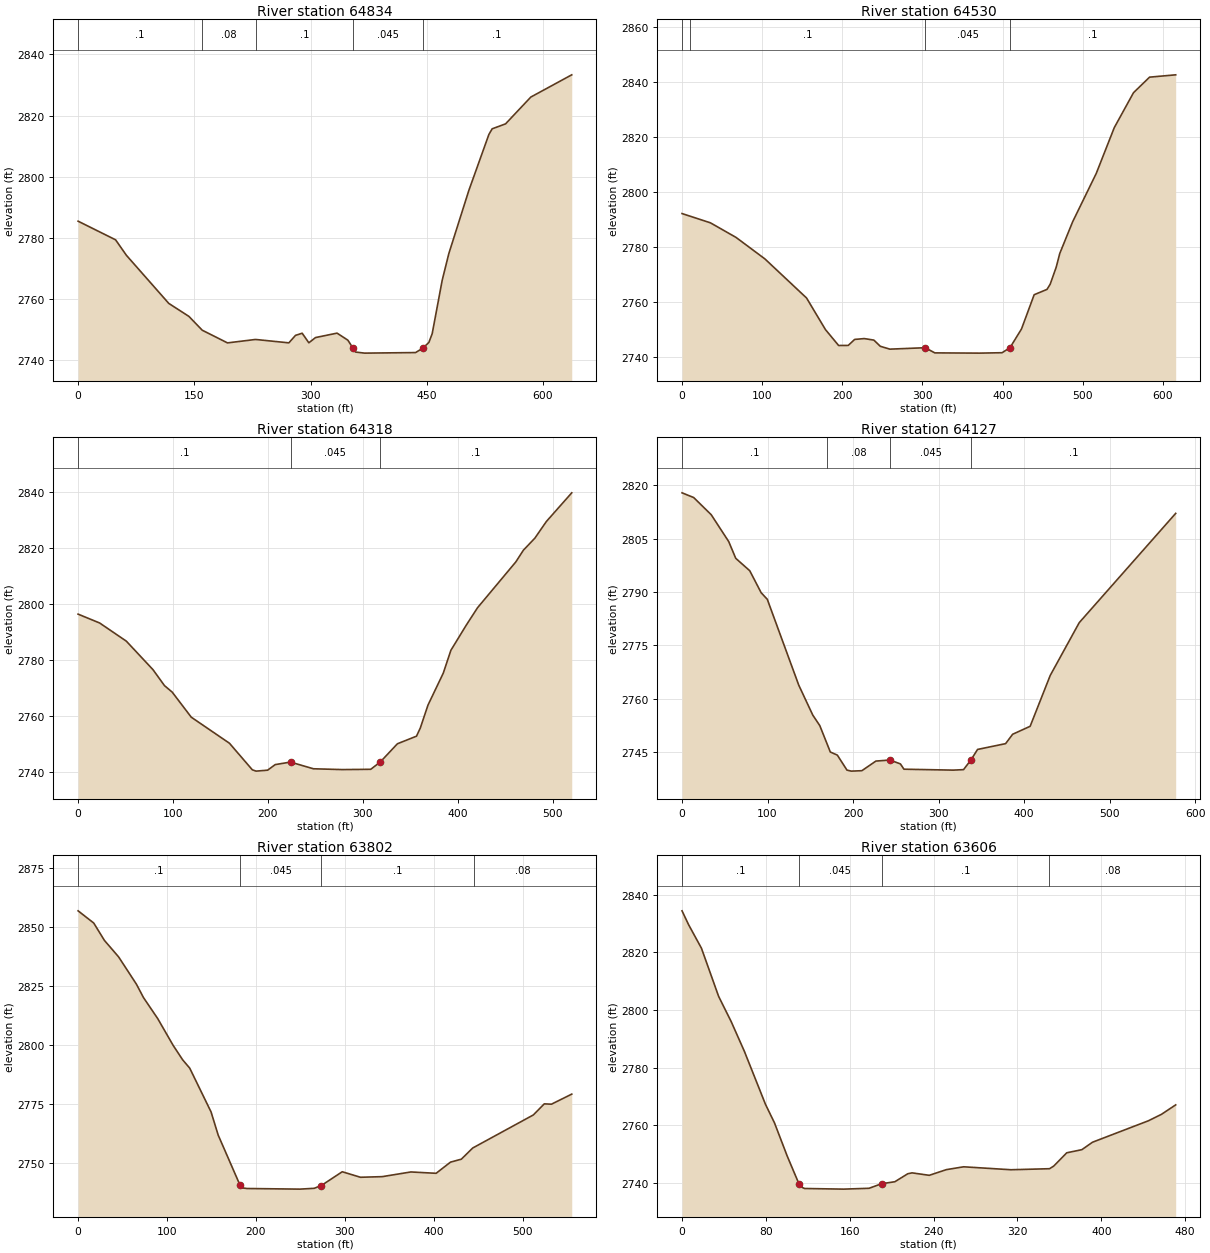
Type RM Length L Ch R = 1 ,64834   ,304,304,304
XS GIS Cut Line= 2
2369973.26405266692516.2154476272370207.57060561693108.614237557
#Sta/Elev= 30
       0 2785.47    48.4 2779.37    62.3 2774.32     117 2758.58     143 2754.33
   160.2 2749.81   192.8 2745.66     229 2746.78     272 2745.67   280.6 2748.12
   289.2 2748.82   297.8 2745.69   306.4  2747.4   334.2 2748.85   348.2 2746.54
   354.4 2744.08   358.1 2742.66   369.8 2742.31   435.5 2742.49   444.8 2743.91
   452.7  2745.8     457 2748.67   469.9 2766.13   478.5  2774.9   504.3 2795.53
   530.2 2813.85   534.4 2815.68   551.7  2817.3   584.3 2826.07   637.1 2833.34
#Mann= 5 ,-1,0
       0      .1       0     160     .08       0     230      .1       0
   354.4    .045       0   444.8      .1       0
Bank Sta=354.4,444.8
XS Rating Curve= 0 ,0
Exp/Cntr=0.3,0.1

Type RM Length L Ch R = 1 ,64530   ,212.5,212.5,212.5
XS GIS Cut Line= 2
2369823.58561384692529.8257707912369813.05666644693145.769193821
#Sta/Elev= 30
       0  2792.1    35.4 2788.73    67.4 2783.41   103.4 2775.58   155.4 2761.33
     179 2749.81   195.4 2744.03   207.4 2744.06   215.4 2746.24   227.4 2746.55
   239.4 2745.99   247.4 2743.74   259.4  2742.7   303.4 2743.22   315.4 2741.34
   371.4 2741.25   399.4  2741.4   409.32743.262   423.6 2750.05   439.4 2762.53
   455.4 2764.47   459.4 2766.36   466.9 2772.56   471.4  2777.6   487.4 2789.09
   516.9 2806.74   539.4 2823.43   563.4 2836.15   583.4  2841.8     616 2842.65
#Mann= 4 ,-1,0
       0     .08       0      10      .1       0   303.4    .045       0
   409.3      .1       0
Bank Sta=303.4,409.3
XS Rating Curve= 0 ,0
Exp/Cntr(USF)=0,0
Exp/Cntr=0.3,0.1

Type RM Length L Ch R = 1 ,64318   ,190.8,190.8,190.8
XS GIS Cut Line= 2
2369634.84021416692590.6452159322369581.56294265693107.774630801
#Sta/Elev= 30
       0 2796.38    22.7 2793.22    50.8 2786.74    78.9 2776.56      91 2770.87
    99.1 2768.56   119.2 2759.61   159.4 2750.32   183.5 2740.84   187.5 2740.37
   199.6 2740.71   207.6  2742.7   223.7  2743.6   247.8 2741.21   278.2 2740.92
   308.2 2741.02   318.3 2743.64   336.3 2750.13   356.4 2752.84   360.4 2755.75
   368.5 2763.93   384.6 2775.33   392.6 2783.47   408.7 2792.39   420.7 2798.67
     461 2815.01     469  2819.2   481.1  2823.5   493.1  2829.4   519.9 2839.66
#Mann= 3 ,-1,0
       0      .1       0   223.7    .045       0   318.3      .1       0
Bank Sta=223.7,318.3
XS Rating Curve= 0 ,0
Exp/Cntr=0.3,0.1

Type RM Length L Ch R = 1 ,64127   ,325.3,325.3,325.3
XS GIS Cut Line= 2
2369481.39482327  692571.94156042369355.04745444693135.240246418
#Sta/Elev= 30
       0 2817.87    13.6 2816.55    34.1 2811.73    54.6 2804.18    62.8 2799.48
    79.2 2795.99    92.5 2789.83    99.7 2787.97   136.5 2763.86   152.9 2755.46
   161.1 2752.51   173.4 2745.09   181.6 2744.22   192.9    2740     198 2739.72
   210.3 2739.84   226.7 2742.54   243.1 2742.84   255.4 2741.74   259.5 2740.26
   317.1    2740   329.2 2740.14   338.2 2742.98   345.6 2745.81   378.4 2747.44
   386.6 2750.07   407.1 2752.31   430.6  2766.6   464.5 2781.41   577.3  2812.1
#Mann= 4 ,-1,0
       0      .1       0     170     .08       0   243.1    .045       0
   338.2      .1       0
Bank Sta=243.1,338.2
XS Rating Curve= 0 ,0
Exp/Cntr(USF)=0,0
Exp/Cntr=0.3,0.1

Type RM Length L Ch R = 1 ,63802   ,195.3,195.3,195.3
XS GIS Cut Line= 3
2369098.47393911692587.5665447832369095.61321416692902.826743718
2369135.15038795693139.723291387
#Sta/Elev= 30
       0 2856.83    17.6 2851.65    29.6 2844.29    45.6 2837.29    65.6 2825.73
    73.6 2820.02    89.6 2811.12   106.9  2799.8   117.6 2793.67   125.6 2790.11
   149.6 2771.55   157.6 2761.74   182.3 2740.39   185.6 2739.28   190.2 2739.07
   249.6 2738.81   265.6 2739.15   273.6 2740.32   297.2 2746.18   317.7 2743.84
   342.1  2744.1   374.4 2746.09   402.8 2745.52     419 2750.26   431.2 2751.51
     444 2756.25   512.2 2770.27   524.5 2774.97   532.6 2774.83   555.4  2779.1
#Mann= 4 ,-1,0
       0      .1       0   182.3    .045       0   273.6      .1       0
  445.27     .08       0
Bank Sta=182.3,273.6
XS Rating Curve= 0 ,0
Exp/Cntr=0.3,0.1

Type RM Length L Ch R = 1 ,63606   ,304.9,304.9,304.9
XS GIS Cut Line= 2
2368870.29103091692687.1277185332368973.91166677693146.512537507
#Sta/Elev= 30
       0 2834.37     6.2  2829.6    18.5 2821.42    34.9 2804.71    46.8 2796.03
    59.5 2785.63    79.6 2767.28    88.2 2760.84   100.3 2749.37   111.4 2739.82
   112.8 2738.77   116.9  2738.1   153.9 2737.88   178.4 2738.17   190.4 2739.76
     203 2740.44   215.3  2743.2   219.4 2743.52   235.8 2742.67   252.2 2744.64
   268.6 2745.62   313.7  2744.6   350.6 2744.96   354.6 2745.88     367 2750.48
   381.4 2751.56   391.6 2754.15   444.9 2761.58   457.3 2763.81   470.9 2767.09
#Mann= 4 ,-1,0
       0      .1       0   111.4    .045       0   190.4      .1       0
     350     .08       0
Bank Sta=111.4,190.4
XS Rating Curve= 0 ,0
Exp/Cntr(USF)=0,0
Exp/Cntr=0.3,0.1