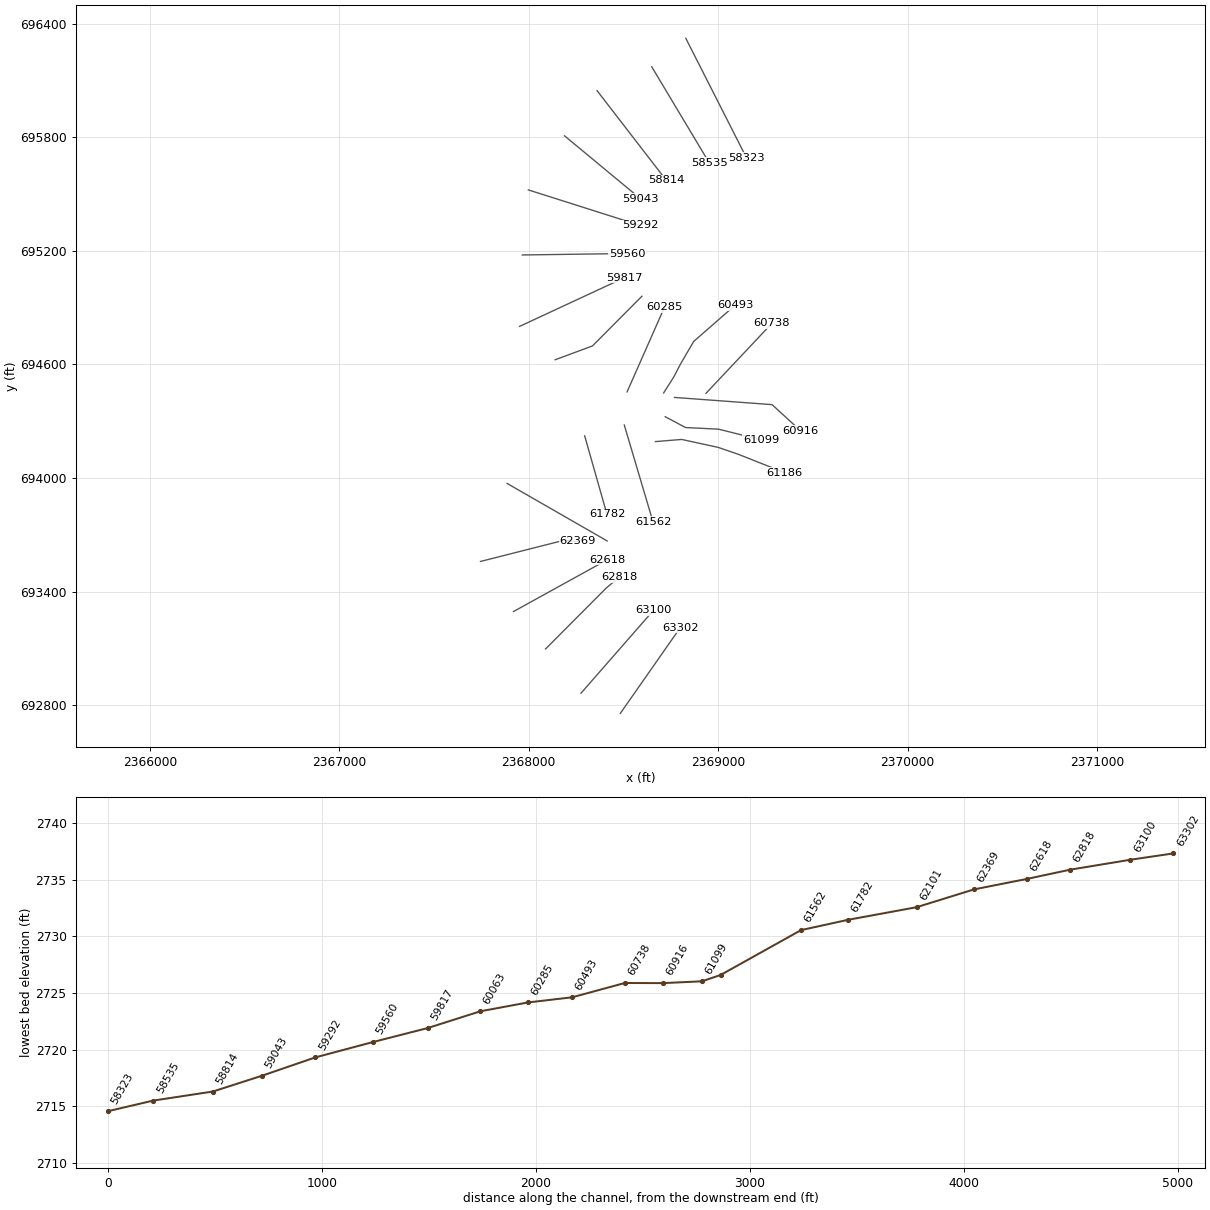
HEC-RAS study LAURELFK.prj: LAURELFK

--- LAURELFK.g01 (geometry) --- (continued)

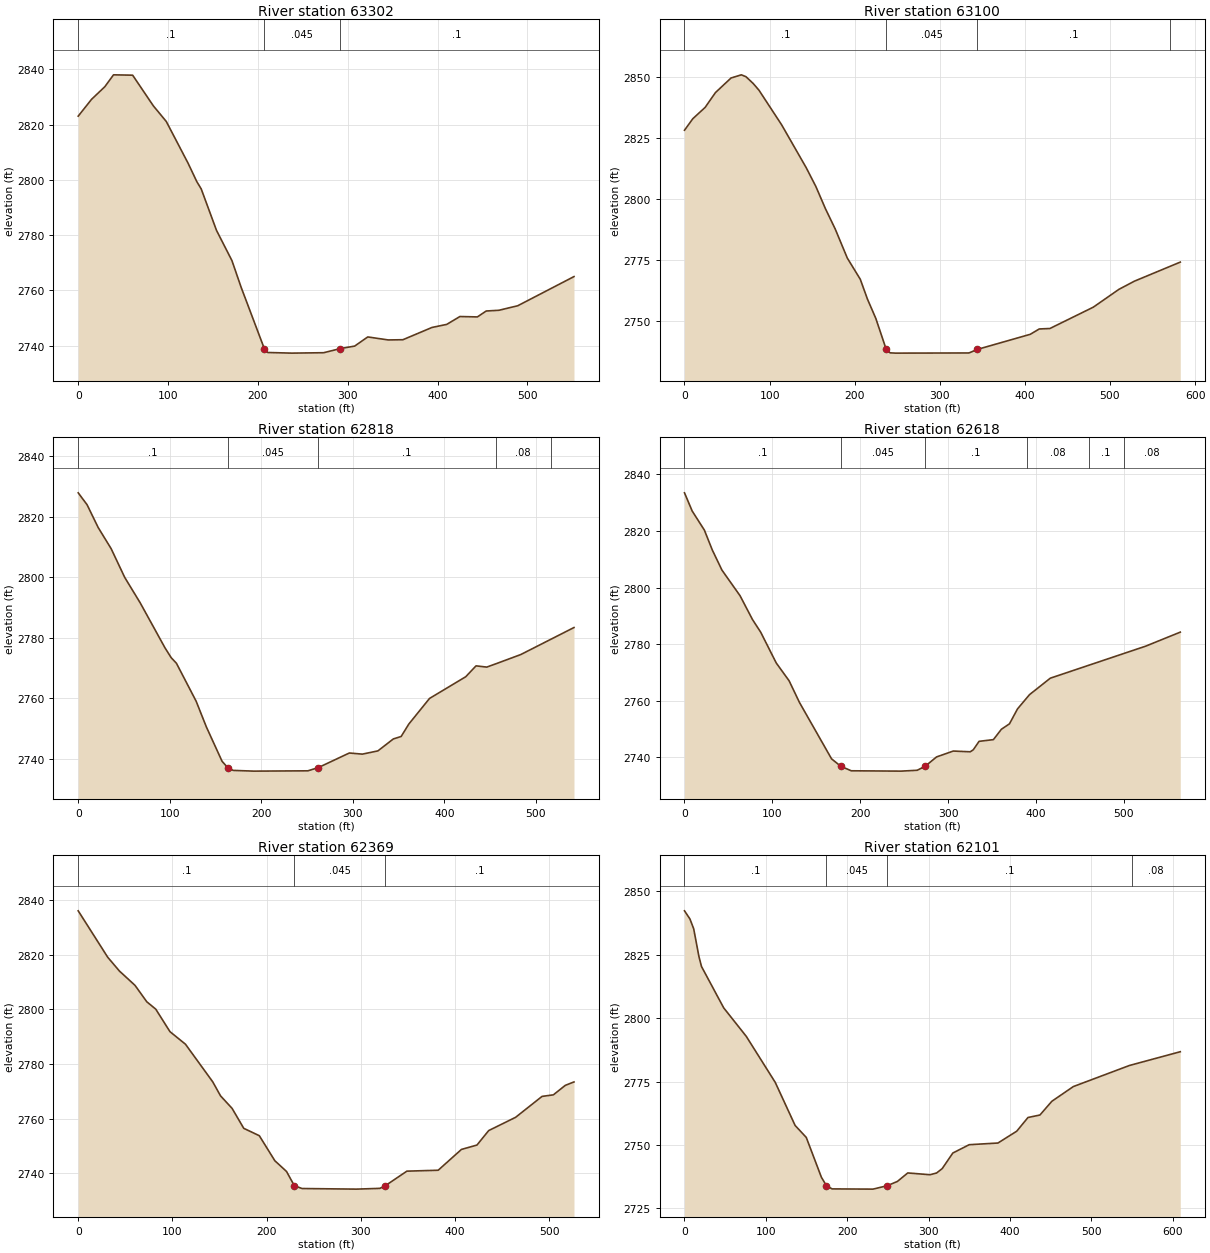
Type RM Length L Ch R = 1 ,63302   ,201.5,201.5,201.5
XS GIS Cut Line= 2
2368484.01712335692756.9358054212368800.01999618693209.248568452
#Sta/Elev= 30
       0 2823.06    14.9 2829.16    29.6  2833.7    39.3 2838.01    60.6 2837.88
    83.6  2826.8      98 2821.14   122.3 2806.03     132 2799.37   136.9 2796.74
   153.9 2781.75   171.1  2770.8   181.3 2761.18   207.1 2738.98   210.8 2737.55
   237.7 2737.32   273.2 2737.47   291.8 2738.97   307.7 2739.87   322.3 2743.18
     345 2742.09   361.4 2742.17   393.8 2746.61   410.2 2747.72   424.8 2750.56
   444.3 2750.42   454.1 2752.56   468.2 2752.82   489.2 2754.46   551.8 2765.01
#Mann= 3 ,-1,0
       0      .1       0   207.1    .045       0   291.8      .1       0
Bank Sta=207.1,291.8
XS Rating Curve= 0 ,0
Exp/Cntr=0.3,0.1

Type RM Length L Ch R = 1 ,63100   ,282.1,282.1,282.1
XS GIS Cut Line= 2
2368276.19938532692863.282799493  2368659.595738693301.943491295
#Sta/Elev= 30
       0 2828.01     9.8 2832.73    24.3 2837.38    36.4 2843.43    54.7 2849.39
    66.8 2850.69    72.2 2849.93    80.7 2847.16    87.5  2844.4   114.1 2830.26
   143.1 2812.63   154.4 2804.95   165.7 2795.83   177.1 2787.59   191.3 2775.69
   206.6 2766.98     215 2758.88   224.9 2750.91     237 2738.33   241.6 2736.88
     248 2736.76   334.3 2736.83   344.3  2738.3   406.3 2744.46   416.9 2746.65
   429.4 2746.84   480.4 2755.57   510.5 2762.87   528.6  2766.2   582.6 2774.02
#Mann= 4 ,-1,0
       0      .1       0     237    .045       0   344.3      .1       0
     570     .08       0
Bank Sta=237,344.3
XS Rating Curve= 0 ,0
Exp/Cntr(USF)=0,0
Exp/Cntr=0.3,0.1

Type RM Length L Ch R = 1 ,62818   ,200.3,200.3,200.3
XS GIS Cut Line= 3
 2368089.3189114693097.1450173742368410.98310216 693420.35708096
2368476.82390167693474.987339125
#Sta/Elev= 30
       0 2827.88     9.7 2823.94    21.8 2816.42      36 2809.41    50.8 2799.93
    67.8 2791.47    94.8 2776.64   101.6 2773.37   107.3 2771.54   128.8 2759.02
   140.1 2750.43   157.2 2739.11   163.3 2737.07   169.3 2736.12   191.9 2735.88
   250.9 2735.98   262.3 2737.05   296.2 2741.87   310.4  2741.5   327.4 2742.57
   344.3 2746.53   352.8 2747.33   361.2 2751.45   383.8 2759.91   423.3 2767.07
   434.6 2770.68   446.3 2770.27     456 2771.33   483.5 2774.42   541.6 2783.35
#Mann= 5 ,-1,0
       0      .1       0   163.3    .045       0   262.3      .1       0
     456     .08       0     516      .1       0
Bank Sta=163.3,262.3
XS Rating Curve= 0 ,0
Exp/Cntr=0.3,0.1

Type RM Length L Ch R = 1 ,62618   ,248.5,248.5,248.5
XS GIS Cut Line= 2
 2367920.4352022693295.0354489052368414.36023313693567.903123333
#Sta/Elev= 30
       0 2833.51     8.8 2827.05    22.6 2820.34    31.7 2813.26    42.6 2806.19
    63.2 2797.13    77.4 2788.69    86.8 2784.18   104.4 2773.34   119.1 2767.01
   130.9 2759.34   167.4 2739.41   177.9 2736.79   189.8 2735.19   246.5 2735.07
   264.8 2735.37   273.9 2736.78   286.9 2740.09   305.9 2742.17   325.2 2741.91
   328.7 2742.62   335.3 2745.61   351.6 2746.21   360.7 2749.88   369.9  2751.8
     379 2757.06   392.7 2762.12   416.4 2767.95   524.8 2779.26   564.3 2784.23
#Mann= 6 ,-1,0
       0      .1       0   177.9    .045       0   273.9      .1       0
     390     .08       0     460      .1       0     500     .08       0
Bank Sta=177.9,273.9
XS Rating Curve= 0 ,0
Exp/Cntr(USF)=0,0
Exp/Cntr=0.3,0.1

Type RM Length L Ch R = 1 ,62369   ,267.8,267.8,267.8
XS GIS Cut Line= 3
2367745.75772342693559.4178700492368185.44523766693671.036305073
2368257.95136624 693664.98028839
#Sta/Elev= 30
       0 2836.15    31.4 2819.11    43.8 2814.07    60.3 2808.84    72.8 2802.82
    82.4 2800.09    97.4 2791.87   113.9 2787.25   142.8 2773.49   151.1 2768.34
   163.4 2763.73   175.8 2756.42   192.3 2753.72   208.8 2744.54   221.2 2740.61
   229.5 2735.38   237.7 2734.36   295.5 2734.14   320.3 2734.42     326 2735.37
     349 2740.73   382.2 2741.06   406.9 2748.69   423.4  2750.3   435.8 2755.59
   464.4 2760.46   492.5 2768.13   504.5  2768.7   517.2 2772.18   526.4 2773.43
#Mann= 3 ,-1,0
       0      .1       0   229.5    .045       0     326      .1       0
Bank Sta=229.5,326
XS Rating Curve= 0 ,0
Exp/Cntr=0.3,0.1

Type RM Length L Ch R = 1 ,62101   ,319.5,319.5,319.5
XS GIS Cut Line= 2
2367886.35610208693971.5921959362368414.37681243  693667.9236329
#Sta/Elev= 30
       0 2842.31     6.7 2839.09    11.3 2835.24    17.7 2824.34    20.9 2820.35
    48.2 2804.03    75.9 2792.81   111.5 2774.66   135.9 2757.68   149.6 2752.96
   168.2 2737.25   174.4  2733.9   181.4 2732.66   231.6 2732.57   249.2 2733.93
   261.6 2735.61   274.3 2738.95   301.7 2738.25   309.7 2738.93   316.6 2740.66
   329.7 2746.81   349.8 2750.09   385.1 2750.75   408.2 2755.42     422 2760.81
   436.7  2761.8   451.3  2767.2   477.7 2773.01   546.6 2781.32   609.1 2786.75
#Mann= 4 ,-1,0
       0      .1       0   174.4    .045       0   249.2      .1       0
     550     .08       0
Bank Sta=174.4,249.2
XS Rating Curve= 0 ,0
Exp/Cntr(USF)=0,0
Exp/Cntr=0.3,0.1

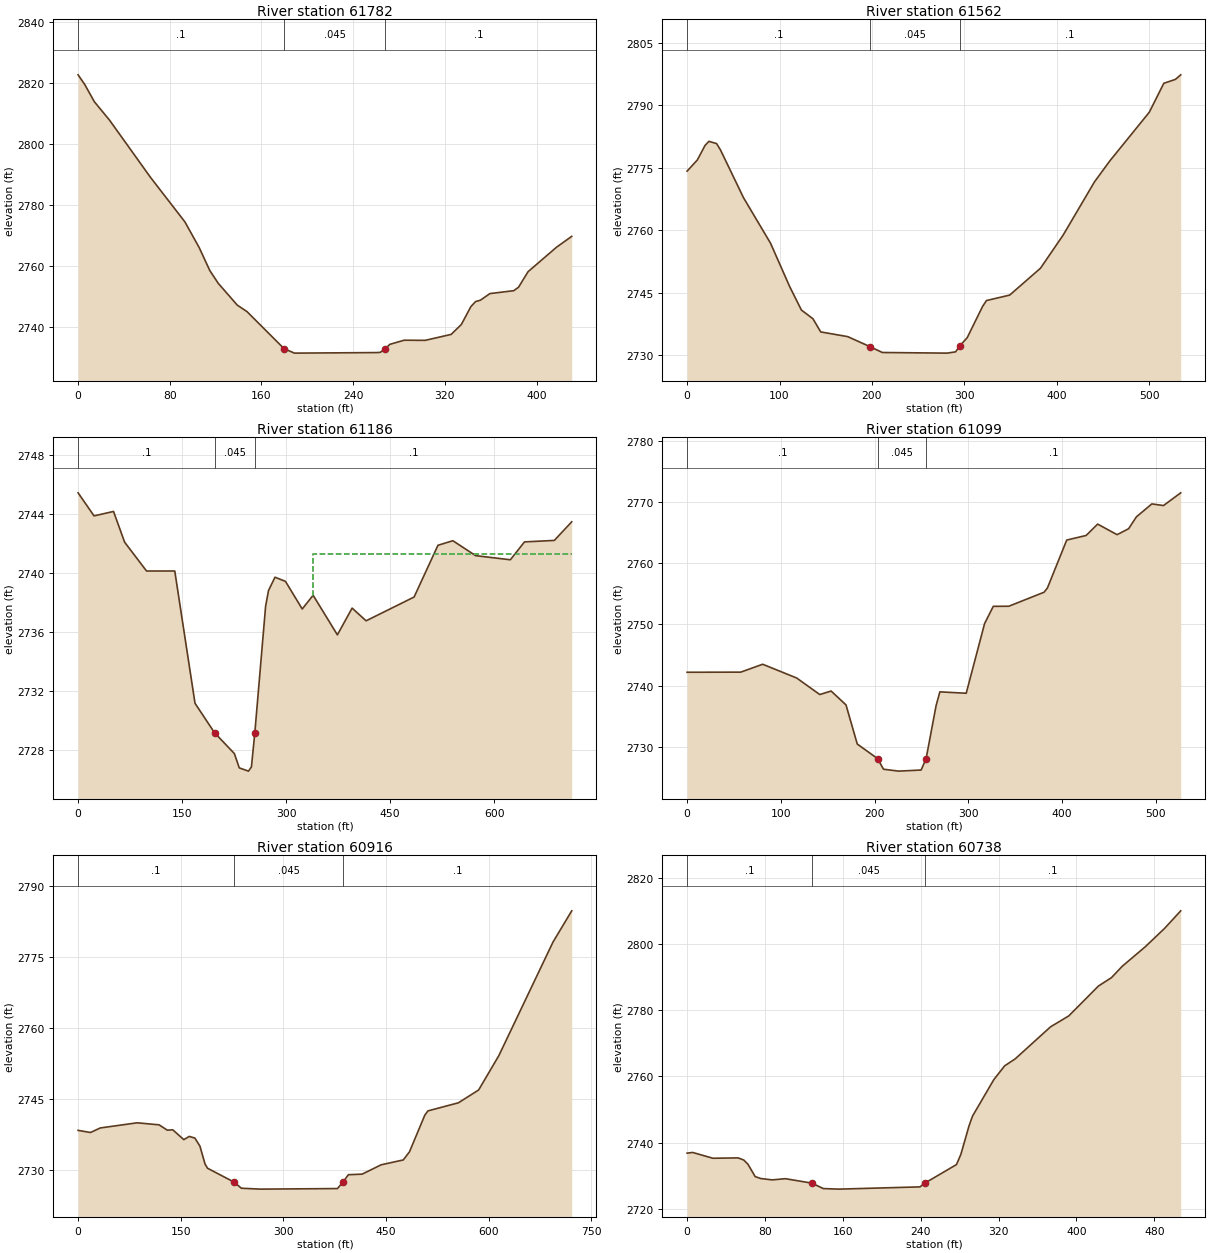
Type RM Length L Ch R = 1 ,61782   ,220,220,220
XS GIS Cut Line= 2
2368295.83052537694222.814277268 2368413.4969201693808.474412781
#Sta/Elev= 30
       0 2822.56     5.9 2819.33    14.2 2813.75    27.5 2807.69    63.1 2789.03
    93.2 2774.42   105.7 2765.98   114.9 2758.51   122.3  2754.3   138.9 2747.17
   147.3 2745.07   179.7 2732.92   188.8 2731.46   260.7 2731.64   263.7 2731.72
   267.8 2732.85     272 2734.33   284.5 2735.69   302.8 2735.64   325.5 2737.59
   334.4 2740.84   342.7 2746.68   346.8 2748.34     351 2748.78   359.3 2750.95
   380.1  2751.9   384.3 2753.04   392.6 2758.12   417.5 2766.15   430.7 2769.69
#Mann= 3 ,-1,0
       0      .1       0   179.7    .045       0   267.8      .1       0
Bank Sta=179.7,267.8
XS Rating Curve= 0 ,0
Exp/Cntr=0.3,0.1

Type RM Length L Ch R = 1 ,61562   ,375.9,375.9,375.9
XS GIS Cut Line= 2
2368505.02414468694279.793125584 2368656.8584262693767.635698374
#Sta/Elev= 30
       0 2774.23    11.1 2776.91    19.4 2780.39    23.6 2781.38    31.9 2780.84
    36.1 2779.33    61.1 2767.83    90.3 2756.93   110.8 2746.62   123.7 2740.89
   136.2  2738.8   144.6 2735.64   173.8 2734.51   197.7 2732.13   211.3  2730.7
   281.4 2730.55   290.6 2730.86   294.8 2732.21   303.1 2734.25   319.8 2741.77
     324 2743.17   349.1 2744.48   382.4 2750.92   406.9 2758.86   440.8 2771.63
   457.5 2776.69   500.2 2788.37   515.9 2795.31   528.4 2796.24   534.2 2797.34
#Mann= 3 ,-1,0
       0      .1       0   197.7    .045       0   294.8      .1       0
Bank Sta=197.7,294.8
XS Rating Curve= 0 ,0
Exp/Cntr(USF)=0,0
Exp/Cntr=0.3,0.1

Type RM Length L Ch R = 1 ,61186   ,86.9,86.9,86.9
XS GIS Cut Line= 5
2368669.28549757694192.607804317 2368807.8423957 694203.99564927
2369000.45478312694162.0544224412369106.85089815694125.597078506
2369351.45164528694028.525590733
#Sta/Elev= 30
       0 2745.42      23 2743.86    51.1 2744.16    67.1 2742.08    98.7 2740.13
   139.4 2740.13   168.6 2731.18   196.7 2729.19   225.3 2727.78   232.4 2726.81
   245.7 2726.59   249.9 2726.87  254.81 2729.17   270.4 2737.75   274.5  2738.8
   283.9 2739.71     299 2739.43   323.2 2737.56   338.9 2738.49   373.9 2735.81
   395.1 2737.62   415.3 2736.76   484.5 2738.37   518.9 2741.87   540.4 2742.18
   573.2 2741.17   623.3 2740.89   643.7  2742.1   686.7  2742.2   711.8 2743.46
#Mann= 3 ,-1,0
       0      .1       0   196.7    .045       0  254.81      .1       0
#XS Ineff= 2 , 0
                          338.27         2741.27
Permanent Ineff=
       F       F
Bank Sta=196.7,254.81
XS Rating Curve= 0 ,0
Exp/Cntr=0.3,0.1

Type RM Length L Ch R = 1 ,61099   ,182.8,182.8,182.8
XS GIS Cut Line= 4
2368720.98372622694324.0190404092368828.67005613694266.840458156
2369003.06473201694258.263670818 2369226.0612028694202.038064935
#Sta/Elev= 30
       0 2742.19    57.2 2742.21    80.6  2743.5   116.9 2741.25   141.5 2738.55
   153.6 2739.12   169.5 2736.85   181.5 2730.46   203.2 2728.07   209.5 2726.34
   225.6 2726.03   249.6 2726.21  254.91 2728.06   265.6 2736.75   269.6 2738.99
   297.7 2738.76   317.3 2750.15   326.6 2752.97   343.1 2752.98   380.7 2755.27
   384.3 2755.96   404.9  2763.8   425.6 2764.55   437.9 2766.41   458.6 2764.68
   470.9 2765.65   479.2 2767.59   495.7 2769.71   508.1 2769.44   526.5 2771.52
#Mann= 3 ,-1,0
       0      .1       0   203.2    .045       0  254.91      .1       0
Bank Sta=203.2,254.91
XS Rating Curve= 0 ,0
Exp/Cntr(USF)=0,0
Exp/Cntr=0.3,0.1

Type RM Length L Ch R = 1 ,60916   ,177.9,177.9,177.9
XS GIS Cut Line= 3
2368770.14467611694425.9226871842369285.14573779694387.868457259
2369436.40256814694249.160389297
#Sta/Elev= 30
       0  2738.3    18.1 2737.85    32.5 2738.81    86.3  2739.9   118.4 2739.47
   130.4 2738.34   138.4 2738.42   154.5 2736.34   162.5 2737.02   170.7 2736.67
   178.1 2734.97   185.6 2731.16   189.3 2730.28   228.12727.348   238.7 2726.06
   266.8 2725.87   379.1 2725.99   387.3 2727.37   395.1 2728.92   415.2 2729.04
   443.1 2731.02   475.3 2732.04   484.4 2733.76   506.8 2741.51   511.4 2742.42
   555.9 2744.13   585.5 2746.84   615.1 2754.12   694.2 2778.13   721.6 2784.74
#Mann= 3 ,-1,0
       0      .1       0   228.1    .045       0   387.3      .1       0
Bank Sta=228.1,387.3
XS Rating Curve= 0 ,0
Exp/Cntr(USF)=0,0
Exp/Cntr=0.3,0.1

Type RM Length L Ch R = 1 ,60738   ,245.6,245.6,245.6
XS GIS Cut Line= 2
2368936.28589361 694447.632709992369283.78585095694816.970497879
#Sta/Elev= 30
       0 2736.78     5.7 2736.99    26.5 2735.23    52.4 2735.34    58.2  2734.7
    62.5 2733.43    69.9 2729.68    75.7 2729.09    87.4 2728.68     101 2729.04
   128.3 2727.69   139.9 2726.05   155.9 2725.88   239.2 2726.56   244.4 2727.73
   276.7 2733.31   281.2 2736.38   289.6 2745.02   293.2    2748   315.1 2759.05
   326.2 2763.22   337.1 2765.35   373.4 2775.05   392.1 2778.35   422.6 2787.41
     436 2789.95     447 2793.38   470.8 2799.33   490.6 2804.89   507.1 2810.18
#Mann= 3 ,-1,0
       0      .1       0   128.3    .045       0   244.4      .1       0
#XS Ineff= 2 , 0
                          616.11         2739.72
Permanent Ineff=
       F       F
Bank Sta=128.3,244.4
XS Rating Curve= 0 ,0
Exp/Cntr=0.3,0.1

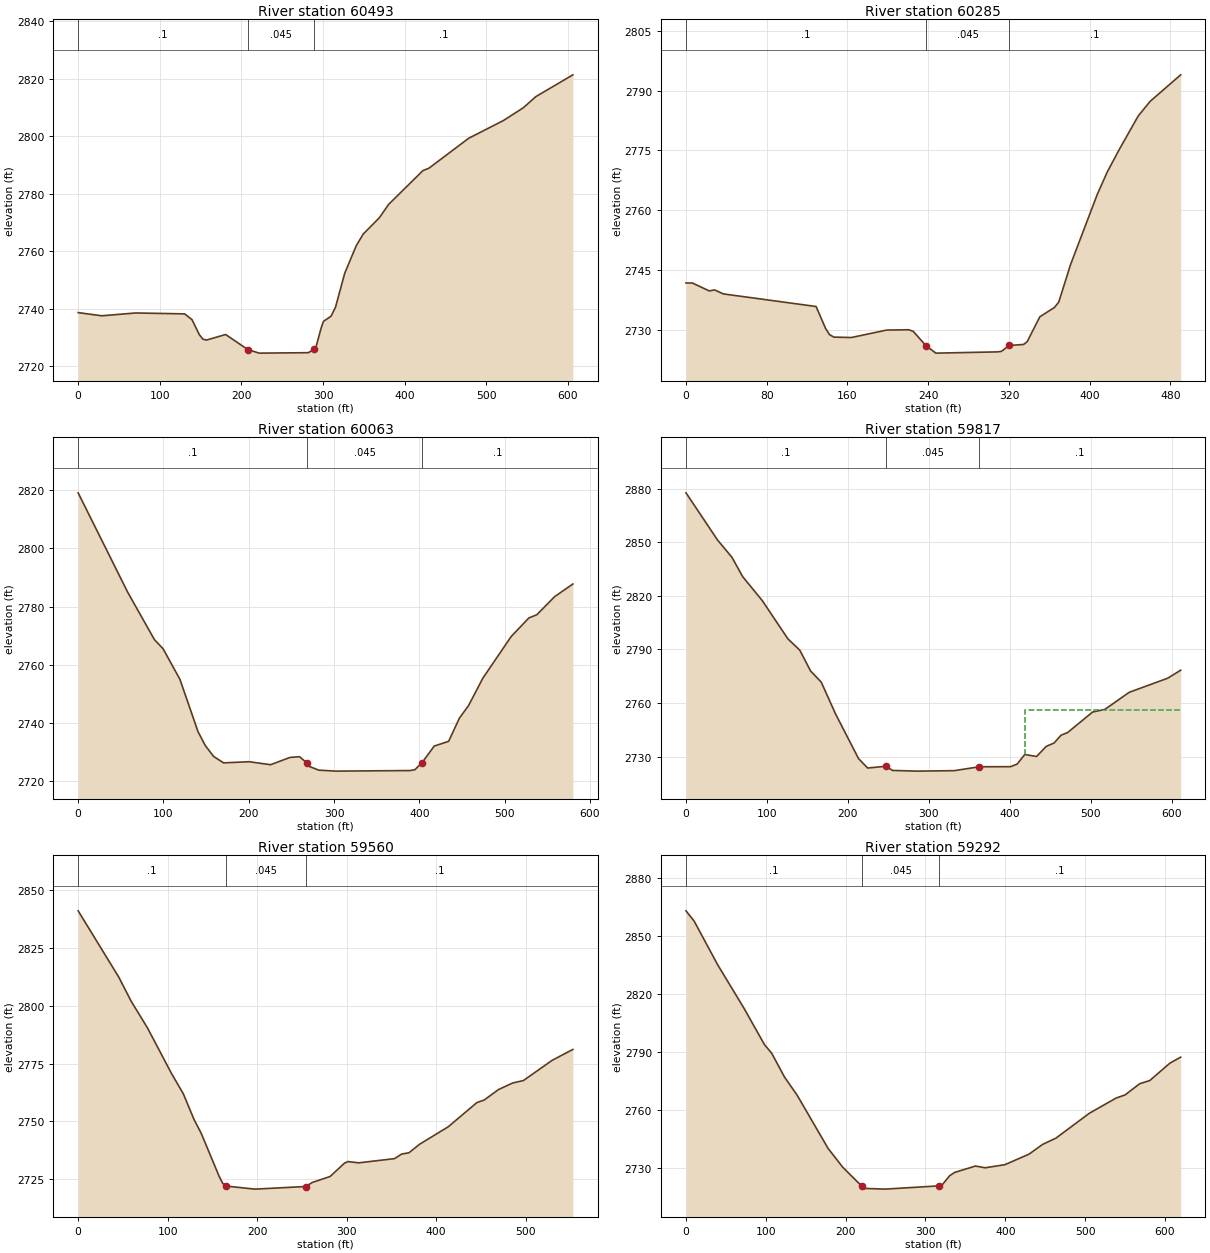
Type RM Length L Ch R = 1 ,60493   ,207.9,207.9,207.9
XS GIS Cut Line= 5
2368712.72104017694449.7983601832368765.59865065694532.891748079
2368800.85039097694600.8772472662368871.35387161694721.740356932
2369090.41825788694913.106947236
#Sta/Elev= 30
       0  2738.7    28.8 2737.59    70.4 2738.57   130.4 2738.25   139.4 2736.27
   148.4 2731.04   152.9 2729.45   157.4 2729.17   180.6 2731.09   207.8 2725.86
   221.7 2724.62   281.9 2724.77   288.9 2725.89   291.2 2726.64   297.6 2733.33
   300.5 2735.67   309.7 2737.43   315.2 2740.56   326.5 2752.36   340.7 2761.99
   349.2 2765.99   368.9 2771.65   380.4 2776.32   422.3 2788.03   429.7 2788.87
   478.3 2799.25   520.9 2805.42   545.2 2809.84   560.4 2813.68   605.9 2821.29
#Mann= 3 ,-1,0
       0      .1       0   207.8    .045       0   288.9      .1       0
Bank Sta=207.8,288.9
XS Rating Curve= 0 ,0
Exp/Cntr(USF)=0,0
Exp/Cntr=0.3,0.1

Type RM Length L Ch R = 1 ,60285   ,222,222,222
XS GIS Cut Line= 2
2368519.69171775694455.2881900512368717.58866706 694903.61990615
#Sta/Elev= 30
       0 2741.75     6.4 2741.74      23 2739.76    28.3 2740.01      37 2739.01
   128.9 2735.85   138.3 2730.36     142 2728.85   146.4 2728.18   163.8 2728.07
   198.8 2729.94   220.7 2730.02   225.1 2729.63   237.6 2726.07   247.5 2724.16
   308.3 2724.47   312.5  2724.6   320.3 2726.08   334.4 2726.33     338 2727.02
   350.6 2733.28     365  2735.6   369.3 2736.95     381 2746.36   407.3 2763.85
   417.4  2769.6   429.5 2775.33     448 2783.61   459.8 2787.28   490.1 2793.94
#Mann= 3 ,-1,0
       0      .1       0   237.6    .045       0   320.3      .1       0
Bank Sta=237.6,320.3
XS Rating Curve= 0 ,0
Exp/Cntr=0.3,0.1

Type RM Length L Ch R = 1 ,60063   ,246,246,246
XS GIS Cut Line= 3
2368140.28792118694625.0992216352368336.88158918694697.789317366
2368597.90511476694960.464890575
#Sta/Elev= 30
       0 2819.16    57.9 2785.05    89.4 2768.65    99.6 2765.47   119.3 2754.97
   140.6  2736.9   149.1 2732.16   158.8 2728.44   170.5 2726.22   200.3 2726.62
   225.6 2725.59   248.3 2728.09   259.6 2728.34   268.1 2726.19     271    2725
     282 2723.72     302 2723.38   389.2 2723.58   394.8 2723.88   403.32726.347
   417.4    2732   434.3 2733.64   446.9  2741.6   457.6 2745.92   474.5 2755.42
   507.6  2769.7   528.3 2776.09   537.7 2777.21   558.4 2783.39   579.9 2787.78
#Mann= 3 ,-1,0
       0      .1       0   268.1    .045       0   403.3      .1       0
Bank Sta=268.1,403.3
XS Rating Curve= 0 ,0
Exp/Cntr(USF)=0,0
Exp/Cntr=0.3,0.1

Type RM Length L Ch R = 1 ,59817   ,257,257,257
XS GIS Cut Line= 2
 2367952.6750588694801.3885674582368506.78810028695059.112719692
#Sta/Elev= 30
       0 2877.72    39.2 2851.17    56.7 2841.68      70 2830.82    94.4 2817.28
   125.9 2795.97   140.6 2789.61   153.9 2777.99   167.1 2771.72   184.7 2753.98
   213.2  2728.9   224.4 2723.64   246.8 2724.61   255.4 2722.28   285.5  2721.9
   331.5 2722.16   362.3 2724.34   400.9 2724.39     409 2725.82   418.5  2731.2
   433.1 2730.11     445 2735.74   454.8 2737.66   463.2 2741.97   471.5 2743.52
   502.3 2754.99   517.4 2756.43   547.5 2766.03     595 2773.91   611.1 2778.41
#Mann= 3 ,-1,0
       0      .1       0   246.8    .045       0   362.3      .1       0
#XS Ineff= 2 , 0
                           419.3         2756.29
Permanent Ineff=
       F       F
Bank Sta=246.8,362.3
XS Rating Curve= 0 ,0
Exp/Cntr=0.3,0.1

Type RM Length L Ch R = 1 ,59560   ,267.8,267.8,267.8
XS GIS Cut Line= 2
2367966.72937434695178.5015947442368519.37276559  695186.1771974
#Sta/Elev= 30
       0 2841.11    45.4 2812.41    59.3 2801.94    77.5 2790.41   104.2 2770.79
   117.5 2761.92   129.5 2750.78   137.5 2744.82   157.5 2726.24   161.5 2723.15
   165.5 2721.98   197.4 2720.66   254.3 2721.79   261.5 2723.53   281.5 2726.13
   297.5 2731.88   301.5 2732.59   313.5 2732.04   353.5 2733.86   361.5 2735.85
   369.5 2736.37   381.5 2740.09   413.5 2747.65   445.5 2758.12   453.5 2759.19
   469.6 2763.74   485.5  2766.6   497.5 2767.66   529.5 2776.39   552.7 2781.12
#Mann= 3 ,-1,0
       0      .1       0   165.5    .045       0   254.3      .1       0
Bank Sta=165.5,254.3
XS Rating Curve= 0 ,0
Exp/Cntr(USF)=0,0
Exp/Cntr=0.3,0.1

Type RM Length L Ch R = 1 ,59292   ,249.5,249.5,249.5
XS GIS Cut Line= 2
2367998.46670237       695522.182368589.05391341695334.517771648
#Sta/Elev= 30
       0 2863.11    10.2 2857.82    39.6 2835.31    73.1 2812.47    98.3 2793.99
   107.3 2789.57   123.5 2777.17   139.1 2767.95   178.1 2740.31   196.4 2730.62
     220 2720.93   224.2 2719.67   249.4 2719.31   317.5 2721.01   320.8 2721.43
   330.2  2726.2   336.6 2727.95   362.7 2731.24   374.8 2730.34   399.6 2731.95
   429.9 2737.42   446.7 2742.41   463.5 2745.67   505.4 2758.54     539  2766.4
     550 2767.97   568.4 2773.78     581 2775.42   606.2  2784.4   619.7 2787.51
#Mann= 3 ,-1,0
       0      .1       0     220    .045       0   317.5      .1       0
Bank Sta=220,317.5
XS Rating Curve= 0 ,0
Exp/Cntr=0.3,0.1

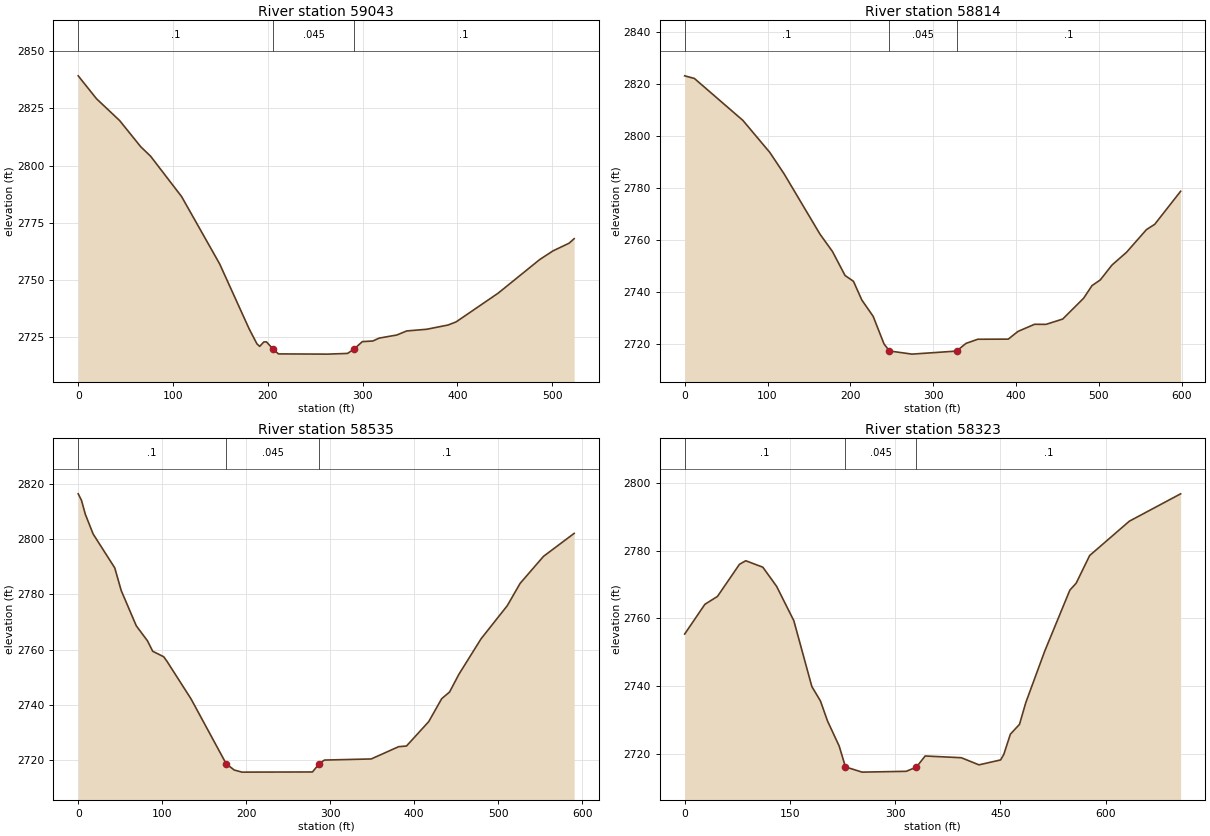
Type RM Length L Ch R = 1 ,59043   ,228.7,228.7,228.7
XS GIS Cut Line= 2
2368189.32185137695807.9010125542368592.29099082695474.012297008
#Sta/Elev= 30
       0 2839.23    19.3 2829.22    43.7  2819.7      66 2808.25    76.4 2804.12
   109.1 2786.49   149.2 2757.14   180.3 2728.79   188.6 2722.17   191.5 2721.08
   195.9 2723.02   198.6 2723.05   205.7 2719.86   211.3 2717.79   263.4 2717.69
   284.2    2718   290.9 2719.83   299.8 2723.15   310.8 2723.42   317.7  2724.7
   336.2 2726.04   346.6 2727.81   367.6 2728.54   390.3 2730.41   398.8 2731.78
   443.1 2744.31     487 2759.01   501.1 2762.81     518 2766.14   523.3 2768.11
#Mann= 3 ,-1,0
       0      .1       0   205.7    .045       0   290.9      .1       0
Bank Sta=205.7,290.9
XS Rating Curve= 0 ,0
Exp/Cntr(USF)=0,0
Exp/Cntr=0.3,0.1

Type RM Length L Ch R = 1 ,58814   ,278.7,278.7,278.7
XS GIS Cut Line= 2
2368361.21359347696046.4693005552368726.77610216695572.486579915
#Sta/Elev= 30
       0 2823.08    11.7 2822.08    70.3 2805.97   102.8 2793.67     120 2785.48
   163.3 2762.34   178.4 2755.67   193.6 2746.46   203.7 2744.26   213.8 2737.08
   227.5  2730.8   240.6 2720.22   247.2 2717.51   274.4  2716.3   328.1 2717.47
   339.6 2720.43   353.8 2722.01   390.6 2722.06   402.3 2725.01   422.3 2727.75
   436.1 2727.72   456.3 2729.76   481.5 2737.74   491.6 2742.57   501.7 2744.79
   515.7 2750.46   533.5 2755.44   557.3 2764.06   567.4 2766.13   598.6 2778.79
#Mann= 3 ,-1,0
       0      .1       0   247.2    .045       0   328.1      .1       0
Bank Sta=247.2,328.1
XS Rating Curve= 0 ,0
Exp/Cntr=0.3,0.1

Type RM Length L Ch R = 1 ,58535   ,212.5,212.5,212.5
XS GIS Cut Line= 2
2368649.85801074696172.4921387242368953.04431566695665.902363414
#Sta/Elev= 30
       0 2816.53     3.9 2814.17     8.5 2809.09    17.8 2801.93    43.5 2789.65
    51.2 2781.41    69.1 2768.64    82.4 2763.19    88.7 2759.38   101.8 2757.38
   105.8 2755.68   134.4 2742.04   176.2 2718.52   185.7 2716.27     195  2715.5
   278.9 2715.56     287  2718.6   293.1 2719.88   348.8 2720.28   381.5 2724.74
   390.8 2724.98   417.3 2733.84   432.7 2742.16   442.1 2744.59   453.2 2751.02
   479.6 2763.91   510.8 2775.93   526.1 2784.03   553.9 2793.83   590.4 2802.17
#Mann= 3 ,-1,0
       0      .1       0   176.2    .045       0     287      .1       0
Bank Sta=176.2,287
XS Rating Curve= 0 ,0
Exp/Cntr(USF)=0,0
Exp/Cntr=0.3,0.1

Type RM Length L Ch R = 1 ,58323   ,226.3,226.3,226.3
XS GIS Cut Line= 2
2368829.75058583696322.834233148     2369149.664      695692.401
#Sta/Elev= 30
       0 2755.37    28.8 2764.16    46.7 2766.48    78.1 2775.98    87.1 2777.03
   111.4 2775.13     131 2769.49   155.6 2759.32   181.3 2739.85   193.5 2735.61
   203.7 2729.65   220.3 2722.24   229.2 2716.11   252.9 2714.56   315.8  2714.8
   330.3 2716.03   342.8 2719.33   394.3 2718.82   419.6 2716.71   450.4 2718.17
   454.9 2719.79   464.3 2725.77   477.3 2728.68   486.3 2735.11   513.2 2750.28
   549.1 2768.35   558.1  2770.4   577.3 2778.57   633.9 2788.72     707 2796.81
#Mann= 3 ,-1,0
       0      .1       0   229.2    .045       0   330.3      .1       0
Bank Sta=229.2,330.3
XS Rating Curve= 0 ,0
Exp/Cntr=0.3,0.1