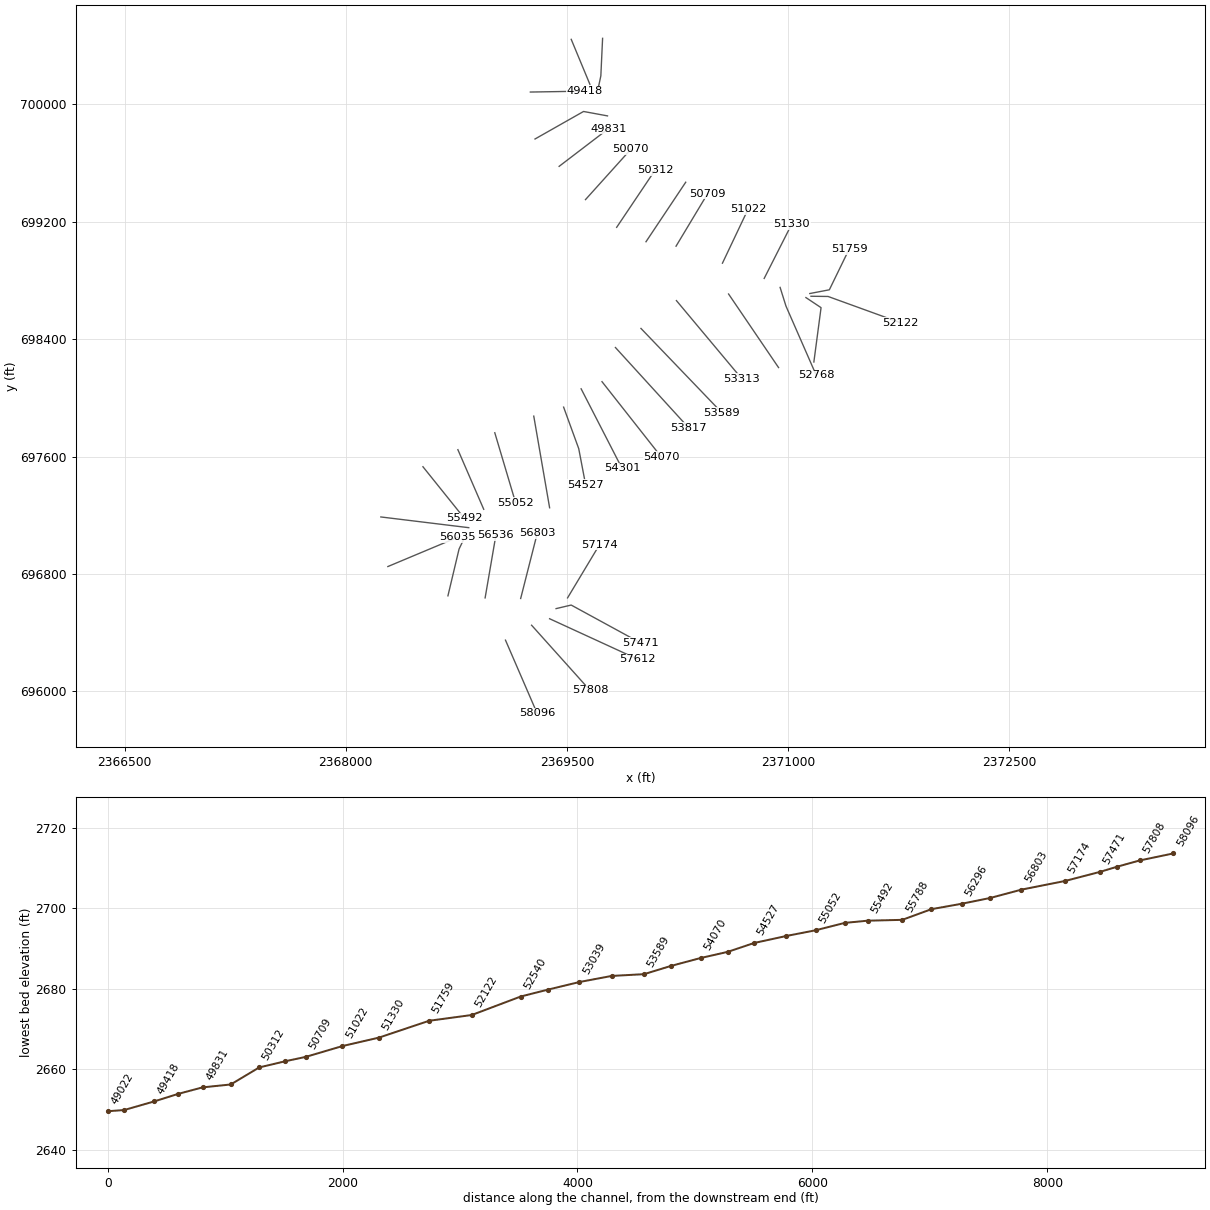
HEC-RAS study LAURELFK.prj: LAURELFK

--- LAURELFK.g01 (geometry) --- (continued)

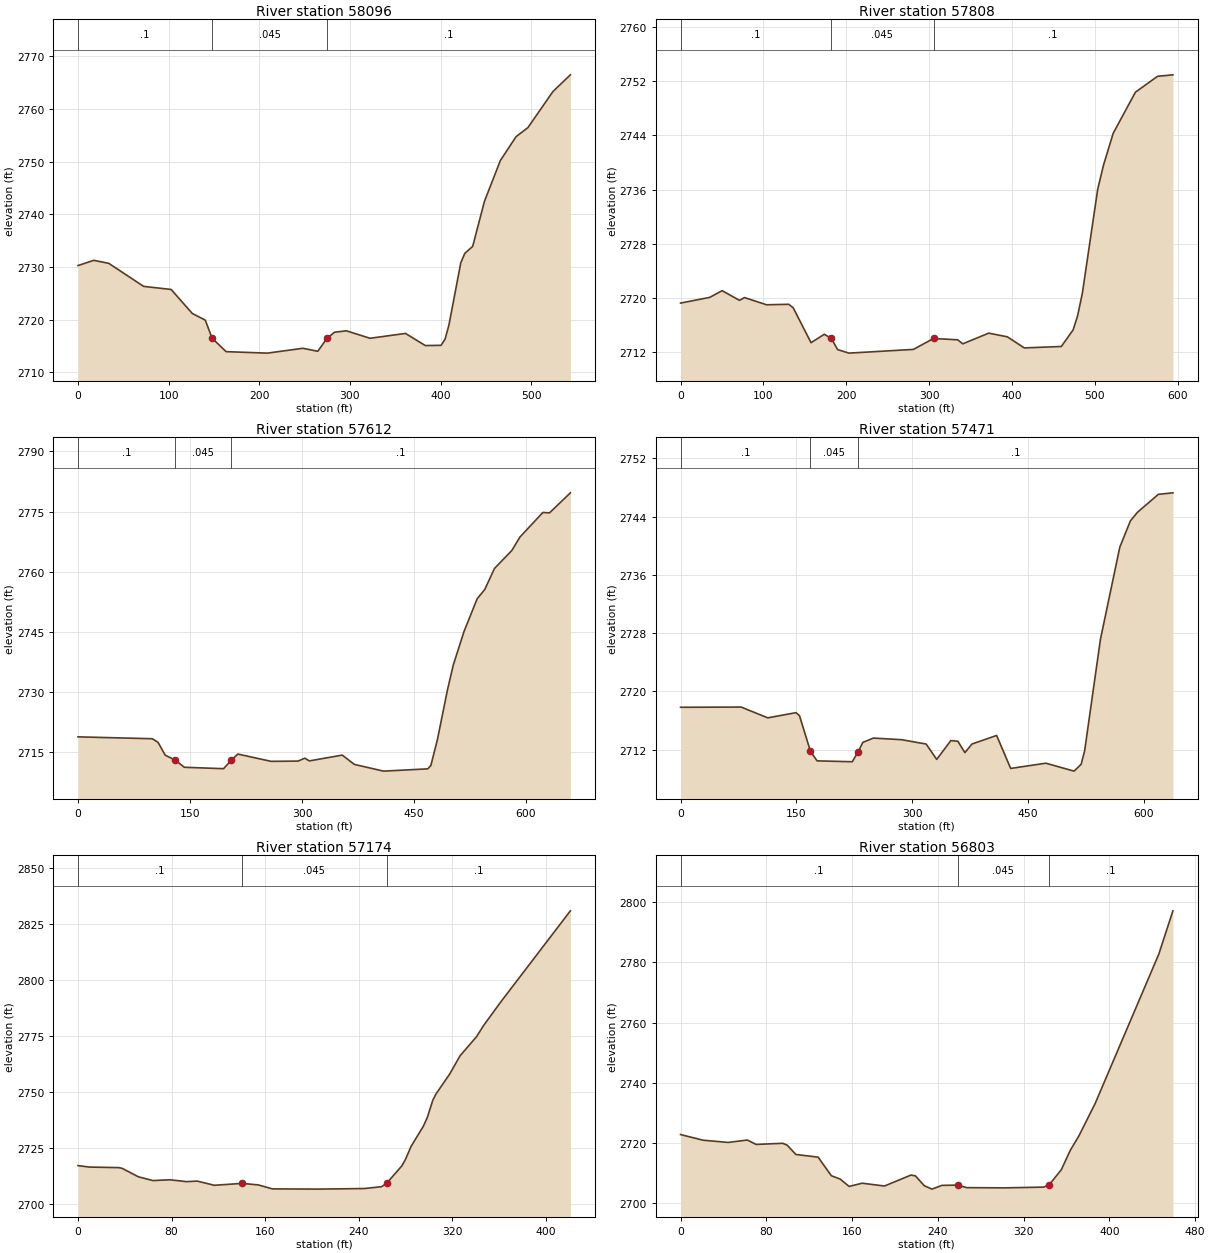
Type RM Length L Ch R = 1 ,58096   ,288.5,288.5,288.5
XS GIS Cut Line= 2
2369083.52956082696349.0309998162369298.44643519695850.116827163
#Sta/Elev= 30
       0 2730.25    17.3 2731.24    33.9 2730.67    72.4 2726.29   102.7 2725.71
   126.1 2721.15   140.4 2719.88   147.9 2716.46   163.4  2713.9   208.9 2713.62
   248.1 2714.54   264.5 2713.97   274.6  2716.4   282.9 2717.58     296 2717.86
   322.1 2716.44   361.3 2717.36   383.1 2715.06   400.5  2715.1   404.9 2716.25
   409.2 2718.95   422.3 2730.78   426.7 2732.56   435.4 2733.88   448.4 2742.45
   465.9 2750.17   483.3 2754.73   496.3 2756.43     524  2763.3   543.2 2766.46
#Mann= 3 ,-1,0
       0      .1       0   147.9    .045       0   274.6      .1       0
Bank Sta=147.9,274.6
XS Rating Curve= 0 ,0
Exp/Cntr(USF)=0,0
Exp/Cntr=0.3,0.1

Type RM Length L Ch R = 1 ,57808   ,196.2,196.2,196.2
XS GIS Cut Line= 2
2369260.72376894696450.6056994452369656.67742008696007.365473939
#Sta/Elev= 30
       0 2719.25    35.2 2720.09    50.2 2721.08    71.2 2719.65    77.2 2720.06
   103.8    2719   130.6 2719.07     136 2718.55   157.5  2713.4   173.5 2714.64
   181.9 2714.05   189.6 2712.38   203.3 2711.86   281.1 2712.41   305.4 2714.02
   334.5 2713.83   340.6 2713.23     372 2714.81   394.4 2714.27   414.9 2712.63
   459.6 2712.84   473.9  2715.3   479.3 2717.39     485  2720.7   503.5 2736.04
   510.5 2739.61   522.2 2744.31     549 2750.38   575.7 2752.73   594.3 2752.95
#Mann= 3 ,-1,0
       0      .1       0   181.9    .045       0   305.4      .1       0
Bank Sta=181.9,305.4
XS Rating Curve= 0 ,0
Exp/Cntr=0.3,0.1

Type RM Length L Ch R = 1 ,57612   ,140.3,140.3,140.3
XS GIS Cut Line= 2
2369382.87806441696494.867450285 2369981.5750716696218.545754661
#Sta/Elev= 30
       0 2718.82    99.5 2718.35   107.2 2717.44   116.8 2714.24   130.1 2713.04
   142.4 2711.23   194.9 2710.88  205.38 2713.02     214 2714.53   258.5 2712.71
   294.6 2712.77   303.7  2713.5   309.8 2712.82   353.9 2714.27     370 2711.95
   409.2 2710.27   468.4 2710.84   472.5 2711.65   481.3 2718.12   494.8 2730.55
   502.6 2736.76   516.9 2745.08   534.5 2753.25   544.8  2755.6   557.7 2760.81
     581 2765.31   591.8 2768.65   622.6  2774.8   631.4 2774.68   659.4 2779.69
#Mann= 3 ,-1,0
       0      .1       0   130.1    .045       0  205.38      .1       0
Bank Sta=130.1,205.38
XS Rating Curve= 0 ,0
Exp/Cntr(USF)=0,0
Exp/Cntr=0.3,0.1

Type RM Length L Ch R = 1 ,57471   ,297.9,297.9,297.9
XS GIS Cut Line= 3
2369426.96556677696563.8697236162369529.25958549 696588.07229775
2369996.47934984696332.100563652
#Sta/Elev= 30
       0  2717.8    78.5 2717.83     113 2716.35   149.5 2717.06   154.1 2716.65
   168.3 2711.75   176.9 2710.44   222.5 2710.32   230.2 2711.71   236.1 2712.97
   249.8 2713.57   286.3 2713.35   318.2 2712.75   331.9 2710.64   350.2 2713.23
   359.3 2713.13   368.4 2711.57   377.5 2712.75   409.5 2713.93   427.7  2709.4
   473.3 2710.12   509.8 2709.03     519 2709.97   523.5  2711.8     544 2727.13
   569.1  2739.8   582.8  2743.4   591.9 2744.58     619 2747.05   637.9 2747.26
#Mann= 3 ,-1,0
       0      .1       0   168.3    .045       0   230.2      .1       0
Bank Sta=168.3,230.2
XS Rating Curve= 0 ,0
Exp/Cntr=0.3,0.1

Type RM Length L Ch R = 1 ,57174   ,370.9,370.9,370.9
XS GIS Cut Line= 2
2369504.65187313696636.8660994242369720.70299479696998.085549468
#Sta/Elev= 30
       0 2717.25     9.7  2716.6    34.9 2716.35    37.7 2716.04    51.6 2712.26
      64 2710.59    78.6 2710.93    92.6 2710.11     102 2710.34   116.5 2708.48
   140.2 2709.33   154.2 2708.64   166.1 2706.88   205.4 2706.77   244.9 2707.04
   259.4 2707.85  263.79 2709.33   276.9  2717.2   279.9 2719.99   284.7  2725.8
   295.2 2734.78   298.7 2738.85   303.3 2746.43   306.1 2749.23   317.8 2758.12
   326.6 2766.19   340.6 2774.65   346.9 2779.82   361.5 2790.25   420.9 2830.77
#Mann= 3 ,-1,0
       0      .1       0   140.2    .045       0  263.79      .1       0
Bank Sta=140.2,263.79
XS Rating Curve= 0 ,0
Exp/Cntr(USF)=0,0
Exp/Cntr=0.3,0.1

Type RM Length L Ch R = 1 ,56803   ,267.1,267.1,267.1
XS GIS Cut Line= 2
2369186.58645832696632.8318985372369299.36119967 697078.05964813
#Sta/Elev= 30
       0 2722.77      21 2720.89    44.4 2720.14    62.3 2720.95    70.5 2719.48
    95.3 2719.86    99.4 2719.26   107.6 2716.14   128.3 2715.26   140.7 2709.07
   148.9 2707.97   157.2 2705.52   169.5 2706.59   190.2 2705.65   214.9 2709.29
   219.1 2709.03   227.3 2705.77   234.5 2704.62   243.8 2705.87   258.4 2705.95
   267.1 2705.11   302.2 2705.04   338.7 2705.29     344 2706.11   355.2 2711.08
   363.5 2717.48   371.7 2722.37   386.8 2733.12   446.1 2782.72   459.3 2797.16
#Mann= 3 ,-1,0
       0      .1       0   258.4    .045       0     344      .1       0
Bank Sta=258.4,344
XS Rating Curve= 0 ,0
Exp/Cntr=0.3,0.1

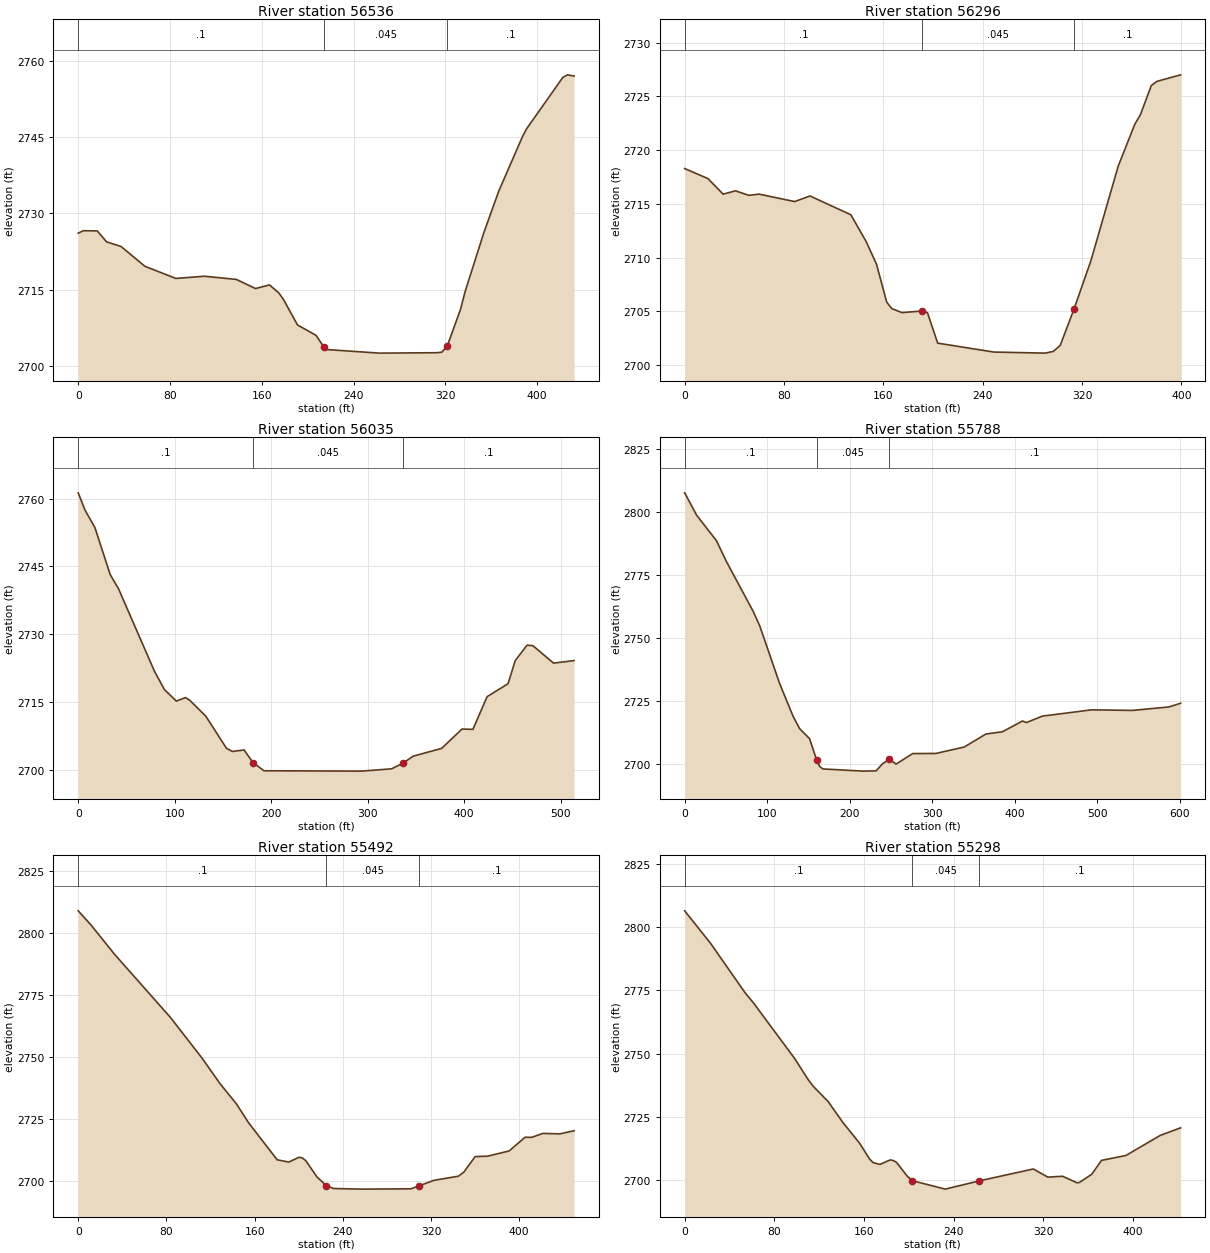
Type RM Length L Ch R = 1 ,56536   ,239.8,239.8,239.8
XS GIS Cut Line= 2
2368945.36871301696636.8660994242369018.28693824697062.862046844
#Sta/Elev= 30
       0 2726.11     4.4  2726.6    16.6 2726.56    24.7 2724.42    37.4 2723.49
    58.1 2719.61    85.1 2717.22   109.9 2717.65   137.8 2717.03   154.5 2715.23
   166.7 2715.95   174.8 2714.38   178.9 2713.08   191.1 2708.08   207.3 2706.03
   214.1 2703.73   215.4 2703.26   262.6 2702.54   312.8 2702.62   316.9 2702.73
   321.5 2703.88   333.1 2711.09   337.1 2714.57   353.4 2726.15   366.5 2734.38
   387.3 2745.16   390.8 2746.65   422.4 2756.75   426.4 2757.24   432.2 2756.99
#Mann= 3 ,-1,0
       0      .1       0   214.1    .045       0   321.5      .1       0
Bank Sta=214.1,321.5
XS Rating Curve= 0 ,0
Exp/Cntr(USF)=0,0
Exp/Cntr=0.3,0.1

Type RM Length L Ch R = 1 ,56296   ,260.4,260.4,260.4
XS GIS Cut Line= 3
2368693.13016369696650.9677659622368768.65263339696969.814949268
2368799.60402938697034.459883794
#Sta/Elev= 30
       0 2718.29    18.7 2717.36      31 2715.91    40.9 2716.22    51.6  2715.8
    59.8 2715.91    88.6 2715.22   100.9 2715.74   133.8 2713.99   146.1  2711.5
   154.4 2709.41   162.6 2705.89   163.9 2705.68   166.7 2705.27   174.9 2704.89
   191.4 2705.04   195.5 2704.88   203.7 2702.05   248.9 2701.22   290.2 2701.12
   296.8 2701.28   302.4 2701.85   313.5 2705.23     327 2709.69   349.1 2718.53
   362.4 2722.41   366.9 2723.29   375.7 2726.01   380.2  2726.4   399.3 2727.01
#Mann= 3 ,-1,0
       0      .1       0   191.4    .045       0   313.5      .1       0
Bank Sta=191.4,313.5
XS Rating Curve= 0 ,0
Exp/Cntr=0.3,0.1

Type RM Length L Ch R = 1 ,56035   ,247.7,247.7,247.7
XS GIS Cut Line= 2
2368285.68085598696850.4674774942368759.31316698697049.891608442
#Sta/Elev= 30
       0 2761.26       7 2757.46    17.3 2753.59    33.1 2743.22    41.8 2740.05
    79.1 2721.79    89.4 2717.77   101.7 2715.24   111.2 2716.01   115.5 2715.43
   132.2 2711.91   153.6 2704.82   159.7  2704.1   171.9 2704.44   181.1 2701.65
   192.5 2699.84   293.5 2699.76   324.7 2700.27   336.8 2701.56   347.1 2703.06
   376.6 2704.79   397.7 2709.06     409 2708.99   423.7 2716.21   445.4 2719.08
   452.9 2724.21   465.2 2727.61   471.3 2727.46   492.6 2723.62   513.9  2724.2
#Mann= 3 ,-1,0
       0      .1       0   181.1    .045       0   336.8      .1       0
Bank Sta=181.1,336.8
XS Rating Curve= 0 ,0
Exp/Cntr(USF)=0,0
Exp/Cntr=0.3,0.1

Type RM Length L Ch R = 1 ,55788   ,295.7,295.7,295.7
XS GIS Cut Line= 2
2368237.98374948 697188.306317932368834.30987456697115.262936414
#Sta/Elev= 30
       0 2807.68    14.3 2798.89    38.5 2788.65    50.6 2780.37    82.8 2760.71
    90.9 2754.87     115 2731.95   131.2 2719.01   139.2 2714.01   151.3    2710
   159.7 2701.72   163.4 2699.03   167.4 2697.99   215.8 2697.11   231.9 2697.23
     240 2700.12     248 2701.79   256.1 2699.91   276.2 2704.08   304.4 2704.14
   338.7 2706.69   364.9 2711.85     385 2712.76   409.2 2717.02     414 2716.41
   433.4 2718.97     493 2721.46   542.2 2721.23   586.5  2722.6   600.8 2724.08
#Mann= 3 ,-1,0
       0      .1       0   159.7    .045       0     248      .1       0
Bank Sta=159.7,248
XS Rating Curve= 0 ,0
Exp/Cntr=0.3,0.1

Type RM Length L Ch R = 1 ,55492   ,194.4,194.4,194.4
XS GIS Cut Line= 2
2368523.63010313697530.322469363 2368804.6368331697179.064056897
#Sta/Elev= 30
       0 2808.89    11.7 2803.15    32.9 2791.43    83.7 2765.96   112.2 2749.68
   128.9 2739.19   143.5 2731.21   154.5 2723.61   180.5 2708.68     191  2707.8
   200.4 2709.74   203.3 2709.42   206.4 2708.37   216.6 2701.77     225 2698.34
   231.7 2697.15     257  2696.9   301.8 2697.03   308.8 2698.17   322.8 2700.46
   344.7 2702.09   349.8 2703.75     360    2710   371.2 2710.15   390.8 2712.26
   405.3 2717.78   411.3 2717.73   421.5 2719.33   436.9 2719.14   449.8  2720.4
#Mann= 3 ,-1,0
       0      .1       0     225    .045       0   308.8      .1       0
Bank Sta=225,308.8
XS Rating Curve= 0 ,0
Exp/Cntr(USF)=0,0
Exp/Cntr=0.3,0.1

Type RM Length L Ch R = 1 ,55298   ,245.8,245.8,245.8
XS GIS Cut Line= 2
2368760.66063065697646.5862193312368935.91506703 697240.50459193
#Sta/Elev= 30
       0 2806.45    23.3 2793.46    53.8 2774.08    61.6 2769.87    98.1 2748.01
   110.4  2739.5   114.8 2736.97   127.9 2731.03   140.9 2722.84   155.9 2714.58
     165  2708.2   168.1 2706.85   174.2 2706.12   183.3 2707.92   186.3 2707.64
   188.9 2706.95   198.5 2701.47   202.9  2699.7   232.4 2696.35   262.9 2699.63
   310.9 2704.32   323.9  2701.1     337 2701.44   350.1 2698.83   352.1    2699
   363.1 2702.25   371.8 2707.72   393.6 2709.68   424.1 2717.59   442.3 2720.61
#Mann= 3 ,-1,0
       0      .1       0   202.9    .045       0   262.9      .1       0
Bank Sta=202.9,262.9
XS Rating Curve= 0 ,0
Exp/Cntr=0.3,0.1

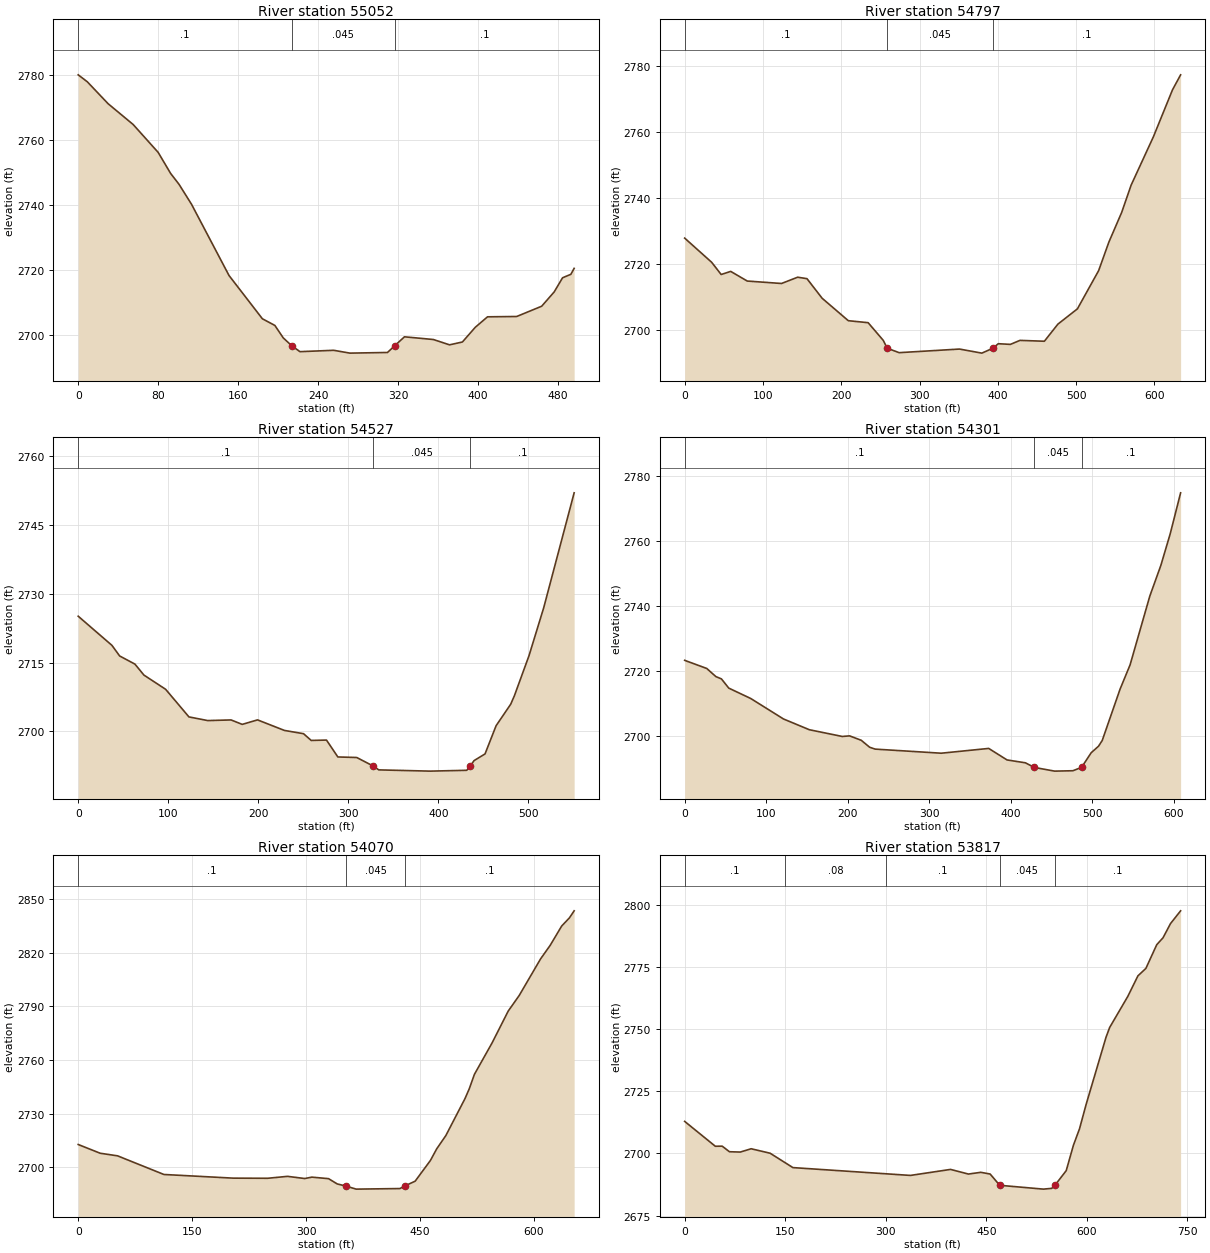
Type RM Length L Ch R = 1 ,55052   ,254.3,254.3,254.3
XS GIS Cut Line= 2
2369011.02634319697761.8911031642369152.03330447697285.992608855
#Sta/Elev= 30
       0 2780.16     9.1 2778.02    29.9 2771.28      55 2764.87      80  2756.3
    92.5 2749.81   100.9 2746.47   113.4 2740.33   150.9 2718.42   184.3  2705.1
   196.8 2703.05   205.2 2699.22   213.5 2696.85   221.9 2694.98   255.7  2695.4
   271.9 2694.53   309.5 2694.73   316.9 2696.85   326.5 2699.55   355.4 2698.72
   371.6 2697.08   384.5 2697.96   397.3 2702.46   409.6  2705.7   438.8  2705.8
   463.8 2708.96   476.3 2713.35   484.7 2717.71     493 2718.78   496.3 2720.61
#Mann= 3 ,-1,0
       0      .1       0   213.5    .045       0   316.9      .1       0
Bank Sta=213.5,316.9
XS Rating Curve= 0 ,0
Exp/Cntr(USF)=0,0
Exp/Cntr=0.3,0.1

Type RM Length L Ch R = 1 ,54797   ,270.9,270.9,270.9
XS GIS Cut Line= 2
 2369275.4254763697875.133094197 2369382.9193756697250.873476303
#Sta/Elev= 30
       0 2727.91    34.5 2720.58    46.6 2716.89    58.8 2717.83    79.9 2714.91
   123.7 2714.17   144.3 2716.07   156.2 2715.63   175.5 2709.71     209  2702.9
   234.3  2702.3   253.6 2696.95   258.6 2694.58   273.9 2693.22     351 2694.31
   379.5 2693.08   393.6 2694.55   400.5 2695.93     416 2695.73   428.2 2696.94
   459.4 2696.68   476.7 2701.87   501.6 2706.49   528.7 2718.06   541.8 2726.72
     558 2735.62   570.2 2743.95   598.6 2758.58     623  2772.8   633.4 2777.36
#Mann= 3 ,-1,0
       0      .1       0   258.6    .045       0   393.6      .1       0
Bank Sta=258.6,393.6
XS Rating Curve= 0 ,0
Exp/Cntr=0.3,0.1

Type RM Length L Ch R = 1 ,54527   ,225.3,225.3,225.3
XS GIS Cut Line= 3
2369477.93717586697936.4471428792369580.52160536697653.562806985
2369627.15089149697407.981899999
#Sta/Elev= 30
       0 2725.13    37.5 2718.77      46 2716.47      63 2714.69      73  2712.3
    97.1  2709.2     123 2703.18   143.9 2702.38   169.8 2702.52   182.2 2701.55
   199.2 2702.53   229.1 2700.23   250.3 2699.52   258.8 2698.05   275.8 2698.13
   288.4 2694.45   309.4 2694.33     327 2692.54   333.9 2691.63   390.9 2691.36
   431.6 2691.54   435.7 2692.53   439.7 2693.65   451.9 2695.11   464.2 2701.26
   480.4 2705.94   484.5 2707.78   500.8 2716.55   517.1 2726.99   550.9 2752.03
#Mann= 3 ,-1,0
       0      .1       0     327    .045       0   435.7      .1       0
Bank Sta=327,435.7
XS Rating Curve= 0 ,0
Exp/Cntr(USF)=0,0
Exp/Cntr=0.3,0.1

Type RM Length L Ch R = 1 ,54301   ,231,231,231
XS GIS Cut Line= 2
2369596.75163239698061.3373849762369874.01119737697519.564102146
#Sta/Elev= 30
       0 2723.22    27.1 2720.72    38.3 2718.22    45.1 2717.51    54.1 2714.68
    81.1 2711.48   121.3 2705.18     153 2701.88   193.4 2699.81   202.4 2699.99
   216.7 2698.63     227 2696.49   233.8 2695.92   314.8 2694.66   373.1 2696.13
   395.6 2692.59   418.1 2691.71     429 2690.29     454 2689.15   476.5 2689.27
   487.1 2690.32   498.9 2694.82   507.9 2696.82   512.4 2698.57   534.3 2714.36
   546.6 2721.84   570.8 2742.98   584.3 2752.38   595.8  2762.1   608.6 2774.73
#Mann= 3 ,-1,0
       0      .1       0     429    .045       0   487.1      .1       0
Bank Sta=429,487.1
XS Rating Curve= 0 ,0
Exp/Cntr=0.3,0.1

Type RM Length L Ch R = 1 ,54070   ,252.8,252.8,252.8
XS GIS Cut Line= 2
2369738.33636339698109.9532352022370141.21339561697596.285019122
#Sta/Elev= 30
       0 2712.64    28.9 2707.74    51.8 2706.28   112.8 2695.83   203.9 2693.78
   249.3  2693.7   275.5 2694.78   298.2 2693.56   307.6 2694.34   329.5 2693.49
   340.9 2690.54   352.3 2689.33   365.9 2687.62   423.5 2687.94   430.8 2689.57
   443.5 2692.07   463.6 2703.68   471.9 2710.21   483.9 2717.64     509 2738.27
   514.7 2743.82   521.5 2751.94   544.9 2769.69     566 2787.42   580.5 2796.19
   608.7 2816.75   621.2 2824.24   636.4 2835.11   646.6  2839.7   652.8 2843.63
#Mann= 3 ,-1,0
       0      .1       0   352.3    .045       0   430.8      .1       0
Bank Sta=352.3,430.8
XS Rating Curve= 0 ,0
Exp/Cntr(USF)=0,0
Exp/Cntr=0.3,0.1

Type RM Length L Ch R = 1 ,53817   ,228.7,228.7,228.7
XS GIS Cut Line= 2
2369829.47835242698342.6067032222370327.01813147697794.784720144
#Sta/Elev= 30
       0 2712.93    45.7 2702.92      56 2702.95    66.8 2700.71      83 2700.58
    99.2 2701.91   127.5 2700.11   161.5 2694.32   336.9 2691.17   396.7 2693.59
   423.4 2691.72   441.8 2692.42   455.8 2691.73   470.1 2687.19   535.3 2685.65
   547.7 2685.96   552.3 2687.14   569.3 2693.09   580.1 2703.35   589.1 2709.91
     599 2719.76   628.7 2746.82   634.1 2750.75   661.2 2763.27   676.3 2771.55
   688.2 2774.56   704.4 2784.11   713.7 2786.86     725 2792.63     740 2797.74
#Mann= 5 ,-1,0
       0      .1       0     150     .08       0     300      .1       0
   470.1    .045       0   552.3      .1       0
Bank Sta=470.1,552.3
XS Rating Curve= 0 ,0
Exp/Cntr=0.3,0.1

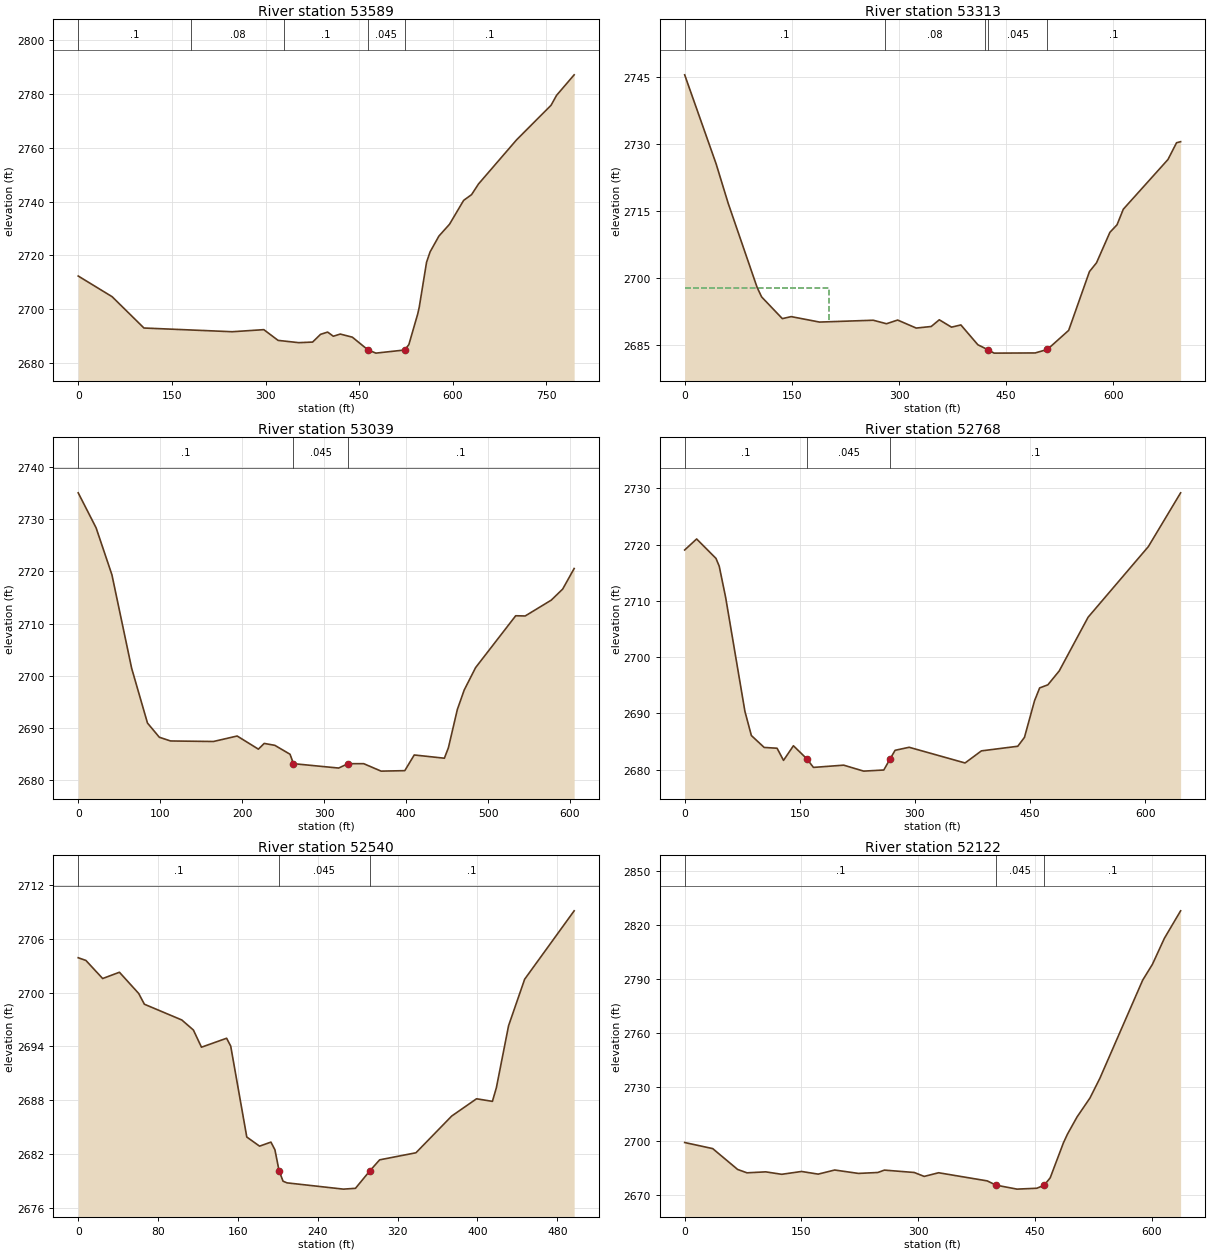
Type RM Length L Ch R = 1 ,53589   ,275.3,275.3,275.3
XS GIS Cut Line= 2
2370002.72441578698472.5425641992370551.64437218697898.442793287
#Sta/Elev= 30
       0 2712.29    54.3  2704.6   105.3 2692.95   246.7 2691.57   297.3 2692.34
   320.1 2688.35   353.3  2687.5   375.4 2687.72   388.2 2690.61   399.5 2691.43
   408.6 2689.89   419.7  2690.7   439.1 2689.54     464 2684.83   476.7 2683.61
     523 2684.78   529.6 2686.81   543.8 2698.21   546.2 2700.71   557.9  2717.4
   563.5 2721.23   577.7 2727.14   594.7 2731.55   617.3 2740.42     630 2742.56
   641.1 2746.52   702.2 2762.97   757.3  2775.8   766.1 2779.48   794.3 2787.12
#Mann= 5 ,-1,0
       0      .1       0     180     .08       0     330      .1       0
     464    .045       0     523      .1       0
Bank Sta=464,523
XS Rating Curve= 0 ,0
Exp/Cntr(USF)=0,0
Exp/Cntr=0.3,0.1

Type RM Length L Ch R = 1 ,53313   ,274.5,274.5,274.5
XS GIS Cut Line= 2
 2370243.2793508698662.2385177362370687.53781289698128.749409696
#Sta/Elev= 30
       0 2745.45      44 2725.53      61 2716.65   101.4 2697.88   107.7 2695.75
   136.7 2690.89   149.1 2691.34   188.8 2690.12   263.9 2690.53   282.5 2689.75
   298.1 2690.57   324.1 2688.78   345.1 2689.13   356.4 2690.63   373.5 2688.98
   386.6 2689.48   410.4 2685.04   424.6 2683.92   433.1 2683.17   490.7 2683.21
   507.7    2684   537.5 2688.26   566.6 2701.42   576.5 2703.39   595.2  2710.2
   605.2 2711.89     614 2715.38   676.5  2726.5   688.5 2730.25   694.2 2730.49
#Mann= 5 ,-1,0
       0      .1       0     280     .08       0     420      .1       0
   424.6    .045       0   507.7      .1       0
#XS Ineff= 2 , 0
           202.2 2697.85
Permanent Ineff=
       F       F
Bank Sta=424.6,507.7
XS Rating Curve= 0 ,0
Exp/Cntr=0.3,0.1

Type RM Length L Ch R = 1 ,53039   ,270.8,270.8,270.8
XS GIS Cut Line= 2
2370597.00716774698707.1937592482370936.00734146698206.127712996
#Sta/Elev= 30
       0 2735.09    21.8 2728.38    41.1 2719.37    65.2  2701.4    84.5 2690.89
      99 2688.16   112.7 2687.45     165 2687.35   193.9  2688.4   219.8 2685.88
   226.9 2686.98   239.9 2686.61   258.4  2684.9   262.6 2683.09   317.7 2682.25
   329.2 2683.09   348.3 2683.09   369.5 2681.66   398.4 2681.75   409.9 2684.76
   446.7 2684.14   451.6 2686.15   462.5 2693.49   470.9 2697.24   484.8 2701.54
   533.7 2711.49   545.3 2711.45   577.1 2714.49     591 2716.61     605 2720.56
#Mann= 3 ,-1,0
       0      .1       0   262.6    .045       0   329.2      .1       0
Bank Sta=262.6,329.2
XS Rating Curve= 0 ,0
Exp/Cntr(USF)=0,0
Exp/Cntr=0.3,0.1

Type RM Length L Ch R = 1 ,52768   ,228.6,228.6,228.6
XS GIS Cut Line= 3
2370946.62016774698752.1109990522370986.36224782 698624.90252275
2371191.40618541698154.652829491
#Sta/Elev= 30
       0 2719.06    15.6 2721.02    40.8 2717.56      45 2716.19    53.4 2710.62
    78.5 2690.38    86.9 2686.08   103.6 2683.96   120.4 2683.82   128.8 2681.66
   141.7 2684.26   159.2 2681.94   167.8 2680.41   207.2 2680.81   233.3 2679.75
   259.5 2679.95   267.9 2681.97   274.2 2683.45   292.5 2683.99   365.4  2681.2
   386.7 2683.35   434.1 2684.17   442.8 2685.75   455.9 2692.25   462.6 2694.54
   473.3 2695.09   488.1 2697.56   525.7  2707.1   604.3 2719.67   646.3 2729.22
#Mann= 3 ,-1,0
       0      .1       0   159.2    .045       0   267.9      .1       0
Bank Sta=159.2,267.9
XS Rating Curve= 0 ,0
Exp/Cntr=0.3,0.1

Type RM Length L Ch R = 1 ,52540   ,417.7,417.7,417.7
XS GIS Cut Line= 3
2371121.79429139698682.7944868352371224.48203119698614.199811993
2371175.65055953698243.991610484
#Sta/Elev= 30
       0  2703.9     7.7  2703.6    24.5 2701.58    41.3 2702.28    60.6 2699.91
    66.3 2698.71   103.8 2696.95   115.4 2695.83   123.5 2693.91   148.7 2694.91
   152.8 2694.03   168.9 2683.88   181.7 2682.86   193.1 2683.31   197.1 2682.45
   201.2 2680.14   205.2 2678.95   209.2 2678.76   265.7 2678.06   277.8 2678.15
   292.2  2680.1     302 2681.33   338.4 2682.12   374.2 2686.22   399.1 2688.15
     415 2687.86     419  2689.4   431.2 2696.31   447.3  2701.5   496.9 2709.14
#Mann= 3 ,-1,0
       0      .1       0   201.2    .045       0   292.2      .1       0
#XS Ineff= 2 , 0
           62.08 2693.81
Permanent Ineff=
       F       F
Bank Sta=201.2,292.2
XS Rating Curve= 0 ,0
Exp/Cntr(USF)=0,0
Exp/Cntr=0.3,0.1

Type RM Length L Ch R = 1 ,52122   ,362.8,362.8,362.8
XS GIS Cut Line= 3
2371156.14893768698691.8575418522371272.05140824698690.437414984
2371761.58657104698512.168192965
#Sta/Elev= 30
       0  2699.3      36 2695.93      68 2684.37      80  2682.5     104 2683.04
   124.6 2681.68   150.1 2683.25   171.4 2681.78   192.7 2684.05   223.1 2682.17
     248 2682.68   256.5    2684   294.8 2682.69   307.6 2680.51   326.1 2682.54
   388.5 2678.03   399.92675.668   426.8 2673.46   452.3 2673.95   461.7 2675.66
   469.4 2679.71   486.4 2699.12   491.5 2703.88   503.9 2713.48   520.5 2723.99
   533.2 2734.91   588.2 2789.34   600.7 2798.11   616.1 2812.57   636.9 2827.76
#Mann= 3 ,-1,0
       0      .1       0   399.9    .045       0   461.7      .1       0
Bank Sta=399.9,461.7
XS Rating Curve= 0 ,0
Exp/Cntr(USF)=0,0
Exp/Cntr=0.3,0.1

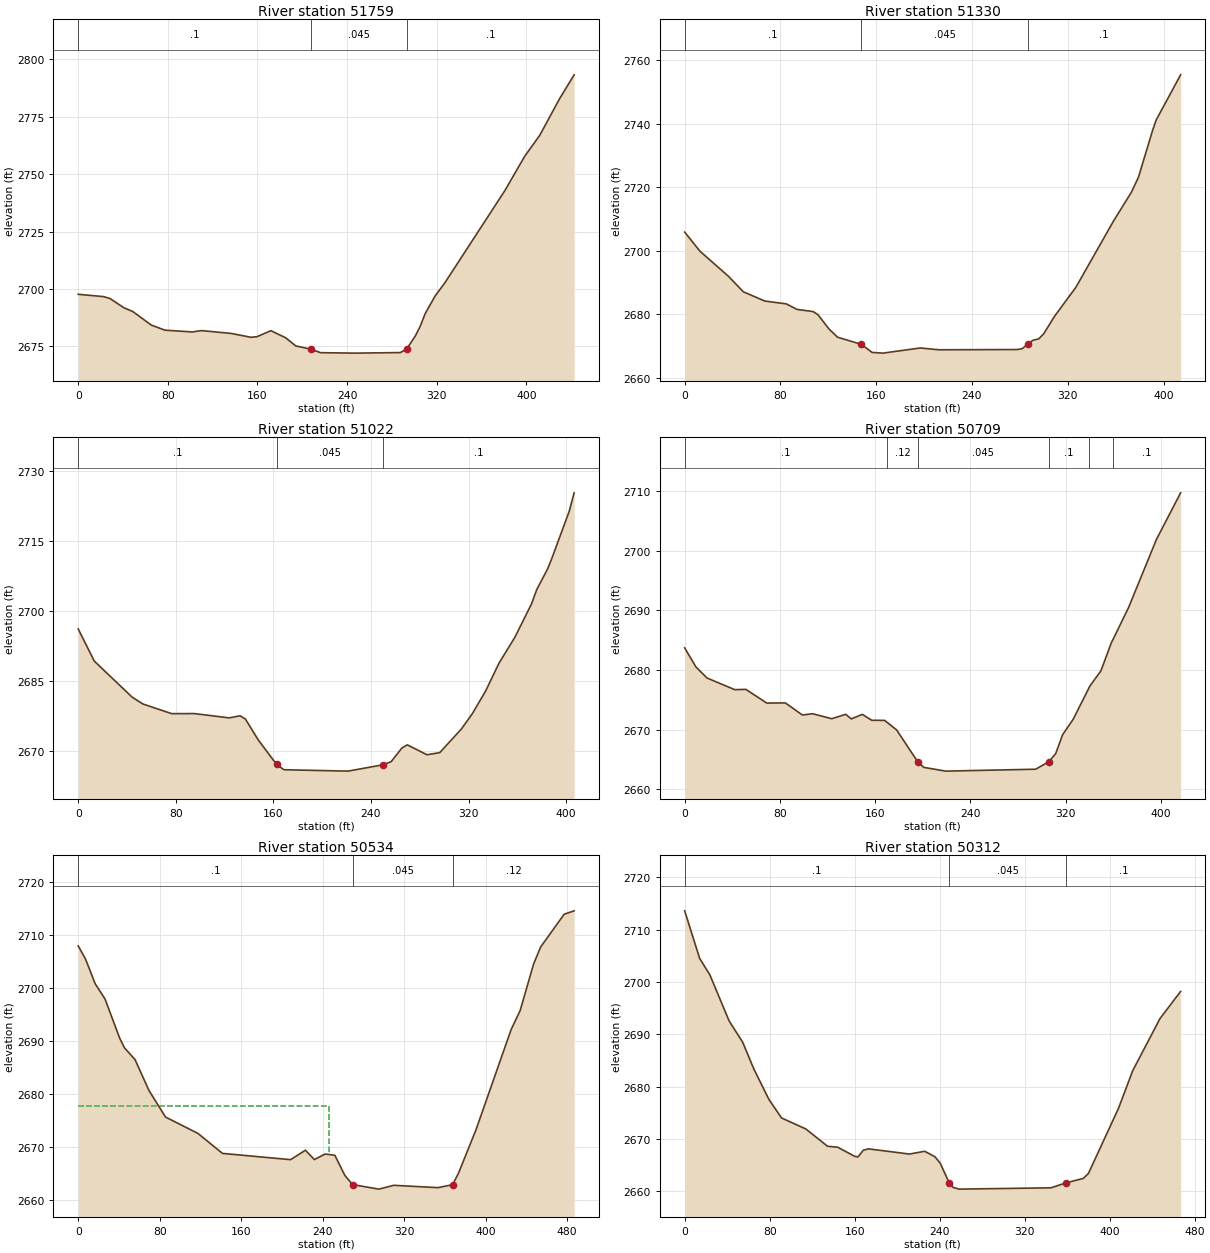
Type RM Length L Ch R = 1 ,51759   ,428.6,428.6,428.6
XS GIS Cut Line= 3
2371148.14035057698710.4528932932371280.67412816 698735.87885525
2371414.87226438699012.846462257
#Sta/Elev= 30
       0 2697.65    22.9 2696.63    28.5 2695.77    40.8  2691.8    48.9 2690.09
    65.2 2684.26    77.4 2682.03   101.9 2681.25     110 2681.84   136.4 2680.62
   154.2 2678.93   159.5 2679.17     172 2681.82   185.3 2678.68   194.2 2675.17
   207.5 2673.77   216.4 2672.22   247.5 2672.03   287.5 2672.27   293.1 2673.81
   300.9 2679.47   305.3 2683.74   309.7 2689.21   318.6 2696.93   327.2 2702.58
   380.9 2742.85   398.6  2757.8     412  2766.9   429.8 2782.93   442.7 2793.24
#Mann= 3 ,-1,0
       0      .1       0   207.5    .045       0   293.1      .1       0
Bank Sta=207.5,293.1
XS Rating Curve= 0 ,0
Exp/Cntr=0.3,0.1

Type RM Length L Ch R = 1 ,51330   ,308.9,308.9,308.9
XS GIS Cut Line= 2
2370838.61766102698813.4136150872371025.38924878699183.246564661
#Sta/Elev= 30
       0  2705.9    12.9 2699.84    36.7 2691.95      49 2687.12      67 2684.21
    84.9 2683.32    93.8 2681.59   107.3  2680.9   111.2 2679.97   120.7 2675.37
   127.7 2672.84   147.6 2670.59   156.6 2668.05   165.5 2667.83   196.9 2669.45
   212.4 2668.88   277.6 2668.96     282 2669.22   286.5 2670.69     291 2671.88
   295.8 2672.32     300 2673.95   308.9 2679.37   326.9 2688.59   358.2 2709.35
   373.2 2718.44   379.1 2723.17     391 2738.03     394 2741.24   414.3 2755.36
#Mann= 3 ,-1,0
       0      .1       0   147.6    .045       0   286.5      .1       0
Bank Sta=147.6,286.5
XS Rating Curve= 0 ,0
Exp/Cntr=0.3,0.1

Type RM Length L Ch R = 1 ,51022   ,312.2,312.2,312.2
XS GIS Cut Line= 2
2370555.46219557698917.2194475772370729.20291572699284.844739477
#Sta/Elev= 30
       0  2696.2    13.2 2689.31    44.2 2681.59      53 2680.13    76.6 2678.06
    95.3 2678.07   123.8 2677.15   132.7  2677.6   137.1 2676.89   147.7  2672.4
   162.7 2667.17   168.7 2666.05   221.2 2665.75   250.1 2667.12   256.6 2667.78
   265.4 2670.71   269.8 2671.38   285.9 2669.26   296.4 2669.71   314.1 2674.76
   322.9 2677.96     334 2682.89     345 2688.87     358 2694.41   371.6 2701.53
     376 2704.66   384.9 2709.08   388.1 2711.15   402.6 2721.42   406.6 2725.34
#Mann= 3 ,-1,0
       0      .1       0   162.7    .045       0   250.1      .1       0
Bank Sta=162.7,250.1
XS Rating Curve= 0 ,0
Exp/Cntr(USF)=0,0
Exp/Cntr=0.3,0.1

Type RM Length L Ch R = 1 ,50709   ,175.1,175.1,175.1
XS GIS Cut Line= 2
2370240.71451415 699033.046594342370454.74293752699390.599960434
#Sta/Elev= 30
       0 2683.71     9.5 2680.51    18.8 2678.66    42.1 2676.71    51.4 2676.76
      69 2674.46    84.6 2674.49    98.9 2672.46   107.4 2672.68   123.6 2671.84
   135.3 2672.58     140 2671.81   149.3 2672.57   157.2 2671.58     168 2671.56
   178.1 2669.96     196 2664.57   200.9 2663.69   219.3 2663.06   294.9 2663.38
   305.9 2664.63   311.7 2665.98   317.6 2669.18   326.5 2671.77   340.5 2677.33
   349.7 2679.85   358.4 2684.51     373 2690.48   396.4 2701.89   416.7 2709.69
#Mann= 6 ,-1,0
       0      .1       0     170     .12       0     196    .045       0
   305.9      .1       0     340     .12       0     360      .1       0
Bank Sta=196,305.9
XS Rating Curve= 0 ,0
Exp/Cntr(USF)=0,0
Exp/Cntr=0.3,0.1

Type RM Length L Ch R = 1 ,50534   ,221.9,221.9,221.9
XS GIS Cut Line= 2
2370036.75801659699063.2623717572370306.18203189699468.657385427
#Sta/Elev= 30
       0 2707.85     7.1 2705.41    16.7  2700.7    26.3 2697.85    40.7 2690.45
    45.5  2688.6    55.8  2686.4    69.5 2680.56    85.7 2675.57   117.6 2672.47
   141.6 2668.71   208.5 2667.53     223 2669.31   231.8 2667.55   242.4 2668.59
   251.9 2668.36   261.7 2664.56   269.3 2662.83   295.2 2661.97   309.7 2662.69
   353.1 2662.25   367.5 2662.81   373.2 2664.94   390.5 2673.19   424.9 2692.05
   433.8 2695.66     447 2704.44   453.9 2707.64     477 2713.83   486.8 2714.47
#Mann= 3 ,-1,0
       0      .1       0   269.3    .045       0   367.5     .12       0
#XS Ineff= 2 , 0
          245.81 2677.69
Permanent Ineff=
       F       F
Bank Sta=269.3,367.5
XS Rating Curve= 0 ,0
Exp/Cntr(USF)=0,0
Exp/Cntr=0.3,0.1

Type RM Length L Ch R = 1 ,50312   ,242.2,242.2,242.2
XS GIS Cut Line= 2
2369837.83748193 699161.463648362370097.18957142 699549.23279187
#Sta/Elev= 30
       0 2713.59    14.1  2704.5    23.7 2701.36    41.8 2692.56    54.6 2688.48
    64.9 2683.45    79.3 2677.54    91.1 2674.03   113.9 2671.93   134.4 2668.62
     144 2668.43   160.1 2666.68     163 2666.58   168.1 2667.87   172.9 2668.12
   211.4 2667.13   225.8 2667.66   235.5  2666.6   240.3 2665.41   248.8 2661.64
   252.4 2660.77   258.1 2660.43   344.6 2660.68     359 2661.65     375 2662.48
   379.8 2663.42   408.1 2675.88   421.5 2683.08   447.2 2693.04   466.5 2698.19
#Mann= 3 ,-1,0
       0      .1       0   248.8    .045       0     359      .1       0
Bank Sta=248.8,359
XS Rating Curve= 0 ,0
Exp/Cntr(USF)=0,0
Exp/Cntr=0.3,0.1

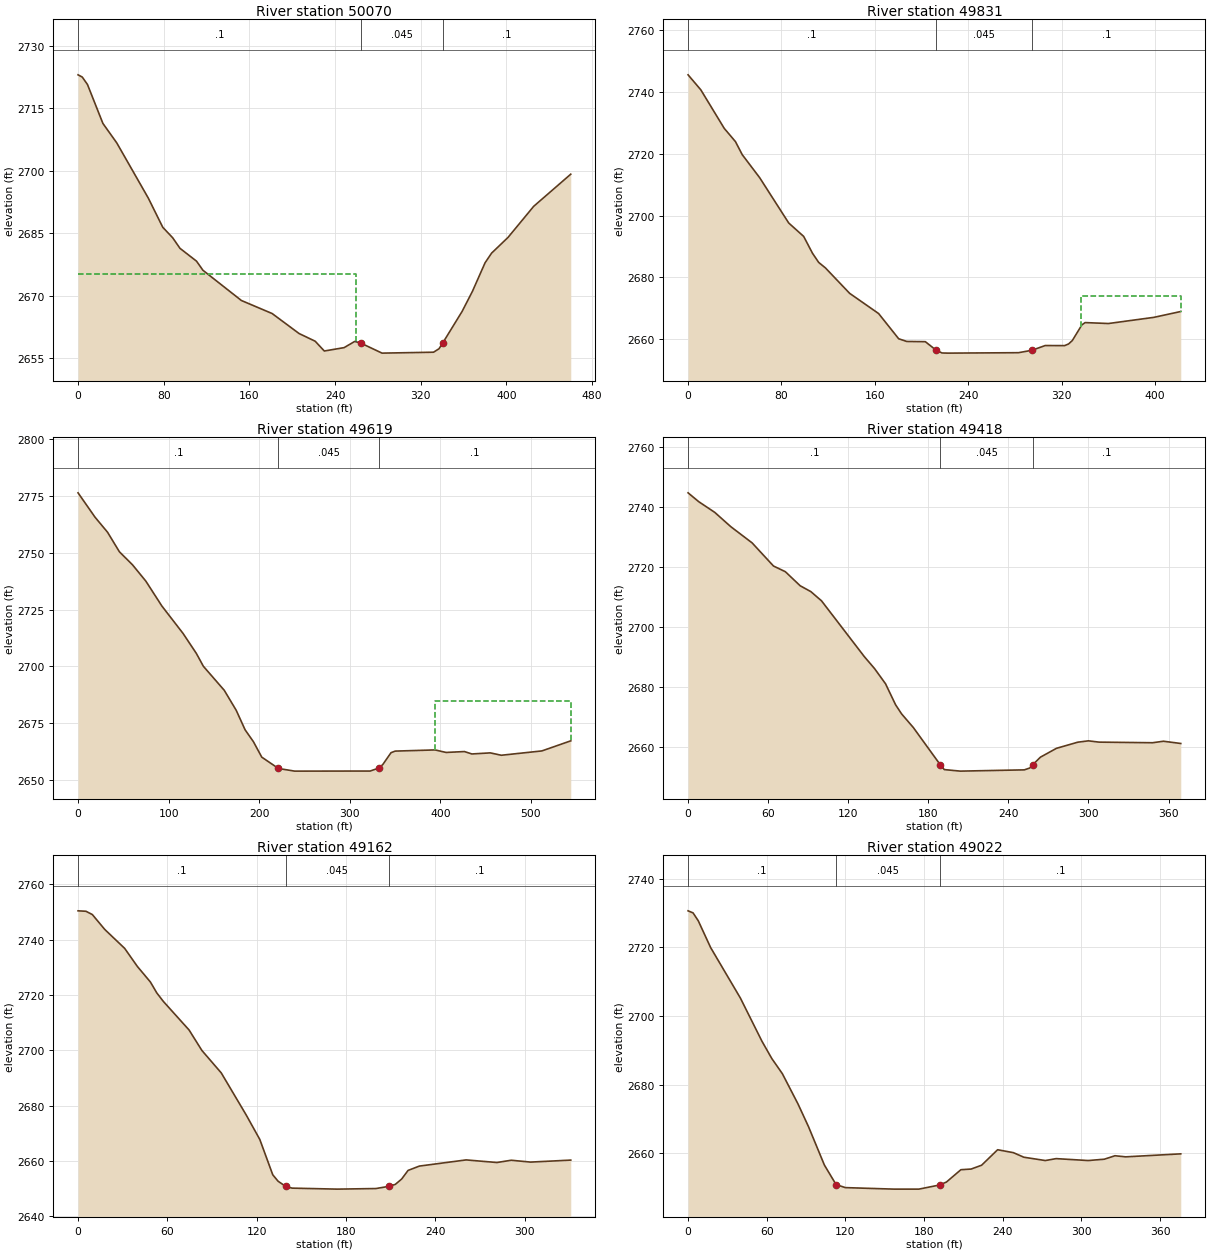
Type RM Length L Ch R = 1 ,50070   ,239.7,239.7,239.7
XS GIS Cut Line= 2
2369626.32704002699350.3122572122369933.52077708699692.757734598
#Sta/Elev= 30
       0 2723.04     3.9 2722.51     8.8 2720.72    23.2 2711.37    36.1 2706.71
    65.7 2693.38    79.1 2686.42    88.3 2683.92    95.2 2681.36   110.6 2678.29
   116.6  2676.1   152.5 2668.84   181.2 2665.71   206.4  2660.9   221.4 2659.06
   229.9 2656.71   248.4 2657.52   258.3 2659.01   263.9 2658.62   283.8  2656.2
   331.9 2656.42     337 2657.25   340.4 2658.61   358.5 2666.19   368.2 2671.04
     380  2677.9   386.1 2680.22   401.5 2684.01   425.4 2691.46     460 2699.18
#Mann= 3 ,-1,0
       0      .1       0   263.9    .045       0   340.4      .1       0
#XS Ineff= 2 , 0
          259.47 2675.23
Permanent Ineff=
       F       F
Bank Sta=263.9,340.4
XS Rating Curve= 0 ,0
Exp/Cntr(USF)=0,0
Exp/Cntr=0.3,0.1

Type RM Length L Ch R = 1 ,49831   ,211.7,211.7,211.7
XS GIS Cut Line= 2
2369447.55035697699576.930587836   2369782.44189699833.764695875
#Sta/Elev= 30
       0 2745.62    10.9 2740.77      31 2728.27    40.6 2723.98    46.4 2719.76
    61.3 2712.32    86.2 2697.63      99 2693.29   106.6 2687.81   111.9 2684.85
   117.6  2683.1   138.4 2674.84   163.2  2668.3   180.4 2660.13   187.3 2659.26
   203.2 2659.19   212.5 2656.42   217.5 2655.53   222.6 2655.48     283 2655.62
   294.5  2656.4   305.9 2657.94   322.5 2657.91   325.9 2658.45   329.1 2659.55
   337.3 2664.63   340.1 2665.37   360.1 2665.07     399 2667.07     422 2668.96
#Mann= 3 ,-1,0
       0      .1       0   212.5    .045       0   294.5      .1       0
#XS Ineff= 2 , 0
                          336.41         2674.14
Permanent Ineff=
       F       F
Bank Sta=212.5,294.5
XS Rating Curve= 0 ,0
Exp/Cntr(USF)=0,0
Exp/Cntr=0.3,0.1

Type RM Length L Ch R = 1 ,49619   ,201.1,201.1,201.1
XS GIS Cut Line= 3
2369283.88156263699763.2612152372369613.06239676699950.745323156
2369775.59499718699920.627787422
#Sta/Elev= 30
       0 2776.43    18.8 2765.67    32.6 2759.06    45.6  2750.5    60.2 2744.69
    74.9 2737.51    92.5 2726.61     116 2714.46   130.7 2705.65   138.4 2700.02
   161.5 2689.42   174.7 2680.59   184.5 2672.01   193.7 2666.77   202.9 2659.98
   221.3    2655   239.2 2653.83   322.6 2653.87   331.8 2655.14   336.4 2656.67
   345.6 2661.94   350.2 2662.65   394.2 2663.17   406.4 2662.06   426.7 2662.45
   434.9 2661.39   455.2 2661.87   467.4 2660.82   512.2 2662.73   544.1 2667.17
#Mann= 3 ,-1,0
       0      .1       0   221.3    .045       0   331.8      .1       0
#XS Ineff= 2 , 0
                          394.46         2684.85
Permanent Ineff=
       F       F
Bank Sta=221.3,331.8
XS Rating Curve= 0 ,0
Exp/Cntr(USF)=0,0
Exp/Cntr=0.3,0.1

Type RM Length L Ch R = 1 ,49418   ,256.1,256.1,256.1
XS GIS Cut Line= 2
2369252.17161018700083.1249928522369621.33287077700089.243687779
#Sta/Elev= 30
       0  2744.7       8 2741.75      20 2738.19      32 2733.43      48 2728.02
      64 2720.32    72.9 2718.42      84 2713.74      92 2711.79     100 2708.72
     132 2690.17   139.8 2686.11     148 2681.06   155.5 2674.09     160 2671.05
   168.8  2666.5   189.1 2654.03     192 2652.49     204 2651.98     252  2652.4
     256 2653.02   258.3 2654.11     264 2656.62     276 2659.57     292 2661.62
     300 2662.07     308 2661.64   348.1 2661.44   356.2 2661.94   369.2 2661.19
#Mann= 3 ,-1,0
       0      .1       0   189.1    .045       0   258.3      .1       0
Bank Sta=189.1,258.3
XS Rating Curve= 0 ,0
Exp/Cntr(USF)=0,0
Exp/Cntr=0.3,0.1

Type RM Length L Ch R = 1 ,49162   ,139.5,139.5,139.5
XS GIS Cut Line= 2
2369529.55244687700442.0884285592369656.00547536700136.153682218
#Sta/Elev= 30
       0 2750.43     5.3 2750.27     9.6 2749.08      18 2743.67    31.3 2736.87
    39.9 2730.29    48.6 2724.71    52.9 2720.76    57.3 2717.69    74.6 2707.35
    83.2 2699.96    96.2 2691.85     113 2676.61   122.1  2667.8   130.8 2655.03
   134.4 2652.69   139.5 2650.82   143.8  2650.2   174.1 2649.84   200.1 2650.05
   208.7 2650.84   213.1 2651.54   217.4 2653.49   221.7  2656.6   229.3 2658.17
   260.7  2660.4   281.4 2659.46     291 2660.28     304 2659.61     331 2660.33
#Mann= 3 ,-1,0
       0      .1       0   139.5    .045       0   208.7      .1       0
Bank Sta=139.5,208.7
XS Rating Curve= 0 ,0
Exp/Cntr(USF)=0,0
Exp/Cntr=0.3,0.1

Type RM Length L Ch R = 1 ,49022   ,162.5,162.5,162.5
XS GIS Cut Line= 3
2369742.36635701700449.0184685522369730.44336405700193.216074304
 2369705.5134697700076.153961682
#Sta/Elev= 30
       0 2730.66     3.8 2730.06     7.8 2727.75    17.2 2719.96    39.9 2705.24
    56.3 2692.69    63.9 2687.59    71.9 2683.21    83.9 2674.34    91.9 2667.72
     104 2656.55   112.9 2650.87     120 2649.99   157.1 2649.55     176 2649.55
     192 2650.77   197.1 2651.63   208.1 2655.21   215.9  2655.4   223.9 2656.52
   236.1 2661.03   248.1 2660.18   256.1 2658.85   272.5 2657.88   280.7 2658.44
   305.2 2657.88   317.5 2658.27   325.6 2659.28   333.8 2658.96   375.8 2659.83
#Mann= 3 ,-1,0
       0      .1       0   112.9    .045       0     192      .1       0
Bank Sta=112.9,192
XS Rating Curve= 0 ,0
Exp/Cntr(USF)=0,0
Exp/Cntr=0.3,0.1