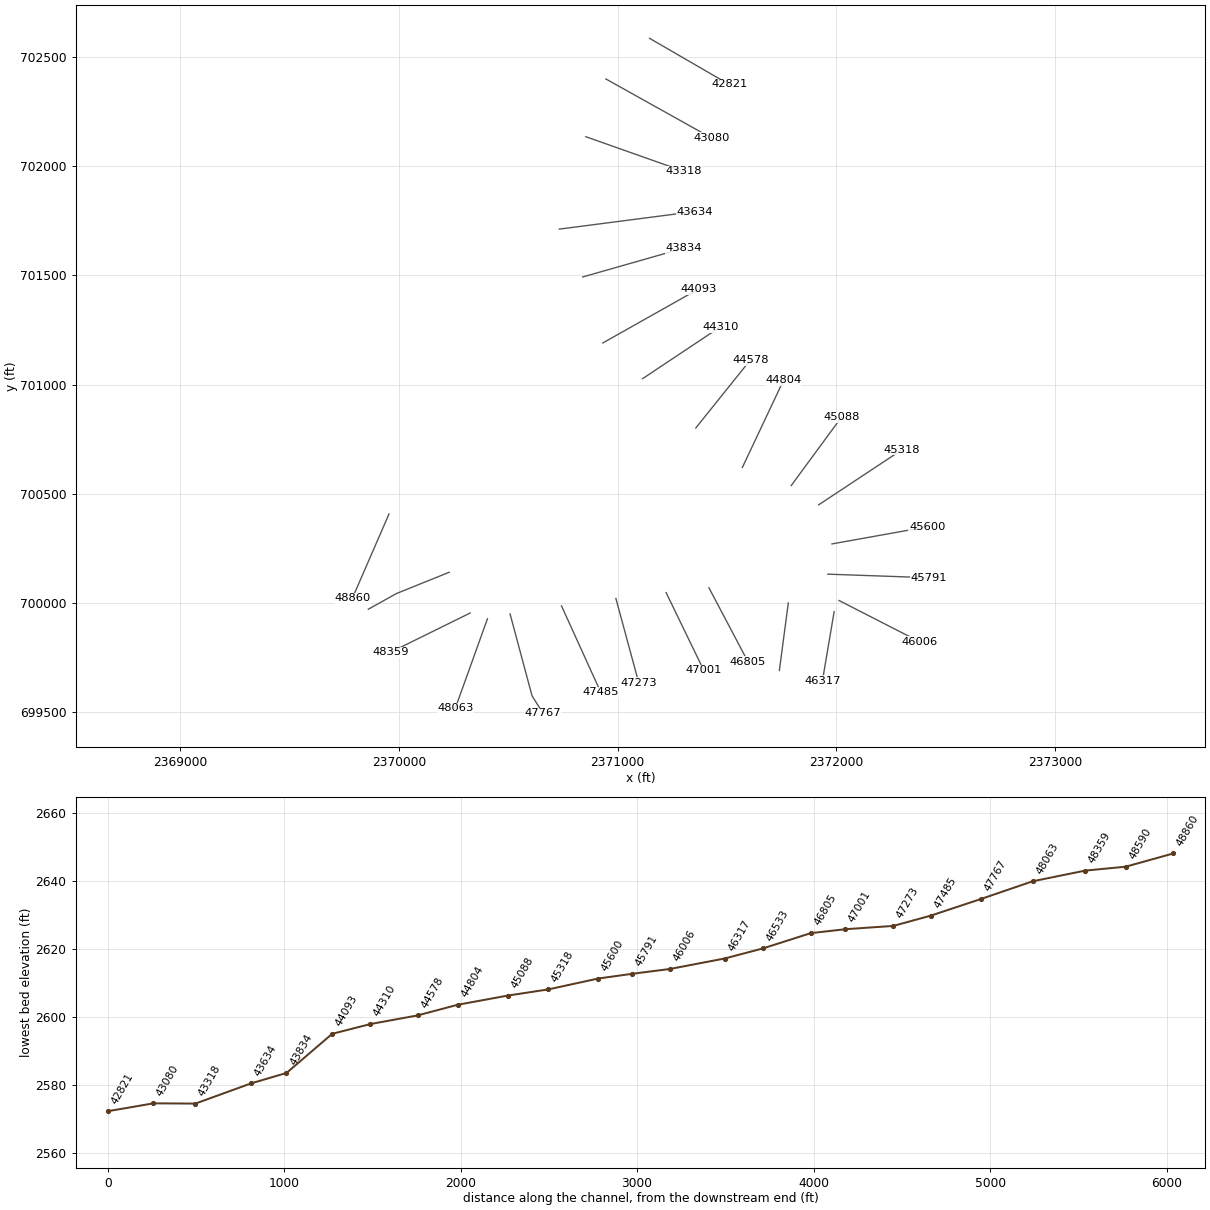
HEC-RAS study LAURELFK.prj: LAURELFK

--- LAURELFK.g01 (geometry) --- (continued)

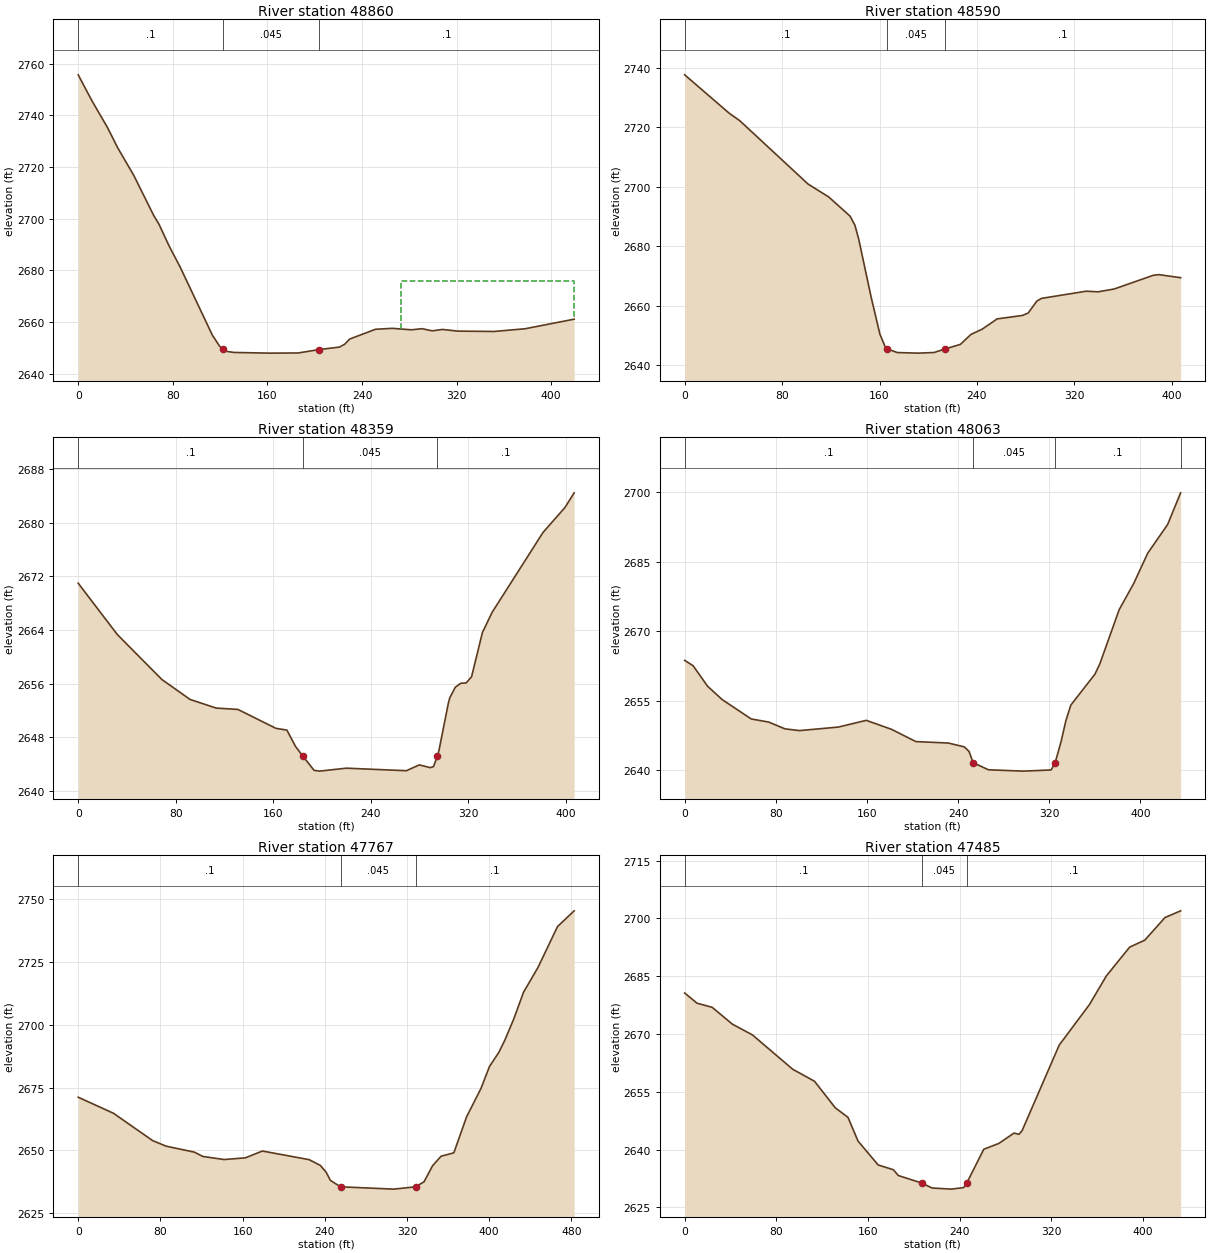
Type RM Length L Ch R = 1 ,48860   ,269.9,269.9,269.9
XS GIS Cut Line= 2
2369954.81241325700407.8299474442369787.89051192700023.042447623
#Sta/Elev= 30
       0 2755.69    11.6 2745.66    24.7 2735.36    33.4 2727.46    46.8 2716.96
    63.9 2701.24    68.3 2697.91      77 2689.37    86.1 2681.43   113.5 2654.94
   119.6  2650.7   122.6 2649.51   125.7 2648.69   131.7 2648.29   161.7 2648.03
     186 2648.09   203.5 2649.39   220.9 2650.37   225.3 2651.46   229.6 2653.48
   251.4 2657.26   265.5 2657.62   281.9 2657.05   290.7 2657.49   299.4 2656.65
   308.1 2657.19   321.2 2656.54   351.7 2656.41   377.9 2657.46   419.4 2661.16
#Mann= 3 ,-1,0
       0      .1       0   122.6    .045       0   203.5      .1       0
#XS Ineff= 2 , 0
                          272.65         2675.88
Permanent Ineff=
       F       F
Bank Sta=122.6,203.5
XS Rating Curve= 0 ,0
Exp/Cntr(USF)=0,0
Exp/Cntr=0.3,0.1

Type RM Length L Ch R = 1 ,48590   ,230.4,230.4,230.4
XS GIS Cut Line= 3
 2370230.1251596700141.188468695 2369988.4135752700043.636708176
2369860.51237808699972.098750463
#Sta/Elev= 30
       0 2737.59    36.6 2724.68    45.2  2722.2   101.3 2700.91   118.3 2696.57
   135.8 2690.13   139.8 2687.07   142.9  2682.4   153.1 2662.94   160.3 2650.48
   164.4 2646.48     166  2645.6   174.6 2644.32   191.9 2644.13   204.8 2644.34
   213.8 2645.53   226.4 2647.07     235  2650.4   244.3 2652.18   256.6 2655.63
   277.3 2656.78   282.1 2657.62   289.1 2661.58     293 2662.52   329.7 2664.92
   339.4 2664.72   352.6 2665.66   384.7 2670.26   389.3 2670.49   407.2 2669.46
#Mann= 3 ,-1,0
       0      .1       0     166    .045       0   213.8      .1       0
Bank Sta=166,213.8
XS Rating Curve= 0 ,0
Exp/Cntr(USF)=0,0
Exp/Cntr=0.3,0.1

Type RM Length L Ch R = 1 ,48359   ,296.4,296.4,296.4
XS GIS Cut Line= 2
2370325.76137089699954.556317496 2369960.6588446  699774.4831258
#Sta/Elev= 30
       0 2670.99    32.1 2663.34    68.7 2656.63    91.8 2653.66   113.3 2652.37
   131.1 2652.17   162.3 2649.35   171.3 2649.09   178.4 2646.65   184.6 2645.16
   193.6 2643.09     198 2642.97   220.1 2643.41   269.4 2643.03     280  2643.9
     289 2643.49   291.7 2643.65   294.9 2645.25   296.1 2646.02   303.9 2653.16
   305.1 2653.94   309.5 2655.47     314 2656.07   318.4 2656.11   322.9 2657.05
   331.8 2663.64   339.7 2666.63   381.5 2678.55   399.5 2682.27   407.1 2684.47
#Mann= 3 ,-1,0
       0      .1       0   184.6    .045       0   294.9      .1       0
Bank Sta=184.6,294.9
XS Rating Curve= 0 ,0
Exp/Cntr(USF)=0,0
Exp/Cntr=0.3,0.1

Type RM Length L Ch R = 1 ,48063   ,296.3,296.3,296.3
XS GIS Cut Line= 2
2370405.05965714699928.1235554132370258.02741805699518.415743112
#Sta/Elev= 30
       0 2663.73     7.4 2662.58    20.1 2658.16    32.9 2655.28    58.4  2651.1
    73.7 2650.43    88.1 2648.96   100.9 2648.59   134.9 2649.35   159.4  2650.8
   181.6 2648.86   202.9 2646.22   231.3 2645.91   245.4 2645.08   249.6  2644.1
   253.2 2641.67   266.6 2640.14     297 2639.85   321.6  2640.1   325.1 2641.59
   330.4 2646.23   334.6 2650.73   338.9 2654.07   360.1 2660.76   364.4 2662.98
   381.4 2674.68   394.1 2680.29   406.4 2686.83   423.9 2693.03   435.3 2699.86
#Mann= 4 ,-1,0
       0      .1       0   253.2    .045       0   325.1      .1       0
  435.29     .12       0
Bank Sta=253.2,325.1
XS Rating Curve= 0 ,0
Exp/Cntr(USF)=0,0
Exp/Cntr=0.3,0.1

Type RM Length L Ch R = 1 ,47767   ,282,282,282
XS GIS Cut Line= 3
2370508.61001345699950.3205277862370609.17370608699575.405296127
2370659.61772564699495.463189581
#Sta/Elev= 30
       0 2671.14    34.3 2664.76    72.4  2653.9    85.5 2651.68     113 2649.31
   121.3 2647.59     142 2646.36   162.7 2647.03   179.3 2649.74   224.8 2646.31
   235.7    2644   241.4 2641.27   245.5 2638.05   255.3 2635.51   307.1 2634.59
   328.4 2635.51   336.6 2637.51   344.9 2643.89   353.2 2647.69   365.6 2649.02
     378 2663.33     392 2674.61   400.3 2683.36   409.4 2688.97   415.2  2693.8
   423.9 2702.22   433.4 2712.85   447.6 2722.82   466.5 2738.99   482.7 2745.26
#Mann= 3 ,-1,0
       0      .1       0   255.3    .045       0   328.4      .1       0
Bank Sta=255.3,328.4
XS Rating Curve= 0 ,0
Exp/Cntr=0.3,0.1

Type RM Length L Ch R = 1 ,47485   ,212.2,212.2,212.2
XS GIS Cut Line= 2
2370743.89749732699987.0579634472370922.92597851699592.742068163
#Sta/Elev= 30
       0 2680.66    10.8 2678.01      24 2676.94    41.6 2672.58    59.2 2669.77
    94.3 2660.87   113.4 2657.74   131.5 2650.86   142.6 2648.38   151.4 2642.21
     169 2636.01   182.2 2634.78   186.6 2633.27   207.1 2631.31   216.1 2630.03
   232.9 2629.74   243.7 2630.14   246.4 2631.36   261.2 2640.09   274.4 2641.61
   287.6 2644.29     292 2643.97   294.7 2644.94   327.1 2667.14   353.5 2677.66
   368.3 2685.11   388.6 2692.57   401.8 2694.37   419.4 2700.23   433.1 2701.99
#Mann= 3 ,-1,0
       0      .1       0   207.1    .045       0   246.4      .1       0
Bank Sta=207.1,246.4
XS Rating Curve= 0 ,0
Exp/Cntr(USF)=0,0
Exp/Cntr=0.3,0.1

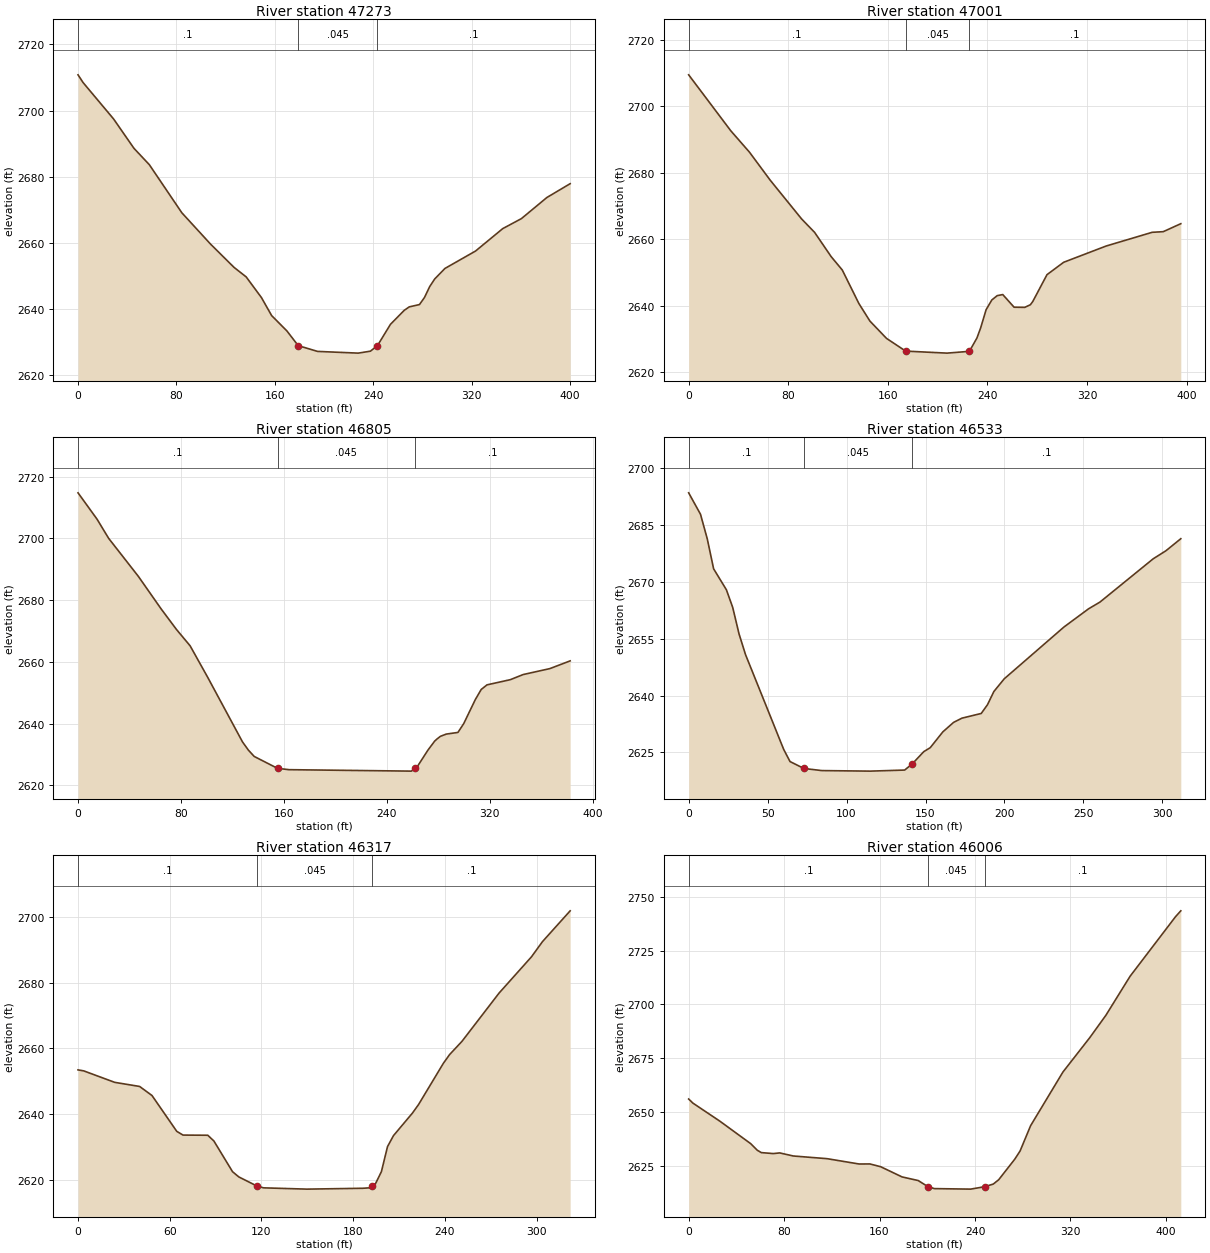
Type RM Length L Ch R = 1 ,47273   ,271.3,271.3,271.3
XS GIS Cut Line= 2
2370992.54091522700021.1151919312371097.15508008699634.916743004
#Sta/Elev= 30
       0 2710.83     4.1  2708.5    28.9  2697.5    45.5 2688.61      58 2683.66
    84.4 2669.14   107.7 2659.69   126.8 2652.65   136.7 2649.76   149.1 2643.52
   157.4 2638.07   169.8 2633.44     179 2628.99   194.7 2627.24   227.8 2626.72
   237.7 2627.31   243.4 2628.96     254 2635.42   265.2 2639.65   269.3  2640.7
   277.6  2641.4   281.7 2643.56   285.9 2646.83     290 2649.14   298.3 2652.31
   323.2 2657.58   345.3 2664.35   360.5 2667.38   381.2 2673.76   400.1 2677.93
#Mann= 3 ,-1,0
       0      .1       0     179    .045       0   243.4      .1       0
Bank Sta=179,243.4
XS Rating Curve= 0 ,0
Exp/Cntr=0.3,0.1

Type RM Length L Ch R = 1 ,47001   ,196,196,196
XS GIS Cut Line= 2
2371222.06217494700048.2449127152371394.29210621699692.454133637
#Sta/Elev= 30
       0 2709.48    33.8 2692.66    48.8 2686.23    65.6 2677.73    90.7 2666.13
   101.2 2662.06   114.5 2654.76   123.4 2650.75   136.7 2640.69   145.6 2635.39
   158.9 2630.19   174.3 2626.36   207.5 2625.75   225.5 2626.29   231.5 2630.27
   234.5  2633.3   238.9 2638.81   243.5 2641.74   247.8 2643.04   252.3 2643.37
   261.4 2639.56     270 2639.52   274.5 2640.32   276.4 2641.28   287.8 2649.35
   301.2 2653.08   335.3 2657.97   372.3  2662.1   381.2 2662.29   395.3 2664.69
#Mann= 3 ,-1,0
       0      .1       0   174.3    .045       0   225.5      .1       0
Bank Sta=174.3,225.5
XS Rating Curve= 0 ,0
Exp/Cntr(USF)=0,0
Exp/Cntr=0.3,0.1

Type RM Length L Ch R = 1 ,46805   ,272.6,272.6,272.6
XS GIS Cut Line= 2
2371417.90616801700070.2341397232371596.37596674699732.023036861
#Sta/Elev= 30
       0 2714.79    14.8 2706.24    23.8 2700.04    46.9 2687.71    64.6 2677.16
    76.5 2670.51    87.1 2665.21   100.7 2655.05   127.8 2634.07   132.4  2631.4
   136.9 2629.36     155  2625.5     164 2625.07     259  2624.6     262 2625.55
   263.5 2625.98   271.9 2631.41   277.1 2634.32   279.1 2635.07   281.6 2635.88
   286.1  2636.6   295.2 2637.14   299.7    2640   308.7 2647.78   313.3 2651.07
   317.8 2652.56   335.9 2654.24   345.9  2655.9   366.6 2657.82   382.4 2660.33
#Mann= 3 ,-1,0
       0      .1       0     155    .045       0     262      .1       0
Bank Sta=155,262
XS Rating Curve= 0 ,0
Exp/Cntr=0.3,0.1

Type RM Length L Ch R = 1 ,46533   ,215.7,215.7,215.7
XS GIS Cut Line= 2
2371780.91075609700000.8292822142371740.02482744699691.779762743
#Sta/Elev= 30
       0 2693.43     7.5 2687.78    11.8 2681.27    15.8 2673.41    23.9 2667.88
    27.9 2663.23    31.9 2656.26      36 2650.81    60.2  2625.8    64.2 2622.61
      73 2620.79    84.4 2620.23     115 2620.09   136.8 2620.37   141.62621.995
   148.9 2625.22     153 2626.27     161 2630.44   167.8 2632.94   173.1 2634.05
   185.3 2635.29   189.3 2637.62   193.3 2641.07   199.9 2644.43   237.7 2658.07
   253.3 2662.87   260.5 2664.64   294.2 2676.04   302.3 2678.17   311.7 2681.34
#Mann= 3 ,-1,0
       0      .1       0      73    .045       0   141.6      .1       0
Bank Sta=73,141.6
XS Rating Curve= 0 ,0
Exp/Cntr(USF)=0,0
Exp/Cntr=0.3,0.1

Type RM Length L Ch R = 1 ,46317   ,310.5,310.5,310.5
XS GIS Cut Line= 2
2371990.46363327 699960.868291762371936.75107832699643.331505803
#Sta/Elev= 30
       0 2653.48     3.7 2653.18      24 2649.68    40.3 2648.43    48.4 2645.67
    64.6 2634.75    68.7 2633.61    84.9 2633.56    88.9 2631.81   101.1 2622.45
   105.2 2620.86   117.3 2618.03   121.4 2617.53   149.8 2617.14   186.3  2617.4
   190.4 2617.52   192.6 2618.08   194.4 2618.57   198.5 2622.47   202.5  2630.1
   206.4 2633.44   218.8 2640.31   222.8 2642.91     239 2655.45   243.1 2658.13
   251.2 2662.17   275.5 2676.89   296.7 2687.94   303.9 2692.57     322 2701.95
#Mann= 3 ,-1,0
       0      .1       0   117.3    .045       0   192.6      .1       0
Bank Sta=117.3,192.6
XS Rating Curve= 0 ,0
Exp/Cntr=0.3,0.1

Type RM Length L Ch R = 1 ,46006   ,215.8,215.8,215.8
XS GIS Cut Line= 2
2372012.96014881700011.9859798152372380.08184442699823.892765398
#Sta/Elev= 30
       0 2655.96     3.6 2654.04    26.1 2645.68      52  2635.2    57.5 2632.15
    60.9 2631.04      71 2630.59    76.3  2630.9    87.7 2629.47     116 2628.22
   142.9 2625.74   151.9 2625.77   160.9 2624.49   178.9 2619.73   192.4 2618.05
   200.6  2615.2   205.9  2614.3   236.3 2614.06   248.2 2615.19   255.3 2616.41
   259.8 2618.39   273.3 2627.96   277.8 2631.81   286.6 2643.55   313.7 2668.51
   336.2  2684.5   349.7 2694.89     370 2713.05   408.1 2740.76   412.5 2743.47
#Mann= 3 ,-1,0
       0      .1       0   200.6    .045       0   248.2      .1       0
Bank Sta=200.6,248.2
XS Rating Curve= 0 ,0
Exp/Cntr(USF)=0,0
Exp/Cntr=0.3,0.1

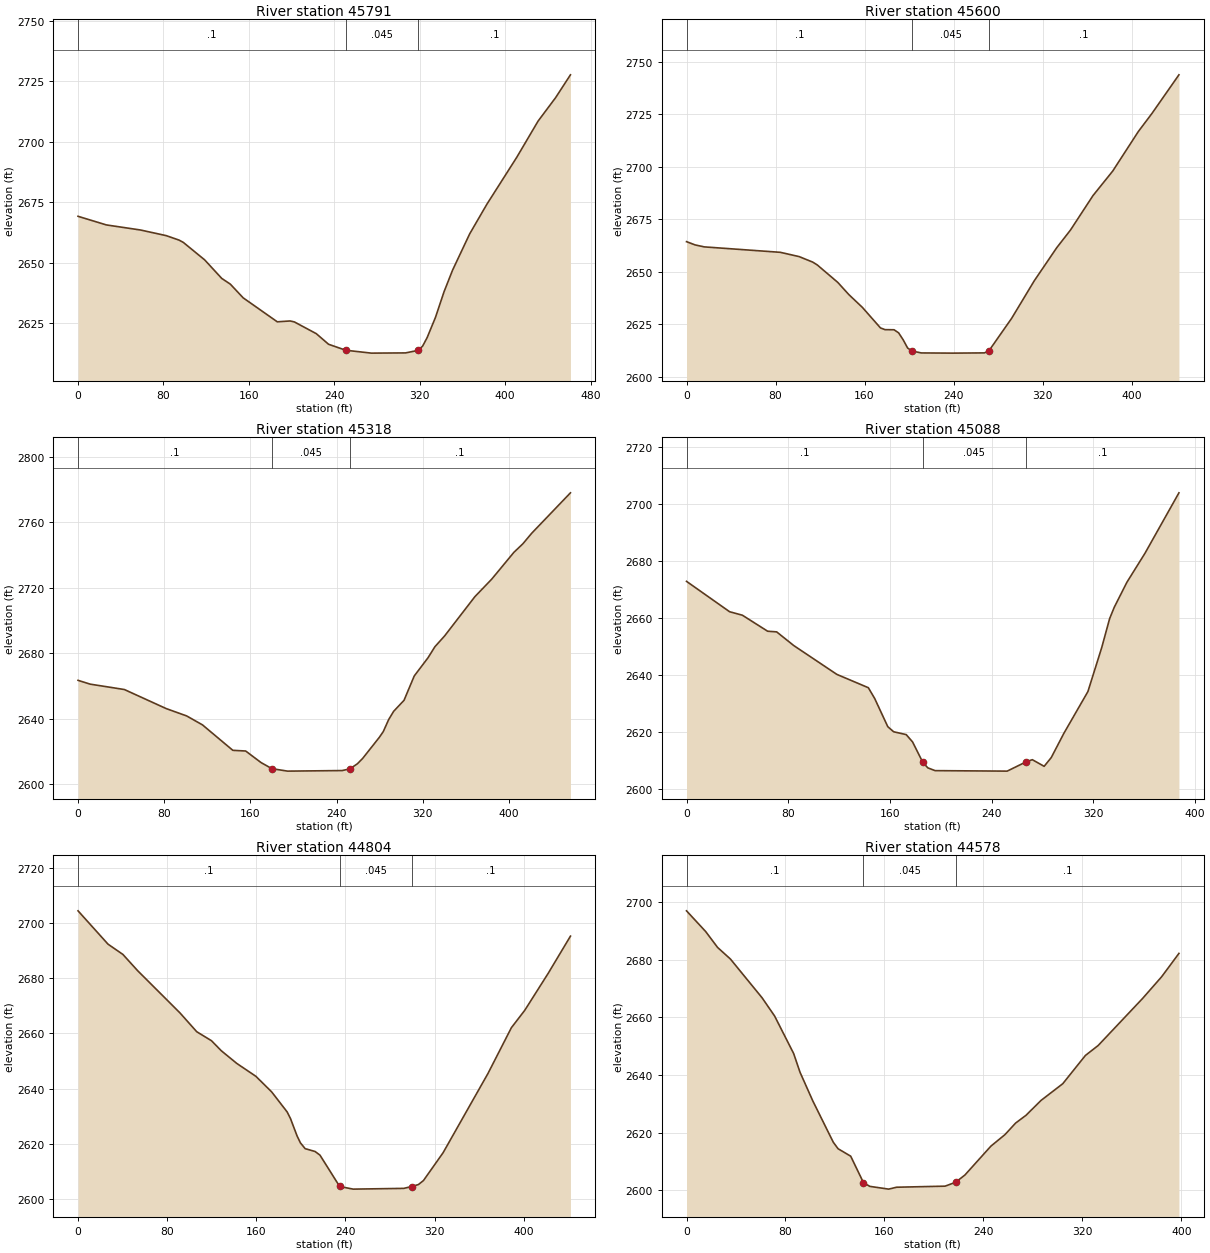
Type RM Length L Ch R = 1 ,45791   ,191,191,191
XS GIS Cut Line= 2
2371961.67290585700132.5468548632372422.51773027700116.302785841
#Sta/Elev= 30
       0 2669.15    26.5 2665.59    58.5 2663.49    82.6 2661.16    94.6 2659.32
    98.6 2658.36   118.6 2651.14   134.6 2643.48   142.6 2641.13   154.6 2635.48
   186.6 2625.56   198.6 2625.92   202.6 2625.51   223.1 2620.67   234.6 2616.29
   250.7 2613.82   274.7 2612.63   306.7 2612.72   318.8  2613.8   322.7 2615.56
   326.9 2619.04   334.7 2627.39   342.7 2637.94   350.7 2646.89   366.7 2661.86
   382.7 2674.03   410.8 2693.51   430.8 2708.48   447.2 2718.16   461.1 2727.59
#Mann= 3 ,-1,0
       0      .1       0   250.7    .045       0   318.8      .1       0
Bank Sta=250.7,318.8
XS Rating Curve= 0 ,0
Exp/Cntr=0.3,0.1

Type RM Length L Ch R = 1 ,45600   ,281.5,281.5,281.5
XS GIS Cut Line= 2
2371980.56035541700270.968335526 2372416.1711465700349.025760518
#Sta/Elev= 30
       0 2664.35     7.7  2662.8    15.9 2661.86    84.3 2659.27   101.2 2657.23
   113.4 2654.61   117.5 2653.26     136 2644.91   145.9 2639.12   158.1 2633.01
   174.3 2623.25   178.4 2622.43   186.5 2622.38   190.6 2620.91   194.7 2617.59
   198.7 2613.67   202.8 2612.27   210.9 2611.34   239.3 2611.25   267.8 2611.36
   271.9 2612.46   292.2 2627.85   312.5 2645.71   332.8 2661.55     345 2669.85
   365.3 2686.31     383 2697.98     406 2716.79   418.2 2725.38   442.5 2743.82
#Mann= 3 ,-1,0
       0      .1       0   202.8    .045       0   271.9      .1       0
Bank Sta=202.8,271.9
XS Rating Curve= 0 ,0
Exp/Cntr(USF)=0,0
Exp/Cntr=0.3,0.1

Type RM Length L Ch R = 1 ,45318   ,230.5,230.5,230.5
XS GIS Cut Line= 2
2371919.86605557  700449.86468462372301.03944177700702.115770618
#Sta/Elev= 30
       0 2663.51    11.3 2661.18      43  2657.9    81.9 2646.24   100.8 2641.78
   115.5 2636.31   143.7 2620.76   155.6 2620.35     170 2613.24     180 2609.56
   194.5 2608.06   245.1  2608.4   252.4 2609.45   259.4  2612.6   264.2 2615.81
   279.7 2628.71   283.4 2632.26   288.4 2639.62     293  2644.6   302.6  2651.3
   312.1 2666.18   324.9 2677.32   331.3 2684.06   340.3 2690.64   368.4 2714.62
   384.1 2725.37   404.6 2741.69   412.9 2746.88   421.1 2753.32   457.1 2778.03
#Mann= 3 ,-1,0
       0      .1       0     180    .045       0   252.4      .1       0
Bank Sta=180,252.4
XS Rating Curve= 0 ,0
Exp/Cntr=0.3,0.1

Type RM Length L Ch R = 1 ,45088   ,283.6,283.6,283.6
XS GIS Cut Line= 2
2371794.22972801700537.8743693712372023.36604009 700850.10406934
#Sta/Elev= 30
       0 2672.76    33.9 2662.11    43.9  2660.9    63.8 2655.28    70.9 2655.05
    84.4 2650.24   118.2 2640.16     143 2635.48     148 2631.71   158.3 2621.83
   162.9 2620.04   172.8 2619.04   177.8 2616.47   185.8 2609.36   189.8 2607.39
   195.5 2606.41   252.2 2606.24     267 2609.47     267 2609.48     272 2610.25
   281.3 2607.92   286.9 2611.01   296.8 2619.49   315.7 2634.12   326.6 2649.59
   332.8 2659.71   336.5 2663.74   346.4 2672.46   360.6 2682.61   387.3 2703.79
#Mann= 3 ,-1,0
       0      .1       0   185.8    .045       0     267      .1       0
Bank Sta=185.8,267
XS Rating Curve= 0 ,0
Exp/Cntr(USF)=0,0
Exp/Cntr=0.3,0.1

Type RM Length L Ch R = 1 ,44804   ,226.4,226.4,226.4
XS GIS Cut Line= 2
2371570.84988885700620.847114691 2371759.3809292701020.554672923
#Sta/Elev= 30
       0 2704.43    26.9 2692.35    40.3 2688.61    53.4 2682.77    91.4 2667.46
   106.5 2660.61   119.8 2657.33   128.6 2653.69   142.5  2649.1   159.6 2644.44
   173.7 2638.82   187.6 2631.56   190.6 2629.18   196.6 2622.79   199.6  2620.3
   203.8 2618.22   212.7 2617.19   217.1 2615.87   234.8  2604.5   246.9 2603.54
   292.3 2603.81   299.3 2604.47   305.5  2605.2     310 2606.66   327.6 2616.73
   367.9 2645.48   388.9 2662.06   400.9 2668.37     422 2681.82   441.9 2695.25
#Mann= 3 ,-1,0
       0      .1       0   234.8    .045       0   299.3      .1       0
Bank Sta=234.8,299.3
XS Rating Curve= 0 ,0
Exp/Cntr=0.3,0.1

Type RM Length L Ch R = 1 ,44578   ,267.6,267.6,267.6
XS GIS Cut Line= 2
2371357.96352574700801.6258584512371606.96391371 701112.17690412
#Sta/Elev= 30
       0 2697.03    15.5 2689.83    25.1 2684.33    35.5 2680.29    61.1 2666.83
    71.2 2660.52    86.6 2647.49    91.7 2641.04     102 2631.11   118.6 2616.72
   122.5 2614.44   132.7 2611.86     143 2602.69   148.1 2601.38   163.4 2600.42
   169.8 2601.08     209 2601.45   217.5  2602.8     225 2605.31     246 2615.33
   257.3 2619.31     266 2623.35   274.4 2626.05   286.5  2631.2   304.1 2637.01
   322.4 2646.82   332.7 2650.27   368.6  2666.6     384 2674.13     398 2682.25
#Mann= 3 ,-1,0
       0      .1       0     143    .045       0   217.5      .1       0
Bank Sta=143,217.5
XS Rating Curve= 0 ,0
Exp/Cntr(USF)=0,0
Exp/Cntr=0.3,0.1

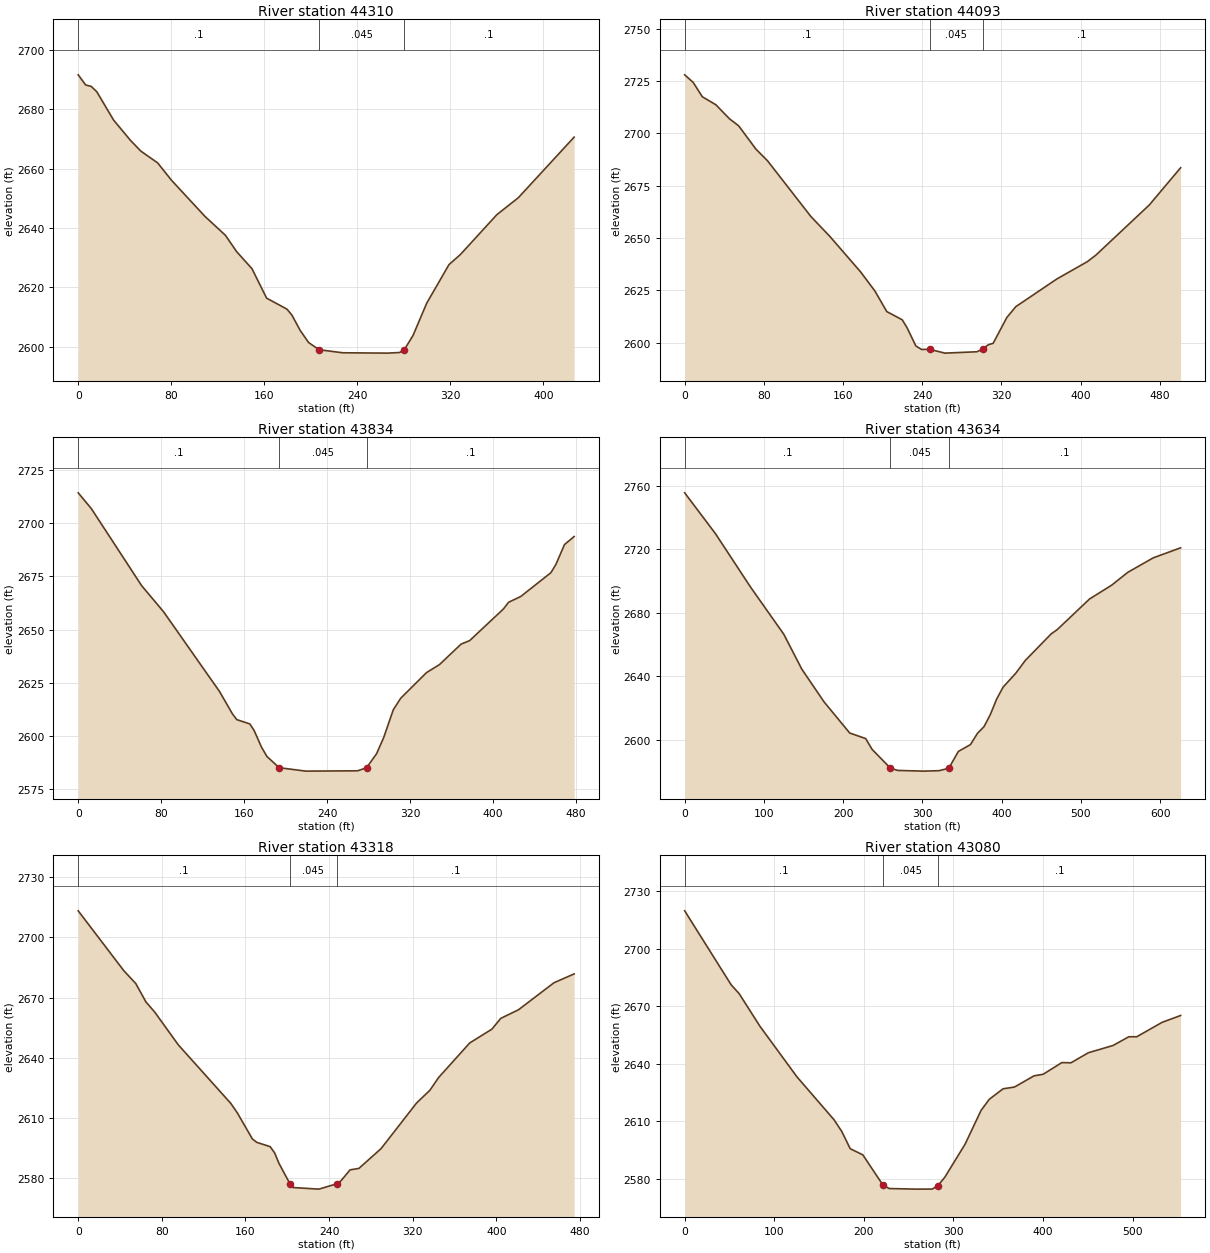
Type RM Length L Ch R = 1 ,44310   ,216.9,216.9,216.9
XS GIS Cut Line= 2
2371114.85805312701027.3206190092371469.67094792701263.791039843
#Sta/Elev= 30
       0 2691.58     6.4 2688.17    11.2 2687.68      16 2685.87    30.4 2676.36
    44.8 2669.58    53.8 2665.91    68.3 2661.93    80.2 2656.08     109 2643.91
   126.6 2637.54   136.2 2632.06   149.4  2626.3     162 2616.39   179.4 2612.71
   183.7 2610.71   190.9  2605.5   198.1 2601.44   207.1 2599.03   227.3    2598
     266 2597.88   276.3 2598.09   280.4 2599.06   287.9 2603.85   299.6 2614.66
   318.8 2627.69   328.5 2631.04     360 2644.52   378.4  2650.2   426.4 2670.61
#Mann= 3 ,-1,0
       0      .1       0   207.1    .045       0   280.4      .1       0
Bank Sta=207.1,280.4
XS Rating Curve= 0 ,0
Exp/Cntr=0.3,0.1

Type RM Length L Ch R = 1 ,44093   ,258.9,258.9,258.9
XS GIS Cut Line= 2
2370932.70443618701190.5141048292371369.15455442701436.716735629
#Sta/Elev= 30
       0 2728.01     8.6 2724.38    17.8 2717.54    31.5 2713.71    45.3 2706.98
    54.5 2703.67      72  2692.5    83.8 2686.88   127.5 2660.31   146.4 2650.94
   177.7 2633.86   192.3 2624.63   204.2 2614.86   219.8 2610.94   224.7 2607.15
   233.6 2598.42   239.4 2596.74   247.4 2596.84   262.9    2595   295.2 2595.65
   301.1 2596.92   306.7 2598.99   311.7 2599.71   325.5 2612.02   334.6 2617.21
     376 2630.43   406.8  2638.7   415.6 2641.89   469.5 2665.83   501.1  2683.6
#Mann= 3 ,-1,0
       0      .1       0   247.4    .045       0   301.1      .1       0
Bank Sta=247.4,301.1
XS Rating Curve= 0 ,0
Exp/Cntr(USF)=0,0
Exp/Cntr=0.3,0.1

Type RM Length L Ch R = 1 ,43834   ,200.5,200.5,200.5
XS GIS Cut Line= 2
 2370841.0454862 701492.634749742371301.03860469701623.892973438
#Sta/Elev= 30
       0 2714.31    12.7 2706.86    61.2 2670.66    82.3 2658.43   136.4 2620.87
   148.8 2610.38     153  2607.7   165.5  2605.7   169.6 2602.69   176.9 2594.69
   182.1 2590.35   193.9 2585.11   219.6  2583.5   269.5 2583.65   278.1 2585.07
   287.8 2591.67   294.8 2599.43   303.9  2612.3   311.1 2617.76     336 2629.82
   348.5 2633.58   369.3 2643.19   377.6 2644.85   410.2 2659.72   415.1 2662.85
   426.9 2665.59     456 2676.79   460.8 2680.66   469.1    2690   478.4 2693.77
#Mann= 3 ,-1,0
       0      .1       0   193.9    .045       0   278.1      .1       0
Bank Sta=193.9,278.1
XS Rating Curve= 0 ,0
Exp/Cntr=0.3,0.1

Type RM Length L Ch R = 1 ,43634   ,315.7,315.7,315.7
XS GIS Cut Line= 2
2370733.64742382701711.5497550322371354.32887318701792.096202659
#Sta/Elev= 30
       0 2755.57    38.9 2729.84    83.2  2696.2   125.1 2666.57   147.8 2644.63
     176 2623.96   208.3 2604.42   228.4 2600.94   236.5 2594.15   259.62582.354
   268.8 2580.88     301 2580.44   320.9 2580.71   333.3 2582.23   345.4 2592.83
   360.7 2597.15   369.6 2604.29   377.7 2608.36   385.7 2615.99   393.8 2625.86
   401.9 2633.31   417.9 2642.07   430.1 2650.21   462.4 2666.74   470.4 2669.59
   510.9 2688.74     539  2697.5   559.2 2705.53   591.4 2714.67   625.9 2720.96
#Mann= 3 ,-1,0
       0      .1       0   259.6    .045       0   333.3      .1       0
Bank Sta=259.6,333.3
XS Rating Curve= 0 ,0
Exp/Cntr(USF)=0,0
Exp/Cntr=0.3,0.1

Type RM Length L Ch R = 1 ,43318   ,237.7,237.7,237.7
XS GIS Cut Line= 2
2370855.06394088702134.3809292052371302.30924106701976.240172037
#Sta/Elev= 30
       0 2713.27    43.6 2683.44    55.1 2676.99    64.8 2667.84    73.3 2662.71
    95.8 2646.41     146 2617.23   152.3 2612.45   166.6 2599.52   170.9 2597.81
   183.6 2595.69   187.9 2592.57   192.1 2587.31   202.4  2577.3   205.5 2575.29
   230.3  2574.5   247.3 2577.16   251.5 2578.72     260  2584.1   268.5 2584.83
   289.7 2594.69   323.6 2617.41   336.4 2623.79   344.8 2630.18   374.5 2647.38
   395.7 2654.26   404.2 2659.64   421.2 2663.95   455.1 2677.41   474.4 2681.82
#Mann= 3 ,-1,0
       0      .1       0   202.4    .045       0   247.3      .1       0
Bank Sta=202.4,247.3
XS Rating Curve= 0 ,0
Exp/Cntr=0.3,0.1

Type RM Length L Ch R = 1 ,43080   ,259.5,259.5,259.5
XS GIS Cut Line= 2
2370946.85860871702398.5635730252371430.13729448702128.496072159
#Sta/Elev= 30
       0 2719.89    51.9 2681.26    60.8 2676.66      84 2659.62   125.4 2633.16
   166.8 2610.75   175.4 2604.65   184.8 2595.68   198.9 2592.46   221.5 2576.57
   228.3 2574.88   258.1 2574.57   276.4  2574.6   282.72576.431   290.2 2580.66
   313.1 2598.11   330.8 2615.64     340 2621.46   355.4 2626.96   368.1 2627.87
     390 2633.72   400.2 2634.55     421 2640.64   431.2 2640.53   450.6 2645.78
   478.1 2649.56   495.8 2654.13   504.6 2654.13     533 2661.67   553.6 2665.23
#Mann= 3 ,-1,0
       0      .1       0   221.5    .045       0   282.7      .1       0
Bank Sta=221.5,282.7
XS Rating Curve= 0 ,0
Exp/Cntr(USF)=0,0
Exp/Cntr=0.3,0.1

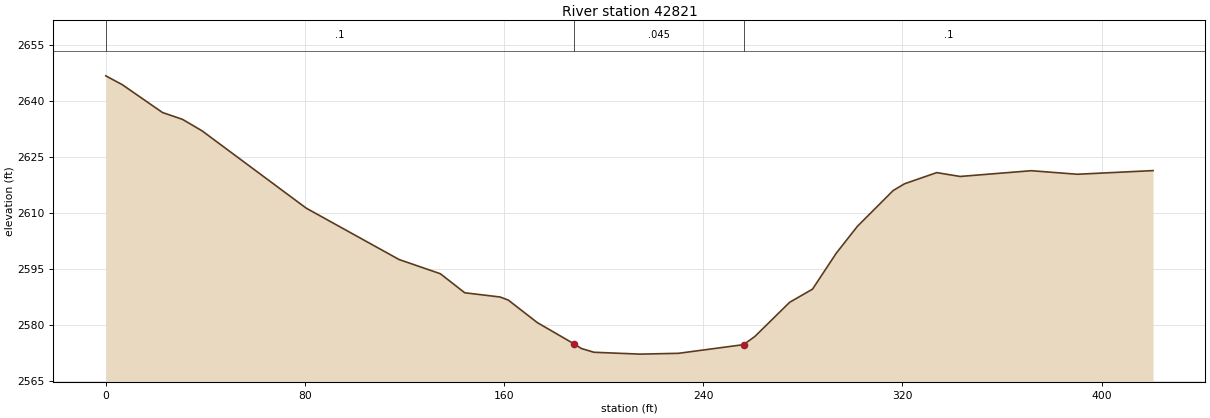
Type RM Length L Ch R = 1 ,42821   ,247.9,247.9,247.9
XS GIS Cut Line= 2
  2371146.561859702584.6037606672371510.55366824702373.569713273
#Sta/Elev= 30
       0 2646.78     6.6 2644.42    22.8 2636.95    30.8 2635.13    38.7 2632.04
    80.5 2611.35   117.8 2597.59   134.4 2593.78   144.2 2588.68   158.4 2587.55
   161.7 2586.72   173.4 2580.67   188.1    2575     191 2573.77   196.1 2572.75
   214.6 2572.25   230.1 2572.47   256.2 2574.79   260.8 2577.01   274.7 2586.12
   283.9 2589.65   293.4 2599.24   301.9 2606.45   316.3 2616.06   320.9 2617.88
   333.8 2620.86   343.2 2619.83   371.8 2621.37   390.3 2620.42   420.7  2621.4
#Mann= 3 ,-1,0
       0      .1       0   188.1    .045       0   256.2      .1       0
Bank Sta=188.1,256.2
XS Rating Curve= 0 ,0
Exp/Cntr=0.3,0.1