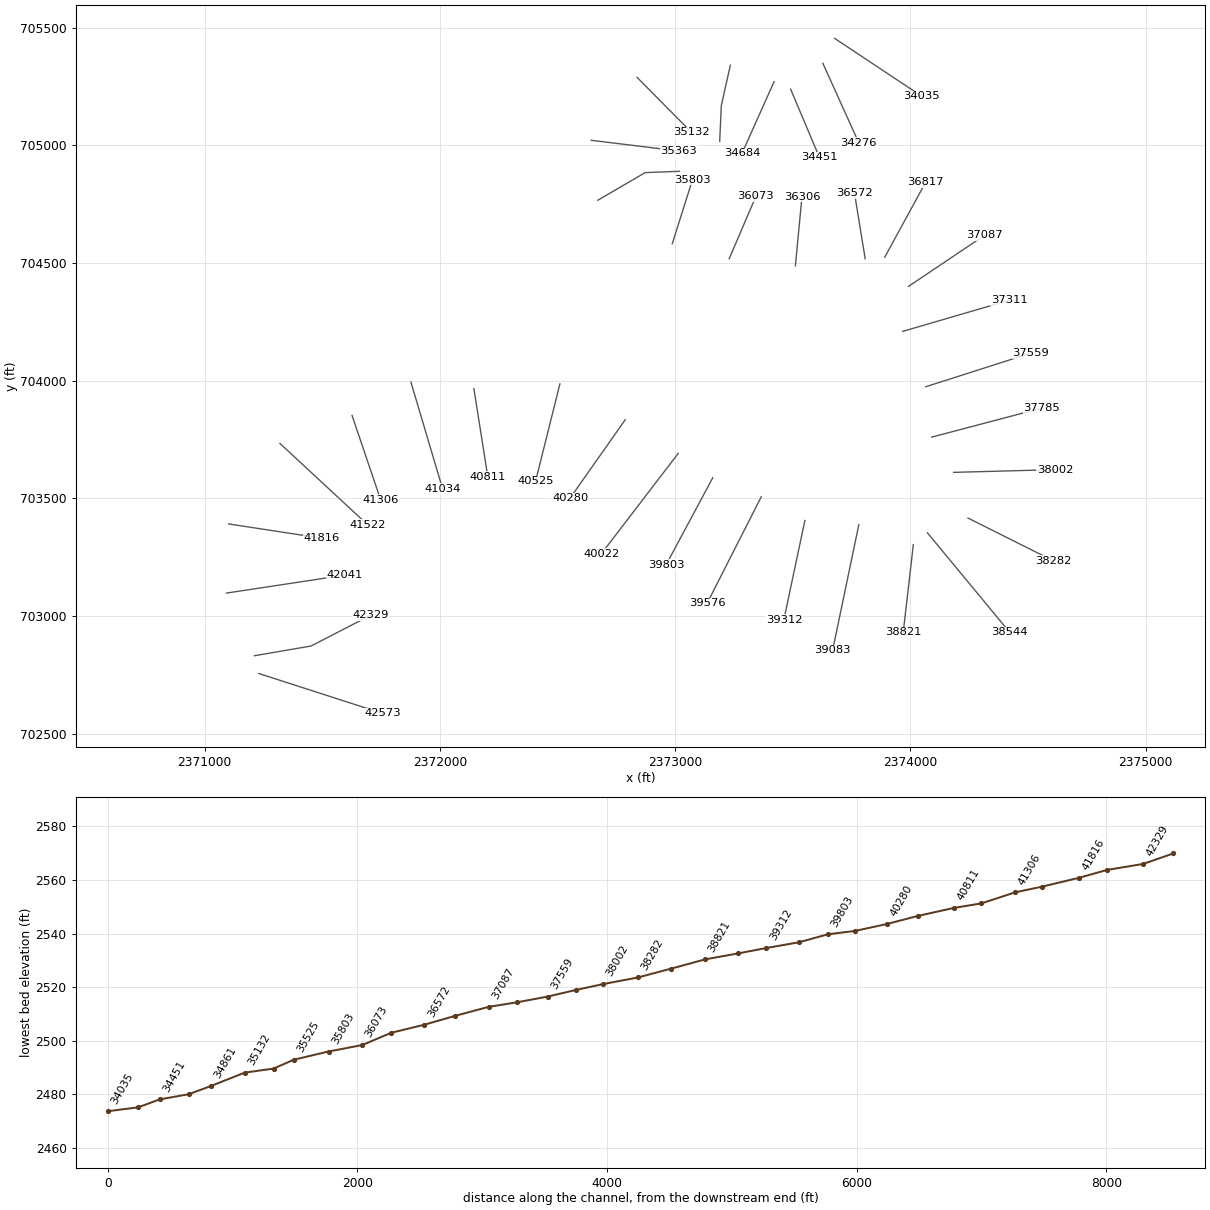
HEC-RAS study LAURELFK.prj: LAURELFK

--- LAURELFK.g01 (geometry) --- (continued)

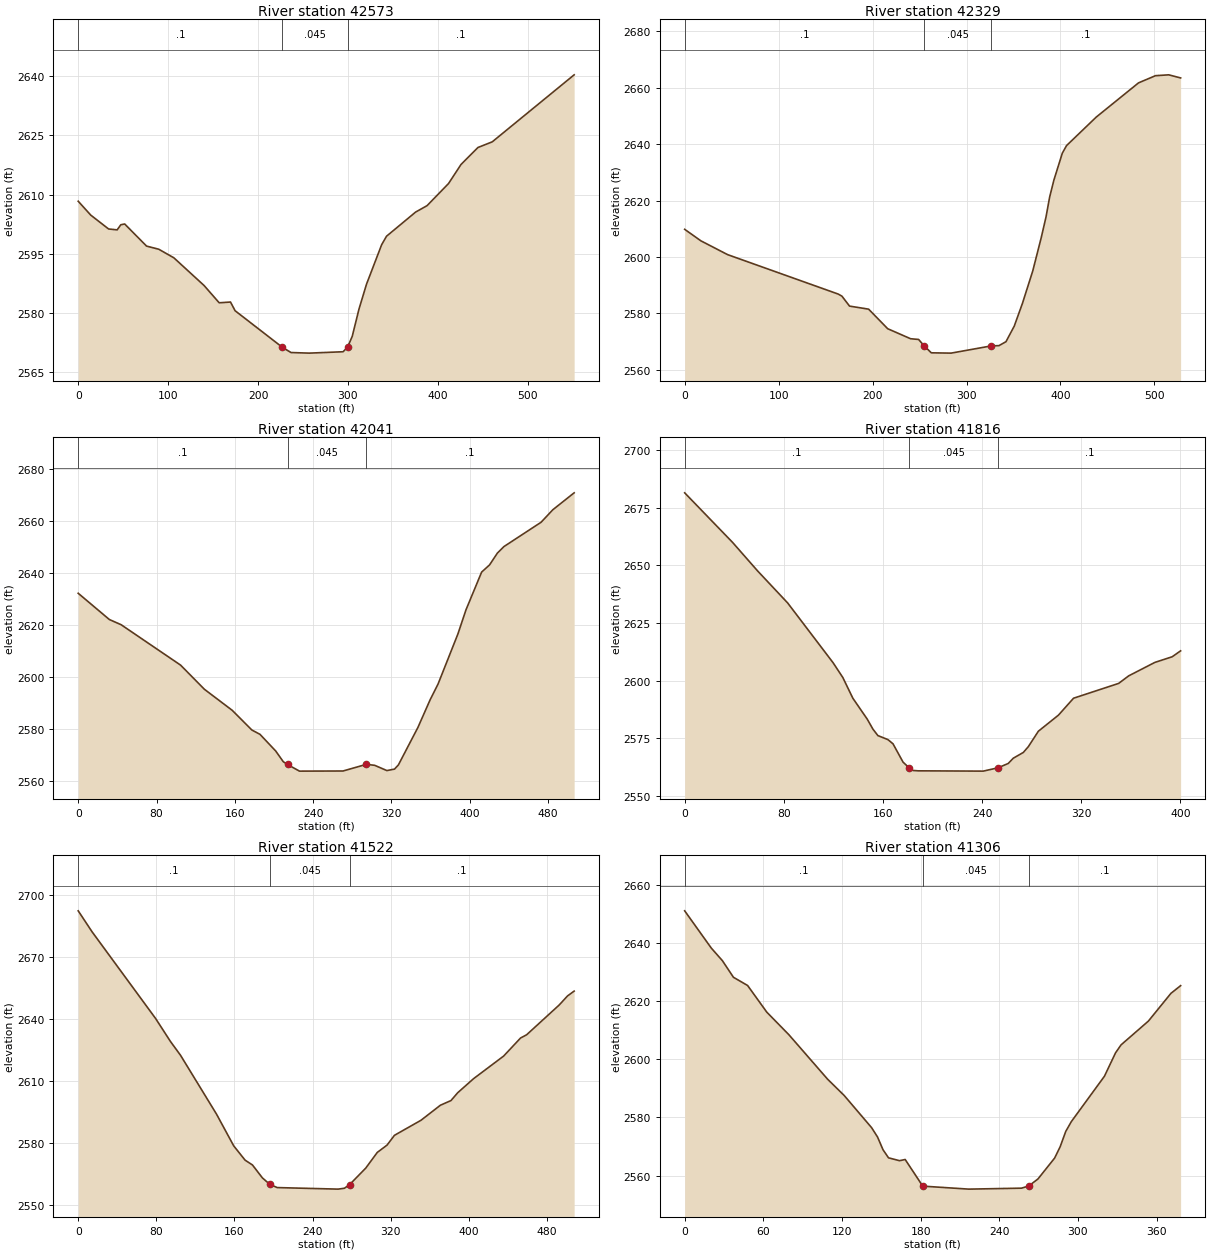
Type RM Length L Ch R = 1 ,42573   ,244.4,244.4,244.4
XS GIS Cut Line= 2
2371230.93171541 702755.55490496 2371755.9429371 702586.30786639
#Sta/Elev= 30
       0 2608.33    13.9 2604.83    33.8 2601.31    43.3 2601.08    47.4 2602.38
    51.7 2602.57      76 2596.98    89.6 2596.18   106.4 2594.01     140    2587
   156.8 2582.63   169.4 2582.82   174.5 2580.62   227.2 2571.34   236.7 2570.04
   257.1 2569.89   294.6 2570.24   299.7 2571.43   304.8 2574.15   312.3 2581.05
   320.6  2587.3   337.5 2597.33   342.9 2599.47   375.3 2605.59     388 2607.21
   411.9 2612.81   425.8 2617.64   444.6 2621.93   460.5 2623.36   551.6 2640.32
#Mann= 3 ,-1,0
       0      .1       0   227.2    .045       0   299.7      .1       0
Bank Sta=227.2,299.7
XS Rating Curve= 0 ,0
Exp/Cntr(USF)=0,0
Exp/Cntr=0.3,0.1

Type RM Length L Ch R = 1 ,42329   ,287.2,287.2,287.2
XS GIS Cut Line= 3
2371211.16269724702831.1827168562371452.32425041  702872.5420671
2371704.01866938703002.395250407
#Sta/Elev= 30
       0 2609.81    17.3 2605.72    45.7 2600.84   163.4 2586.87   167.4 2586.12
   175.5  2582.6   195.8 2581.52   216.1 2574.59   240.5 2571.04     249 2570.78
   254.8 2568.57   262.5 2566.05   283.6 2565.94   326.5 2568.51   334.5 2568.59
     342 2569.99   350.8  2575.5   359.5 2583.54   370.5 2595.05   379.5 2606.81
   384.6 2614.15   388.5 2621.25     393 2627.24     402 2636.81   406.5 2639.48
   438.1 2649.58   483.1  2661.7   501.1 2664.24   515.2 2664.55   527.9 2663.45
#Mann= 3 ,-1,0
       0      .1       0   254.8    .045       0   326.5      .1       0
Bank Sta=254.8,326.5
XS Rating Curve= 0 ,0
Exp/Cntr=0.3,0.1

Type RM Length L Ch R = 1 ,42041   ,225.5,225.5,225.5
XS GIS Cut Line= 2
 2371092.7708676703097.5030032932371593.60394092703173.491469589
#Sta/Elev= 30
       0 2632.09    31.8 2622.01    43.9 2619.99   104.6 2604.47   128.9 2595.19
   157.3 2587.11   177.4 2579.53   185.7 2577.87   201.7 2571.48   209.5 2567.34
   213.8 2566.28     226 2563.73   270.5 2563.78   294.3 2566.33   302.8 2565.97
   315.3 2563.94   323.1 2564.51   327.1 2566.14     347 2580.51   359.5 2591.16
   367.6 2597.23   387.8 2616.39   396.1 2625.72   412.1 2640.24   420.2    2643
   428.2 2647.54   434.8 2650.02   472.8 2659.38   484.9 2664.22   506.6  2670.7
#Mann= 3 ,-1,0
       0      .1       0   213.8    .045       0   294.3      .1       0
Bank Sta=213.8,294.3
XS Rating Curve= 0 ,0
Exp/Cntr(USF)=0,0
Exp/Cntr=0.3,0.1

Type RM Length L Ch R = 1 ,41816   ,293.9,293.9,293.9
XS GIS Cut Line= 2
2371102.03076434703391.4556841192371497.61929789703330.914433713
#Sta/Elev= 30
       0 2681.48    38.6 2660.01    58.8 2647.64    83.1 2633.72   119.7 2607.84
   127.6  2601.4   135.7 2592.41   147.3 2583.35   151.9    2579   155.9  2576.2
     164 2574.45   168.1 2572.64   176.2  2564.7   181.4 2562.07   184.3 2561.06
   188.3 2560.91   240.9 2560.78     253 2562.24   261.1 2564.11   265.2 2566.39
   273.3 2568.89   277.3 2571.38   285.4 2578.08   301.6 2585.05   313.8  2592.4
   350.2 2598.83   358.3  2602.1   379.4 2607.93   393.4 2610.38   400.2 2612.95
#Mann= 3 ,-1,0
       0      .1       0   181.4    .045       0     253      .1       0
Bank Sta=181.4,253
XS Rating Curve= 0 ,0
Exp/Cntr=0.3,0.1

Type RM Length L Ch R = 1 ,41522   ,216,216,216
XS GIS Cut Line= 2
2371320.35552806703733.4377972482371692.62225688703388.035677719
#Sta/Elev= 30
       0 2692.39    14.2 2682.22    79.3 2640.17    94.5 2629.04   104.8 2622.35
   141.6 2593.86   159.2 2578.49   170.9 2571.53   178.4 2569.22   188.6 2562.95
   196.2  2559.8   203.8 2558.25   266.1  2557.5   272.6 2557.93     278 2559.74
   294.4 2567.68   306.2 2575.28   316.2 2578.83   323.8 2583.58     351 2590.88
   370.8 2598.15   381.7 2600.43   388.5 2604.19   404.8 2611.03   435.6 2621.99
   452.9 2630.73   459.1  2632.3   492.5 2646.75     501 2651.13   507.8 2653.48
#Mann= 3 ,-1,0
       0      .1       0   196.2    .045       0     278      .1       0
Bank Sta=196.2,278
XS Rating Curve= 0 ,0
Exp/Cntr(USF)=0,0
Exp/Cntr=0.3,0.1

Type RM Length L Ch R = 1 ,41306   ,272.4,272.4,272.4
XS GIS Cut Line= 2
2371626.58814242 703852.443953782371748.09061731703494.151954015
#Sta/Elev= 30
       0 2650.99    20.3 2638.19    28.8 2633.85    37.2 2628.16      48 2625.34
    62.6  2616.2    79.5 2608.42     109 2593.16   121.7 2587.54   142.6 2576.49
   147.1  2573.3   151.3 2568.91   155.5 2566.13   163.9 2565.15   168.2 2565.56
   181.6 2556.41   216.7 2555.38   256.9 2555.71   262.5 2556.47   269.5 2558.88
   282.2 2566.05   286.4 2569.93   290.7 2575.22   294.9 2578.55   320.2 2594.17
   328.7 2602.23   332.9 2604.95   353.7  2613.1   370.9 2622.63   378.3 2625.28
#Mann= 3 ,-1,0
       0      .1       0   181.6    .045       0   262.5      .1       0
Bank Sta=181.6,262.5
XS Rating Curve= 0 ,0
Exp/Cntr=0.3,0.1

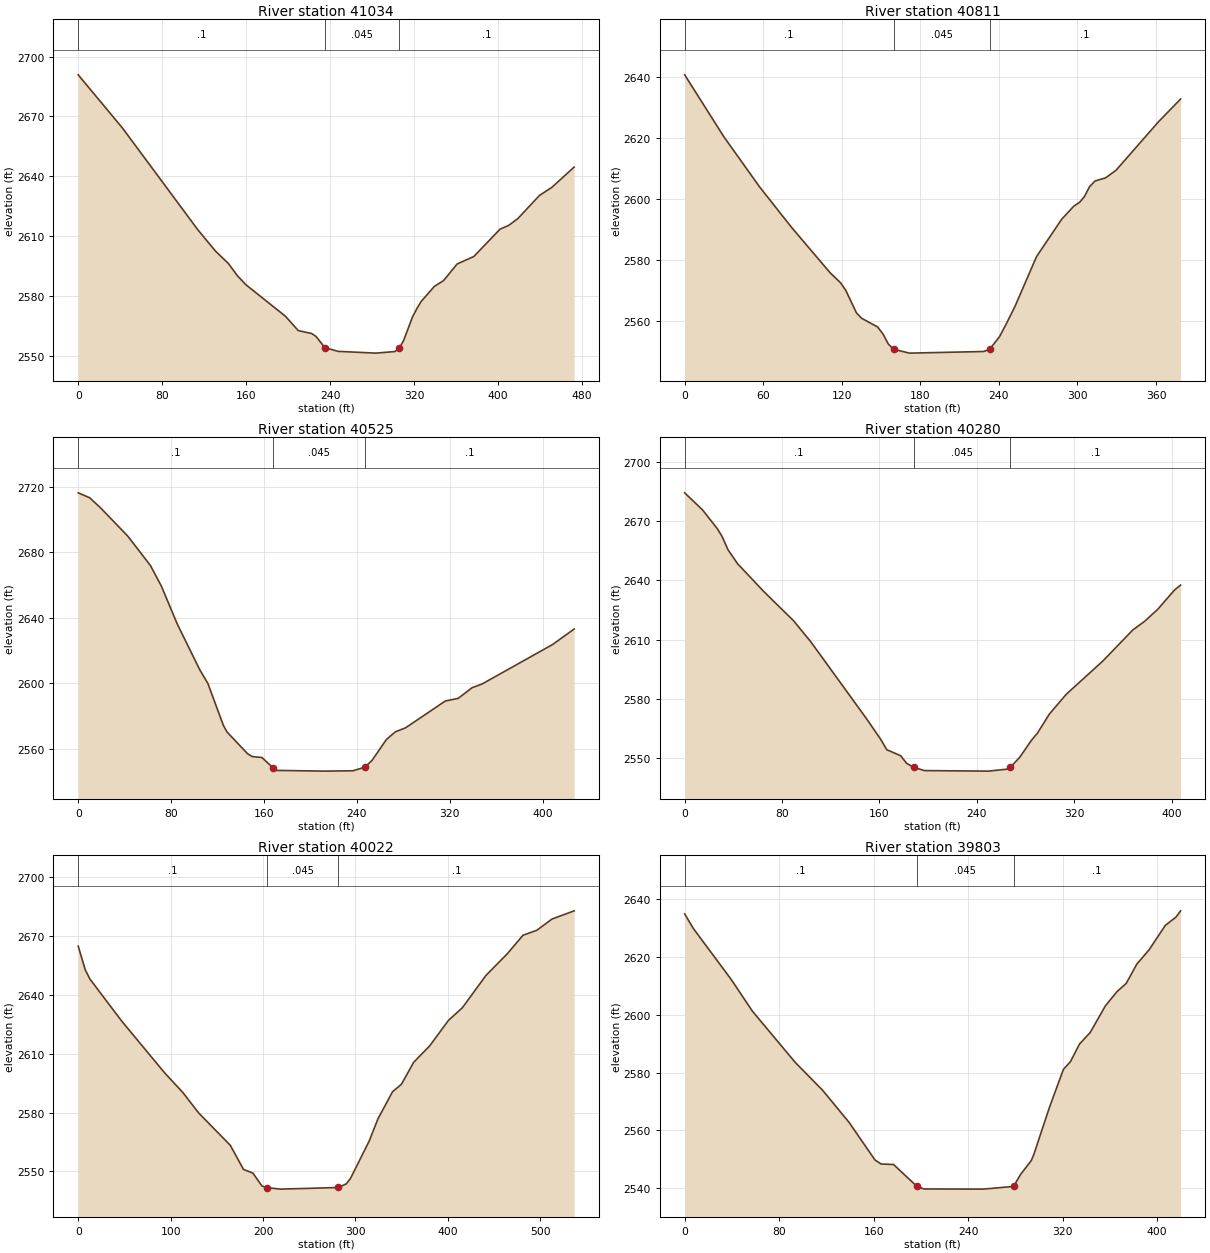
Type RM Length L Ch R = 1 ,41034   ,222.7,222.7,222.7
XS GIS Cut Line= 2
2371876.83672063703994.4082875582372011.15976711703541.547730843
#Sta/Elev= 30
       0 2690.84    42.3 2664.05   113.9 2613.15   130.6 2602.51   143.1 2596.17
   151.7 2590.02   159.8 2585.52   197.4 2569.73   209.6 2562.54   222.5 2561.05
   226.6 2559.54   234.9 2554.02   247.4 2552.12   283.6 2551.23   301.7 2552.02
   305.9 2553.81     310  2557.6   318.4 2569.37   322.5 2573.48   326.7 2577.16
   339.2 2584.69     348  2587.6   360.9 2595.94   376.8 2599.69   401.8  2613.4
   410.2 2615.36   418.8 2618.73   439.4 2630.36     451 2634.31   472.4 2644.57
#Mann= 3 ,-1,0
       0      .1       0   234.9    .045       0   305.9      .1       0
Bank Sta=234.9,305.9
XS Rating Curve= 0 ,0
Exp/Cntr(USF)=0,0
Exp/Cntr=0.3,0.1

Type RM Length L Ch R = 1 ,40811   ,286.3,286.3,286.3
XS GIS Cut Line= 2
2372144.35809503703966.7268108892372203.48480924703592.554001881
#Sta/Elev= 30
       0 2640.78    29.9  2620.5    57.1  2604.1    81.6 2590.78   110.9 2575.96
     119 2572.62   123.1 2570.07   131.2 2562.71   135.2 2560.95   147.4 2558.09
   151.6  2555.7   155.5 2552.53   159.5 2550.81   171.7 2549.52   228.3 2550.05
   232.9 2550.77   240.5 2554.93     246 2559.42   252.2 2564.76   268.8  2581.2
   287.9 2593.39   297.2 2597.71   301.9 2599.07   305.3 2600.84   309.3 2604.11
   313.4 2605.97   321.5 2606.99   329.6 2609.54     362 2625.43   378.8 2632.86
#Mann= 3 ,-1,0
       0      .1       0   159.5    .045       0   232.9      .1       0
Bank Sta=159.5,232.9
XS Rating Curve= 0 ,0
Exp/Cntr=0.3,0.1

Type RM Length L Ch R = 1 ,40525   ,244.8,244.8,244.8
XS GIS Cut Line= 2
2372510.07393977703986.7326849022372406.45330391703572.250141468
#Sta/Elev= 30
       0  2716.2     9.8 2713.23    19.3 2707.01    42.8 2689.72    62.2 2671.91
    71.7 2659.24    85.3 2636.27   104.7 2608.33   111.7    2600   124.9 2574.69
   128.2  2570.4   145.9 2557.15     150 2555.42   158.3 2554.83   167.8 2548.57
   170.6    2547   211.9 2546.55   236.6 2546.76   246.9 2548.94   246.9 2548.95
   253.1 2553.09   265.5 2565.86   273.3 2570.55     282 2572.95   316.2 2589.28
   327.3  2590.9   339.3  2597.4   347.9 2599.67   408.6 2623.72   427.2 2633.18
#Mann= 3 ,-1,0
       0      .1       0   167.8    .045       0   246.9      .1       0
Bank Sta=167.8,246.9
XS Rating Curve= 0 ,0
Exp/Cntr(USF)=0,0
Exp/Cntr=0.3,0.1

Type RM Length L Ch R = 1 ,40280   ,258,258,258
XS GIS Cut Line= 2
2372787.66625451703834.3027992912372553.29298502 703501.07287477
#Sta/Elev= 30
       0 2684.23    14.8 2675.52    26.9 2666.02    30.7 2662.23    35.6 2655.45
    43.5 2648.37    64.9  2634.4    89.4 2619.61   103.8 2608.79   149.7 2569.79
   161.2 2559.48     166  2554.4   177.4 2551.36   182.3 2547.53   188.1 2545.51
     197 2543.84   249.4 2543.57   264.6 2544.55   267.4 2545.44   275.2 2550.54
     285 2559.27   289.9 2562.87   299.7 2572.49   313.4 2582.38   343.7 2599.33
   368.1  2614.9   377.9 2619.33   388.5 2625.27   402.4 2635.13   407.4  2637.6
#Mann= 3 ,-1,0
       0      .1       0   188.1    .045       0   267.4      .1       0
Bank Sta=188.1,267.4
XS Rating Curve= 0 ,0
Exp/Cntr=0.3,0.1

Type RM Length L Ch R = 1 ,40022   ,219.1,219.1,219.1
XS GIS Cut Line= 2
2373012.82591375703691.2219826392372686.61280086 703265.22603522
#Sta/Elev= 30
       0 2664.78     7.6 2652.75    12.6 2648.06    47.1 2626.57    93.2 2600.38
   113.4 2590.09   130.3 2579.78   164.6 2563.28   178.8 2551.02     189 2549.13
   198.8 2542.59   204.1 2541.71   219.2 2540.96   281.5 2541.79   290.1 2543.66
   294.8 2546.57   314.9 2565.53   324.3 2576.77   340.1 2590.58   349.8 2594.43
   362.9 2605.56   380.4 2614.01   400.6 2626.95   415.6 2633.36   441.3 2649.92
   464.1  2660.8   481.3 2670.34   496.3 2672.88   512.6 2678.57   536.6 2682.77
#Mann= 3 ,-1,0
       0      .1       0   204.1    .045       0   281.5      .1       0
Bank Sta=204.1,281.5
XS Rating Curve= 0 ,0
Exp/Cntr(USF)=0,0
Exp/Cntr=0.3,0.1

Type RM Length L Ch R = 1 ,39803   ,227,227,227
XS GIS Cut Line= 2
2373159.65188444703587.7780100992372961.40616881703217.719340925
#Sta/Elev= 30
       0 2634.88     7.4 2629.81    39.3 2612.26    57.4 2601.21    93.7 2583.47
   116.8 2573.87   139.1 2562.81   161.1 2549.77   166.3 2548.38   176.8 2548.21
   196.6 2540.64   202.5 2539.75   252.5 2539.69   278.4 2540.62   284.3 2544.76
   293.4 2549.59   295.4  2551.5   308.8    2568   320.6 2581.12   326.6 2583.82
   334.2 2589.88   343.3 2593.88   356.1 2603.07     366 2608.03   373.8 2610.86
   382.7 2617.51   393.2  2622.5   406.8 2630.89   415.9  2633.8   419.8 2635.95
#Mann= 3 ,-1,0
       0      .1       0   196.6    .045       0   278.4      .1       0
Bank Sta=196.6,278.4
XS Rating Curve= 0 ,0
Exp/Cntr(USF)=0,0
Exp/Cntr=0.3,0.1

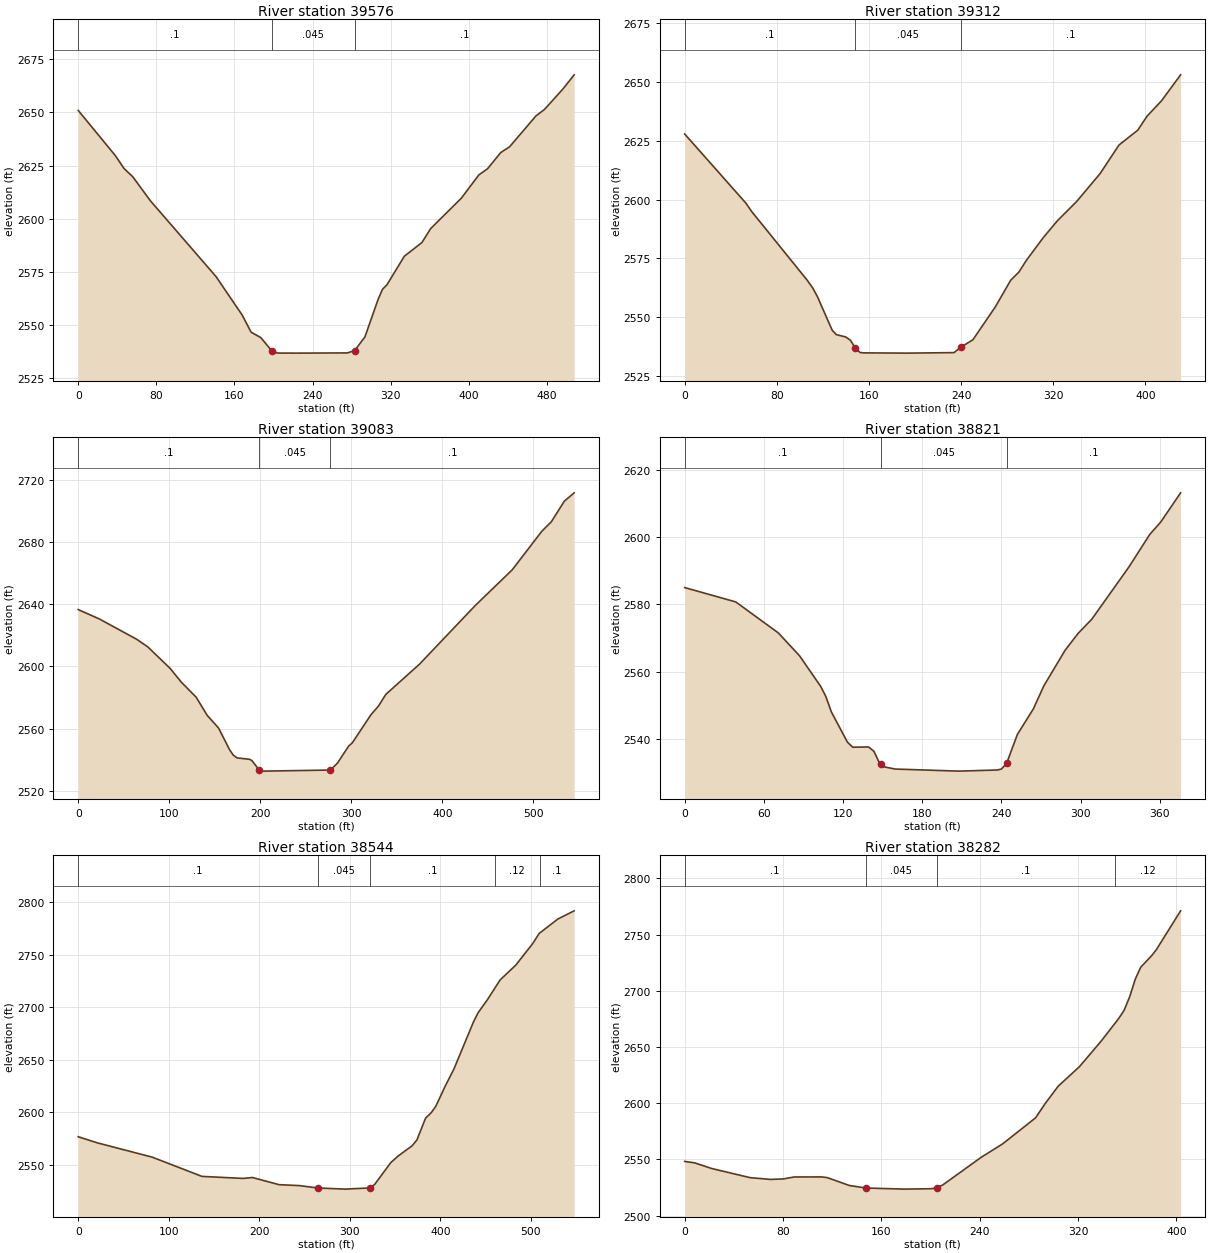
Type RM Length L Ch R = 1 ,39576   ,263.7,263.7,263.7
XS GIS Cut Line= 2
2373365.90363593 703507.007518892373135.63555625703054.146962175
#Sta/Elev= 30
       0 2650.94      38  2629.7    46.9 2623.64    55.9 2619.72    73.8  2608.5
   141.2 2572.75   168.1 2554.56   177.1  2546.6   187.1 2544.04     198 2537.98
     204 2536.79   222.8 2536.75   275.8 2536.85   283.2 2537.98   293.7 2544.38
   307.2 2562.04   311.7 2566.78   316.2 2568.89   334.1 2582.35   352.1 2588.79
     361 2595.33   392.5 2609.68   410.4  2620.6   419.4 2623.54   432.8 2631.11
   441.8 2633.79   468.7 2648.27   477.7 2651.44   496.5 2661.02     508 2667.68
#Mann= 3 ,-1,0
       0      .1       0     198    .045       0   283.2      .1       0
Bank Sta=198,283.2
XS Rating Curve= 0 ,0
Exp/Cntr(USF)=0,0
Exp/Cntr=0.3,0.1

Type RM Length L Ch R = 1 ,39312   ,228.8,228.8,228.8
XS GIS Cut Line= 2
2373551.18717281703406.0527707722373461.97660077702984.780625061
#Sta/Elev= 30
       0 2627.93    53.2 2598.46    58.1 2594.95   106.2 2565.77   111.3 2562.24
   115.4 2558.49   128.1 2544.33   131.7 2542.47   139.9 2541.47     144 2540.03
   148.1 2536.76   152.2 2534.88   155.1  2534.7   193.1 2534.59   233.9 2534.81
   239.5 2537.01   250.3  2540.3   269.8 2554.35     283 2565.59   290.1 2569.06
   296.8 2574.19   311.6 2583.95   323.8 2591.08   340.3 2599.15   360.7 2611.07
   377.1 2623.24   393.4 2629.55   401.4 2635.49   413.9    2642   430.6 2653.13
#Mann= 3 ,-1,0
       0      .1       0   148.1    .045       0   239.5      .1       0
Bank Sta=148.1,239.5
XS Rating Curve= 0 ,0
Exp/Cntr(USF)=0,0
Exp/Cntr=0.3,0.1

Type RM Length L Ch R = 1 ,39083   ,262.5,262.5,262.5
XS GIS Cut Line= 2
2373780.38617937703388.0356777192373669.08994085702854.581293114
#Sta/Elev= 30
       0 2636.69    23.3 2630.61    64.2 2617.55    76.5 2612.61     101 2598.77
   113.2 2589.95   129.6  2580.2   141.8 2568.43   154.1 2560.44   166.4 2546.28
   170.4 2542.83   174.5  2541.1   188.5 2540.14   190.9 2539.32   198.72533.378
   203.1 2532.55   277.1 2533.25   284.9 2537.74   297.1 2548.66   301.2 2550.81
   321.6 2568.88   329.8  2574.4     338 2582.02   374.8 2601.39     436 2639.14
   476.9 2662.32   509.4 2687.17   519.9 2693.32   534.1 2706.53   544.9 2711.92
#Mann= 3 ,-1,0
       0      .1       0   198.7    .045       0   277.1      .1       0
Bank Sta=198.7,277.1
XS Rating Curve= 0 ,0
Exp/Cntr(USF)=0,0
Exp/Cntr=0.3,0.1

Type RM Length L Ch R = 1 ,38821   ,276.3,276.3,276.3
XS GIS Cut Line= 2
2374012.10846164703303.6258176972373969.15522326702930.263053263
#Sta/Elev= 30
       0 2585.03    38.7 2580.76    70.9 2571.54      87 2564.73   103.1 2555.57
   106.9 2552.63   111.2 2547.95   123.3 2538.99   127.3 2537.47   139.4 2537.53
   143.4 2536.25   147.4 2532.91   148.5 2532.59   151.4 2531.59   159.5 2530.96
   207.8 2530.34   236.9 2530.68     240 2530.95     244 2532.69     244 2532.71
   252.1 2541.26   264.2 2548.88   272.2 2555.78   288.3 2566.37   298.2 2571.41
   308.5 2575.61   336.7 2591.21   352.4 2600.85   360.8 2604.59   375.8 2613.26
#Mann= 3 ,-1,0
       0      .1       0   148.5    .045       0     244      .1       0
Bank Sta=148.5,244
XS Rating Curve= 0 ,0
Exp/Cntr(USF)=0,0
Exp/Cntr=0.3,0.1

Type RM Length L Ch R = 1 ,38544   ,262.9,262.9,262.9
XS GIS Cut Line= 2
 2374072.0590803703353.4954657662374421.29900116702931.337319675
#Sta/Elev= 30
       0 2576.71    21.2 2570.87    81.8 2557.26   136.7 2538.96   182.1 2537.03
   192.5  2537.9   221.9 2531.07   244.4  2530.2   264.5 2527.96   295.1 2526.84
   322.3    2528   327.5 2531.31   345.3 2552.07   353.4 2558.33     369 2568.16
   374.2 2573.68   383.8 2594.47   389.8 2599.37     395  2605.6   405.3 2624.59
   415.1 2641.19   436.5 2685.62   441.7  2694.6   452.1 2707.16   466.2 2726.05
   483.4 2740.01   502.2 2760.62   509.2 2770.15   529.9 2783.92   547.9 2791.71
#Mann= 5 ,-1,0
       0      .1       0   264.5    .045       0   322.3      .1       0
     460     .12       0     510      .1       0
Bank Sta=264.5,322.3
XS Rating Curve= 0 ,0
Exp/Cntr(USF)=0,0
Exp/Cntr=0.3,0.1

Type RM Length L Ch R = 1 ,38282   ,279.4,279.4,279.4
XS GIS Cut Line= 2
 2374244.4675102703416.411690508 2374605.1935609703235.891864857
#Sta/Elev= 30
       0 2548.23     8.2 2546.93      22 2541.93    53.3 2533.78    69.8 2532.22
    80.2 2532.65    89.1  2534.4   111.5 2534.44     116 2533.82   133.9 2526.83
   147.3 2524.58   178.6 2523.58     201 2523.96   204.9 2524.84   209.9 2527.27
   241.2 2551.91   258.6 2563.82   285.4 2586.99   293.2 2599.65   303.8 2615.16
   321.2 2632.63   339.1 2655.72     353 2675.34   357.5 2682.75     362 2694.86
   366.5 2710.34   370.9 2720.95   379.9 2731.38   383.8 2736.88   403.4  2771.2
#Mann= 4 ,-1,0
       0      .1       0   147.3    .045       0   204.9      .1       0
     350     .12       0
Bank Sta=147.3,204.9
XS Rating Curve= 0 ,0
Exp/Cntr(USF)=0,0
Exp/Cntr=0.3,0.1

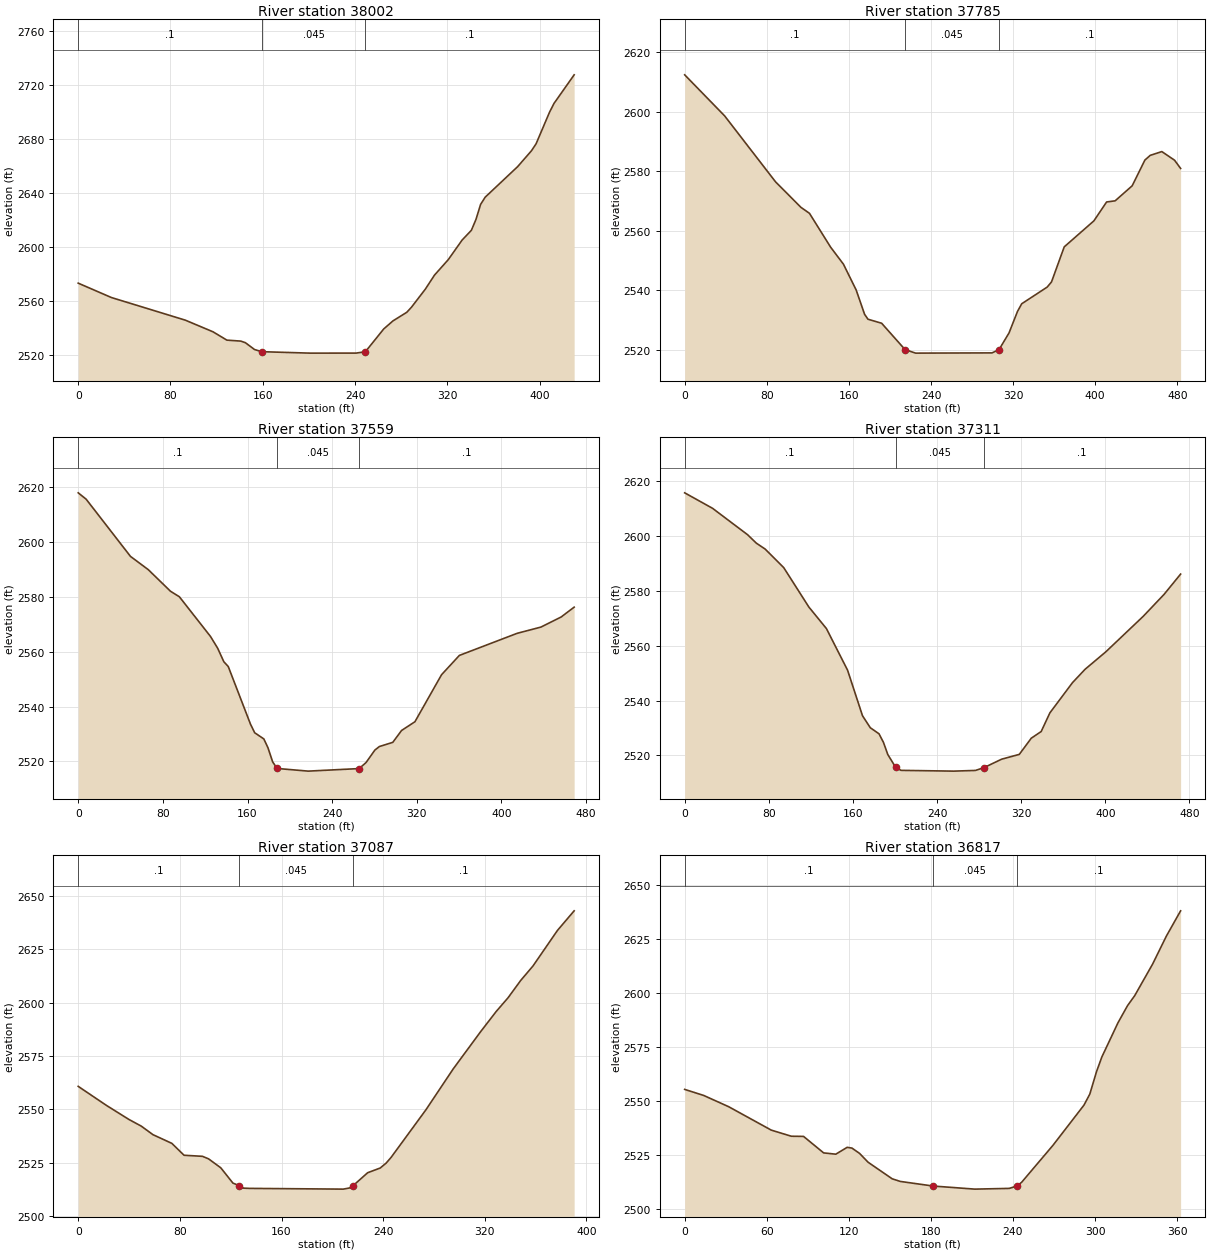
Type RM Length L Ch R = 1 ,38002   ,217.2,217.2,217.2
XS GIS Cut Line= 2
2374183.35531882703610.6281547492374613.18906756703622.141558733
#Sta/Elev= 30
       0 2573.02    28.8 2562.35    92.9 2545.56   116.9 2536.92   128.9 2530.75
   140.9 2530.03   144.9 2528.87   152.9 2523.77   159.2 2522.18   200.9 2521.11
   240.9 2521.13     249 2522.15   264.9 2539.04   272.9 2545.02   284.9 2551.42
   288.9 2555.12   300.9 2568.49   308.9 2578.97   320.9  2590.5   332.9 2605.03
   340.9 2612.24   344.9 2620.35   348.9 2631.47   352.9 2636.83     381 2659.45
     393 2671.25     397 2676.41   408.6 2699.73   412.5 2706.31     430 2727.57
#Mann= 3 ,-1,0
       0      .1       0   159.2    .045       0     249      .1       0
Bank Sta=159.2,249
XS Rating Curve= 0 ,0
Exp/Cntr(USF)=0,0
Exp/Cntr=0.3,0.1

Type RM Length L Ch R = 1 ,37785   ,225.8,225.8,225.8
XS GIS Cut Line= 2
2374090.59086595703760.5358221952374557.81631304703883.637137595
#Sta/Elev= 30
       0 2612.43    38.9 2598.65    88.5 2576.49   113.3  2567.9   121.6 2565.89
   142.3 2554.47   154.7  2548.8   167.1 2540.12   175.3 2531.96   178.6 2530.31
   191.9 2528.96   214.7 2520.11     225 2518.92   299.5    2519   306.3 2520.11
     316 2525.69   324.3 2532.95   328.4 2535.51   353.2 2541.11   357.4 2542.84
   369.8 2554.62   398.7 2563.36   411.1 2569.71   419.4 2570.09     436 2575.14
   448.4 2583.79   453.6 2585.37   464.9 2586.64   477.3 2583.74   483.2 2580.97
#Mann= 3 ,-1,0
       0      .1       0   214.7    .045       0   306.3      .1       0
Bank Sta=214.7,306.3
XS Rating Curve= 0 ,0
Exp/Cntr(USF)=0,0
Exp/Cntr=0.3,0.1

Type RM Length L Ch R = 1 ,37559   ,248,248,248
XS GIS Cut Line= 2
2374065.07804293703974.5787902542374511.51615426704117.348338547
#Sta/Elev= 30
       0 2617.99     7.5 2615.67    49.4  2594.8    66.2 2589.97    87.2 2582.09
    95.6 2580.07     125  2565.6   131.8  2561.3   137.6 2556.38   141.8 2554.63
   162.8 2533.61   166.8 2530.45   175.4 2528.22   179.3 2525.02   183.8 2519.81
     188 2517.43   217.4 2516.46   265.5 2517.39     272 2519.58   280.4 2524.15
   284.6 2525.43   297.3 2526.96   305.6 2531.29   318.2 2534.47   343.4 2551.64
   360.2 2558.67   414.8 2566.73   437.3 2569.01   456.4 2572.69   468.7 2576.28
#Mann= 3 ,-1,0
       0      .1       0     188    .045       0   265.5      .1       0
Bank Sta=188,265.5
XS Rating Curve= 0 ,0
Exp/Cntr(USF)=0,0
Exp/Cntr=0.3,0.1

Type RM Length L Ch R = 1 ,37311   ,224,224,224
XS GIS Cut Line= 2
 2373966.7706645704209.7515482922374419.46514732704341.995315881
#Sta/Elev= 30
       0 2615.67    26.5 2610.03    59.8 2600.42    68.1 2597.35    76.5 2595.19
    94.2 2588.42   118.1 2574.07   134.8 2566.22   154.9 2551.07   169.1 2534.47
   176.5 2530.11   184.8 2527.89     189 2524.79   193.2 2520.31   200.6  2515.7
   205.7 2514.58   255.7  2514.3   276.5 2514.55   284.5 2515.56   301.5 2518.66
   318.2  2520.4   329.6  2526.3     339 2528.72   347.3 2535.53   368.8 2546.53
   380.7 2551.38   400.6  2557.8   436.1 2570.71   455.7 2578.61   471.6 2586.07
#Mann= 3 ,-1,0
       0      .1       0   200.6    .045       0   284.5      .1       0
Bank Sta=200.6,284.5
XS Rating Curve= 0 ,0
Exp/Cntr=0.3,0.1

Type RM Length L Ch R = 1 ,37087   ,270.6,270.6,270.6
XS GIS Cut Line= 2
2373991.01081836 704400.699581352374315.07503115704618.253178748
#Sta/Elev= 30
       0 2560.78    22.4 2551.79    39.9 2545.28    49.6 2542.16    58.8 2538.16
    73.7 2534.07    83.3  2528.5    97.8    2528   102.6 2526.81   112.2 2522.62
   121.8 2515.43   126.7 2514.29     130  2513.1   134.4 2512.98   208.6 2512.63
   213.4 2513.16   216.2 2514.18   227.8 2520.32   237.6  2522.5   242.3  2524.8
   246.2 2527.47   273.6 2549.76   295.1 2568.94   316.6 2586.33     329  2595.9
   338.2 2602.23   348.3 2610.45   357.9 2617.19   377.2 2633.88   390.3 2643.03
#Mann= 3 ,-1,0
       0      .1       0   126.7    .045       0   216.2      .1       0
Bank Sta=126.7,216.2
XS Rating Curve= 0 ,0
Exp/Cntr(USF)=0,0
Exp/Cntr=0.3,0.1

Type RM Length L Ch R = 1 ,36817   ,244.6,244.6,244.6
XS GIS Cut Line= 2
2373890.51129789704524.942045853 2374064.2940185704843.204867388
#Sta/Elev= 30
       0 2555.45    13.9 2552.65    32.2 2547.42    63.3 2536.59      78 2533.75
    86.9 2533.68   101.6 2526.03   110.5 2525.44   118.8 2528.61   122.3 2528.26
   127.9 2525.78   134.1 2521.71   151.7 2514.04   157.6 2512.82  181.572510.686
   212.1 2509.25   237.3 2509.59   243.1 2510.72   246.4 2512.45   269.2 2529.49
   291.9 2548.13   296.2 2553.26   301.1 2563.65     305 2570.45   316.8 2586.31
   323.8 2594.26     329 2598.84   342.1 2613.47   352.2 2626.48   362.6 2638.17
#Mann= 3 ,-1,0
       0      .1       0  181.57    .045       0   243.1      .1       0
Bank Sta=181.57,243.1
XS Rating Curve= 0 ,0
Exp/Cntr=0.3,0.1

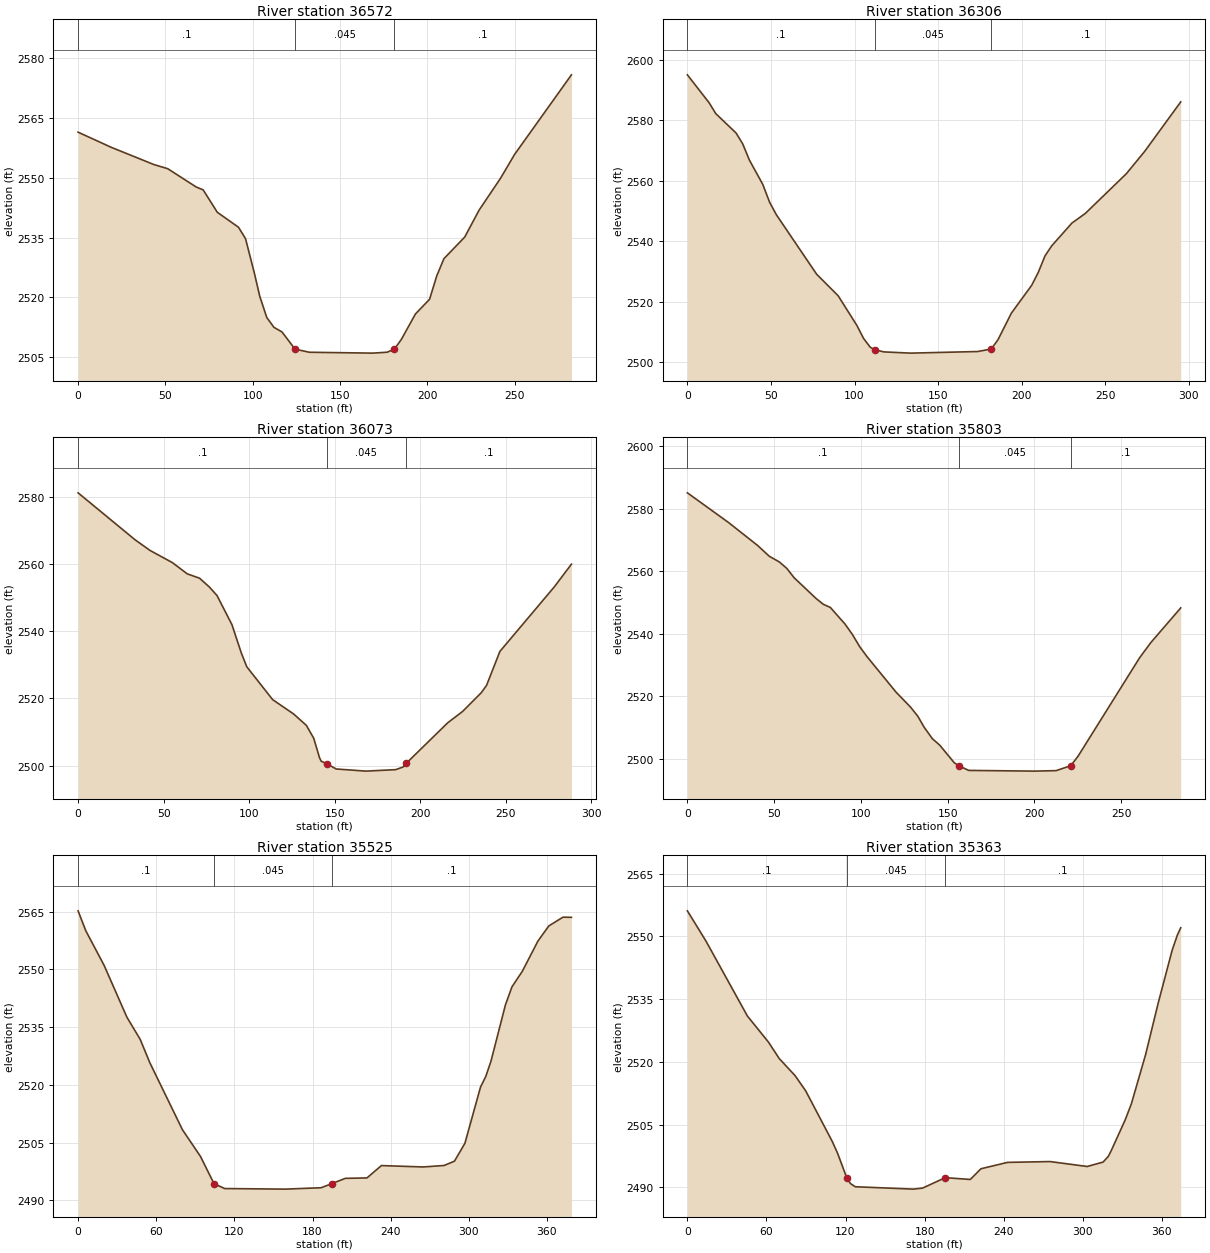
Type RM Length L Ch R = 1 ,36572   ,266,266,266
XS GIS Cut Line= 2
2373807.44997055704518.5411132742373762.12630443 704797.28165994
#Sta/Elev= 30
       0 2561.46    18.9 2557.67    43.5 2553.31    51.3 2552.29    67.5 2547.72
    71.6 2546.96    79.7 2541.34    91.8 2537.59    95.2 2535.19    95.9 2534.64
   100.9 2526.07     104 2520.24     108 2514.93   112.1 2512.45   116.7  2511.3
   124.2 2506.97   132.4 2506.19   168.6 2505.97   176.9  2506.2     181 2506.95
     185 2509.38   193.1  2515.8   201.2  2519.5   205.3 2525.36   209.4 2529.69
   221.3 2535.11   229.6 2541.92   241.8 2549.88   249.9  2555.9   282.4 2575.86
#Mann= 3 ,-1,0
       0      .1       0   124.2    .045       0     181      .1       0
Bank Sta=124.2,181
XS Rating Curve= 0 ,0
Exp/Cntr(USF)=0,0
Exp/Cntr=0.3,0.1

Type RM Length L Ch R = 1 ,36306   ,233.2,233.2,233.2
XS GIS Cut Line= 2
2373510.78845008704488.2337970732373538.82973323704781.978281517
#Sta/Elev= 30
       0 2595.01      13 2585.77      17 2582.17    29.1 2575.78    33.1 2572.17
    37.1  2566.8    45.1 2558.77    49.2 2552.85    53.2 2548.75    77.3 2529.06
    90.2 2521.91   101.4  2512.1   105.4  2507.8   109.4 2504.89   112.2 2504.06
   117.5 2503.36   133.5 2502.95   173.7 2503.48   181.8 2504.33   185.8  2507.4
   193.8 2516.18   205.9 2525.35   209.9 2529.68   213.9 2535.11   217.9 2538.43
     230 2545.97     238 2549.15   262.6 2562.32   273.6 2569.74   295.1 2586.06
#Mann= 3 ,-1,0
       0      .1       0   112.2    .045       0   181.8      .1       0
Bank Sta=112.2,181.8
XS Rating Curve= 0 ,0
Exp/Cntr=0.3,0.1

Type RM Length L Ch R = 1 ,36073   ,269.4,269.4,269.4
XS GIS Cut Line= 2
2373229.57322746704518.5411132742373342.88239277704783.684560103
#Sta/Elev= 30
       0 2581.27    33.3 2567.28      42 2564.12    55.1 2560.48    63.8 2557.13
      71 2555.83    76.8 2553.17    81.2 2550.66    89.9 2542.01    95.4 2533.54
    98.6 2529.43   113.7 2519.66   125.9 2515.41   133.4 2511.99   137.7 2508.16
   141.1 2502.33   142.1  2501.3  145.182500.627   150.8    2499   168.2 2498.36
   185.6  2498.8     190  2499.6  191.712500.656     216 2512.76   224.7 2516.14
   235.6 2521.72   238.7 2523.91   246.5 2534.03   278.3 2553.26   288.3 2560.02
#Mann= 3 ,-1,0
       0      .1       0  145.18    .045       0  191.71      .1       0
Bank Sta=145.18,191.71
XS Rating Curve= 0 ,0
Exp/Cntr(USF)=0,0
Exp/Cntr=0.3,0.1

Type RM Length L Ch R = 1 ,35803   ,278.7,278.7,278.7
XS GIS Cut Line= 2
 2372987.5933355704582.5616137662373073.22164976704853.646332249
#Sta/Elev= 30
       0 2585.07    23.7 2575.57    40.5  2568.2    47.2 2564.76    53.1  2562.9
    57.3 2560.87    61.5 2557.89    74.1 2551.27    78.3 2549.39    82.4 2548.36
    90.8 2543.07      95  2539.8    99.2 2535.89   103.4  2532.7   120.2 2521.28
   128.6 2516.46   132.8 2513.53   136.4 2510.04   141.2 2506.33   145.4 2504.29
   153.8 2498.63   156.4 2497.69   162.1 2496.19   199.9 2495.96   212.5 2496.12
   220.9 2497.69   225.1 2500.71   260.6 2532.26     267 2537.08   284.3 2548.23
#Mann= 3 ,-1,0
       0      .1       0   156.4    .045       0   220.9      .1       0
Bank Sta=156.4,220.9
XS Rating Curve= 0 ,0
Exp/Cntr=0.3,0.1

Type RM Length L Ch R = 1 ,35525   ,161.1,161.1,161.1
XS GIS Cut Line= 3
2372670.95855123704767.0951107982372872.39706734704884.600911862
2373017.88044008704890.196426198
#Sta/Elev= 30
       0  2565.2       6 2559.97      20 2551.02    37.5 2537.55    47.7  2531.8
    55.1 2525.73    80.1 2508.34      94 2501.37  104.342494.331   112.5 2493.04
   158.9 2492.89   186.6 2493.25   194.7  2494.3   205.2 2495.69   221.8  2495.8
   232.9 2499.01     265 2498.65     281 2499.03     289 2500.16     297  2504.8
     309 2519.42     313 2522.14     317 2526.11   328.1 2540.74   333.1 2545.43
   341.1  2549.5     353  2557.3   361.4 2561.27   372.3 2563.55   378.8 2563.51
#Mann= 3 ,-1,0
       0      .1       0  104.34    .045       0   194.7      .1       0
Bank Sta=104.34,194.7
XS Rating Curve= 0 ,0
Exp/Cntr(USF)=0,0
Exp/Cntr=0.3,0.1

Type RM Length L Ch R = 1 ,35363   ,231.9,231.9,231.9
XS GIS Cut Line= 2
2372643.02876017705021.9566657112373014.68282239704976.632999586
#Sta/Elev= 30
       0 2556.11    14.2 2548.83    45.5 2530.99    61.6  2524.7    69.7  2520.8
    81.7 2516.73    89.8 2513.07     110 2500.96     114 2498.15   121.12492.162
   123.8 2490.91   127.4 2490.16   171.6 2489.59   178.5 2489.84   195.7 2492.33
   214.7  2491.9   222.8 2494.46   242.9 2495.98   275.2 2496.18   303.4    2495
   315.5 2496.06   319.5 2497.45   321.7 2498.83   332.2 2506.11   336.9 2509.95
   347.7 2521.71   357.3 2534.08   367.9 2546.71   371.9 2550.37   374.4 2552.07
#Mann= 3 ,-1,0
       0      .1       0   121.1    .045       0   195.7      .1       0
Bank Sta=121.1,195.7
XS Rating Curve= 0 ,0
Exp/Cntr(USF)=0,0
Exp/Cntr=0.3,0.1

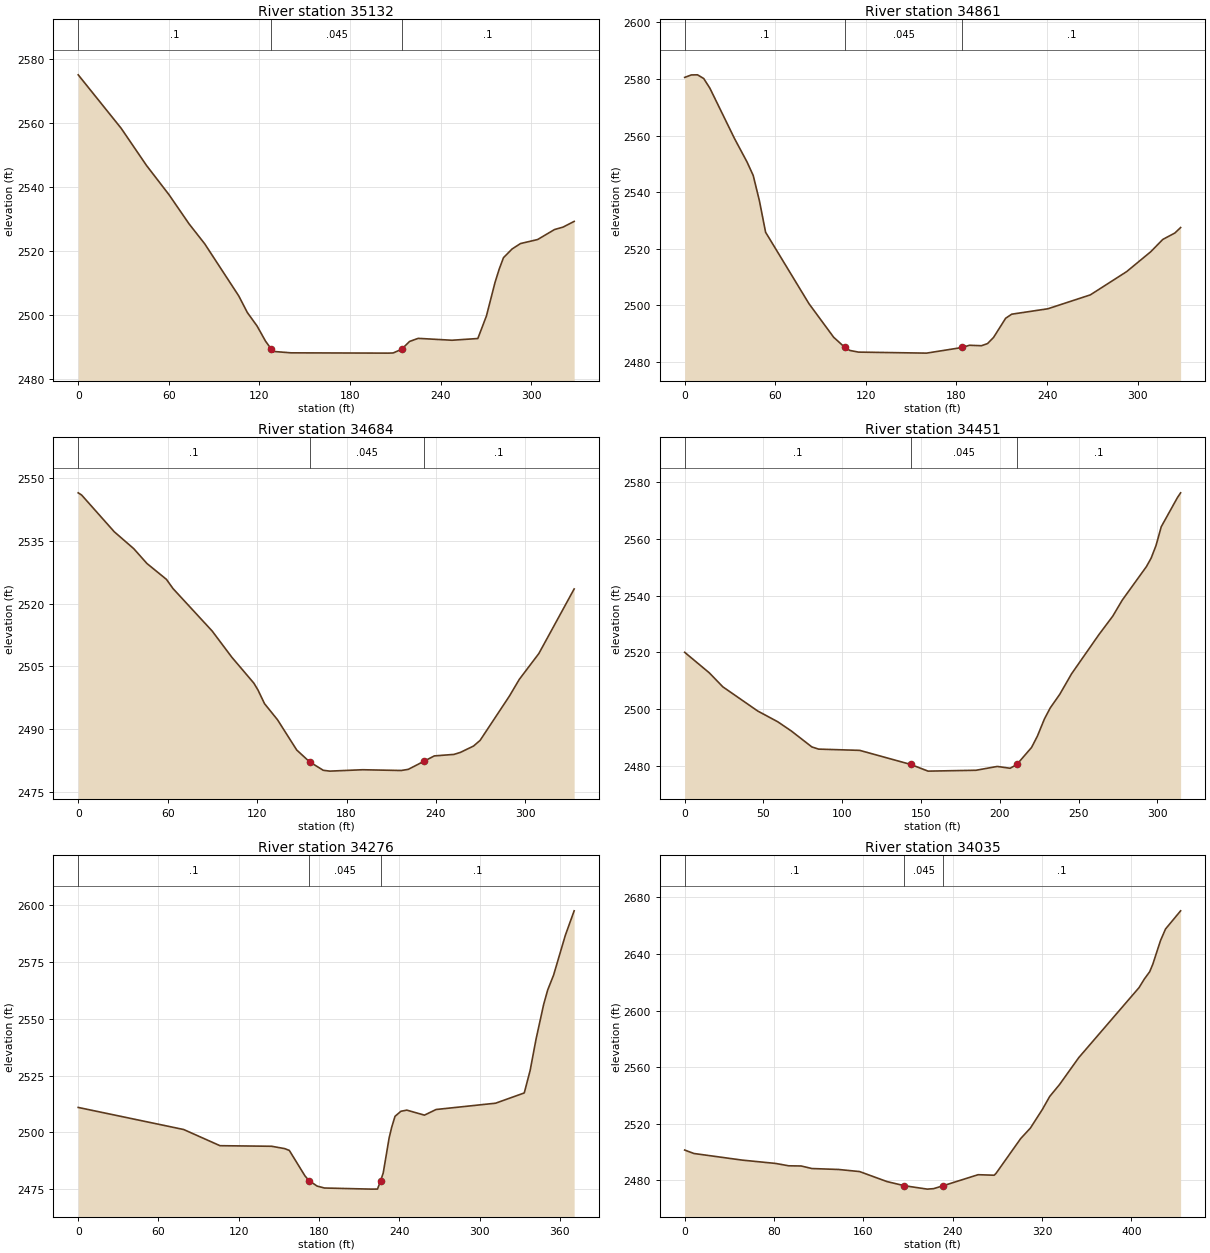
Type RM Length L Ch R = 1 ,35132   ,270.9,270.9,270.9
XS GIS Cut Line= 2
2372837.92052451705289.3662958452373069.07122174705055.949415304
#Sta/Elev= 30
       0 2575.12    28.4 2558.43    45.3 2546.73    60.1 2537.65    73.4 2528.52
    83.8 2522.26   106.4 2505.92     112 2500.79   118.5 2496.53   124.1  2491.8
  127.972489.275   129.7 2488.58     141 2488.16   205.4 2488.07   208.6 2488.12
   214.2 2489.27   219.5 2491.73   225.2 2492.69   247.6  2492.1   264.7 2492.64
   270.4  2499.7   276.1  2510.2   278.9 2514.42   281.7 2517.93   287.4 2520.65
     293 2522.35   304.3  2523.6   315.5 2526.73   321.1 2527.48   328.5 2529.27
#Mann= 3 ,-1,0
       0      .1       0  127.97    .045       0   214.2      .1       0
Bank Sta=127.97,214.2
XS Rating Curve= 0 ,0
Exp/Cntr(USF)=0,0
Exp/Cntr=0.3,0.1

Type RM Length L Ch R = 1 ,34861   ,176.9,176.9,176.9
XS GIS Cut Line= 3
 2373234.5026031705341.4885118892373195.97748689705169.258580615
2373189.17893697705017.424299098
#Sta/Elev= 30
       0 2580.54     4.4 2581.41     8.5 2581.45    12.6 2580.15    16.7 2576.72
    33.1 2558.83    41.3 2550.65    45.4 2545.87    49.5 2536.94    53.6 2525.81
    82.3 2500.58    98.7 2488.68     106 2485.15   109.4 2484.03   115.1 2483.44
   160.2 2483.08     184 2485.09   188.6 2485.86   196.6  2485.7   200.6 2486.45
   204.6 2488.63   212.6  2495.4   216.6 2496.84   240.6 2498.76   268.7 2503.67
   292.7 2511.87   308.7 2518.91   316.7 2523.27   324.7 2525.54   328.5 2527.47
#Mann= 3 ,-1,0
       0      .1       0     106    .045       0     184      .1       0
Bank Sta=106,184
XS Rating Curve= 0 ,0
Exp/Cntr(USF)=0,0
Exp/Cntr=0.3,0.1

Type RM Length L Ch R = 1 ,34684   ,232.8,232.8,232.8
XS GIS Cut Line= 2
2373420.32963421705271.2368293962373284.35863583704967.568266361
#Sta/Elev= 30
       0 2546.39     2.3 2545.86    24.2  2537.1    37.3 2533.06    46.1 2529.54
    59.2 2525.75    63.6 2523.56    89.9 2513.42   103.1 2507.17   117.8 2501.02
   120.6 2499.37     125 2496.11   133.7 2492.28   146.6 2485.06  155.212482.245
   164.4 2480.23   168.8 2480.03   190.7 2480.36   216.6 2480.18   221.4 2480.45
   231.7 2482.33   238.9 2483.66   252.1 2484.02   256.4  2484.5   265.2 2486.01
   269.6 2487.36   289.3 2497.94   295.9 2501.91     309 2508.06   332.7 2523.47
#Mann= 3 ,-1,0
       0      .1       0  155.21    .045       0   231.7      .1       0
Bank Sta=155.21,231.7
XS Rating Curve= 0 ,0
Exp/Cntr(USF)=0,0
Exp/Cntr=0.3,0.1

Type RM Length L Ch R = 1 ,34451   ,174.6,174.6,174.6
XS GIS Cut Line= 2
 2373490.5813167705239.5102631082373612.95521524704949.438799911
#Sta/Elev= 30
       0 2519.98    15.6 2512.76    24.2 2507.82    46.4 2499.27      59 2495.52
    67.7 2492.24    80.7 2486.63      85 2485.85   111.1 2485.41   143.4 2480.46
   154.5 2478.09   184.9 2478.39   198.4 2479.74   206.6  2479.1   210.9 2480.46
   220.2 2486.45   223.9 2490.44   228.3 2496.42     232 2500.34   238.1 2505.19
   245.6 2512.42     263 2526.27   271.7 2532.71   277.8 2538.42   293.1  2550.2
   296.1  2553.2   299.2 2557.66   302.5 2564.25   312.8 2574.55   314.8 2576.21
#Mann= 3 ,-1,0
       0      .1       0   143.4    .045       0   210.9      .1       0
Bank Sta=143.4,210.9
XS Rating Curve= 0 ,0
Exp/Cntr(USF)=0,0
Exp/Cntr=0.3,0.1

Type RM Length L Ch R = 1 ,34276   ,241.7,241.7,241.7
XS GIS Cut Line= 2
2373627.67994928705348.9876267342373780.34148771705011.153314106
#Sta/Elev= 30
       0 2510.98    78.8 2501.29     106 2494.18   144.6 2493.93   154.4 2492.89
   157.8  2492.1   169.5 2480.92   172.6 2478.81   178.6 2476.44   184.1  2475.6
   219.3 2475.11   223.7 2475.14   226.12478.839     228 2482.24   232.4 2497.58
   234.3 2502.23   236.8 2507.08   241.2 2509.29   245.6  2509.8   258.8  2507.6
   267.5 2510.07     312 2512.84   333.4 2517.34   337.8 2527.21   342.2 2540.91
   347.9 2556.19   350.9 2562.52   355.3 2569.03   364.1 2586.54   370.7 2597.31
#Mann= 3 ,-1,0
       0      .1       0   172.6    .045       0   226.1      .1       0
Bank Sta=172.6,226.1
XS Rating Curve= 0 ,0
Exp/Cntr=0.3,0.1

Type RM Length L Ch R = 1 ,34035   ,233.2,233.2,233.2
XS GIS Cut Line= 2
2373677.28466749705455.307941172 2374047.2103375705209.727034187
#Sta/Elev= 30
       0 2501.32     8.3 2498.87    51.5  2494.2    81.5 2491.84    93.1 2490.17
   104.3 2490.04   113.9 2488.24   137.9 2487.56   156.6 2486.09   181.1 2479.02
   196.62476.095   217.2 2473.67   222.9 2474.01   231.6 2476.12   262.7 2483.87
   277.1 2483.51   278.7 2484.77   300.8 2509.41   309.5 2516.85   320.3 2530.13
   326.8 2539.22   335.5 2547.56   352.8 2566.68   406.8 2616.24   411.6 2622.39
   416.3 2627.44   419.1 2632.77     426 2649.52   430.5  2657.7     444 2670.54
#Mann= 3 ,-1,0
       0      .1       0   196.6    .045       0   231.6      .1       0
Bank Sta=196.6,231.6
XS Rating Curve= 0 ,0
Exp/Cntr(USF)=0,0
Exp/Cntr=0.3,0.1