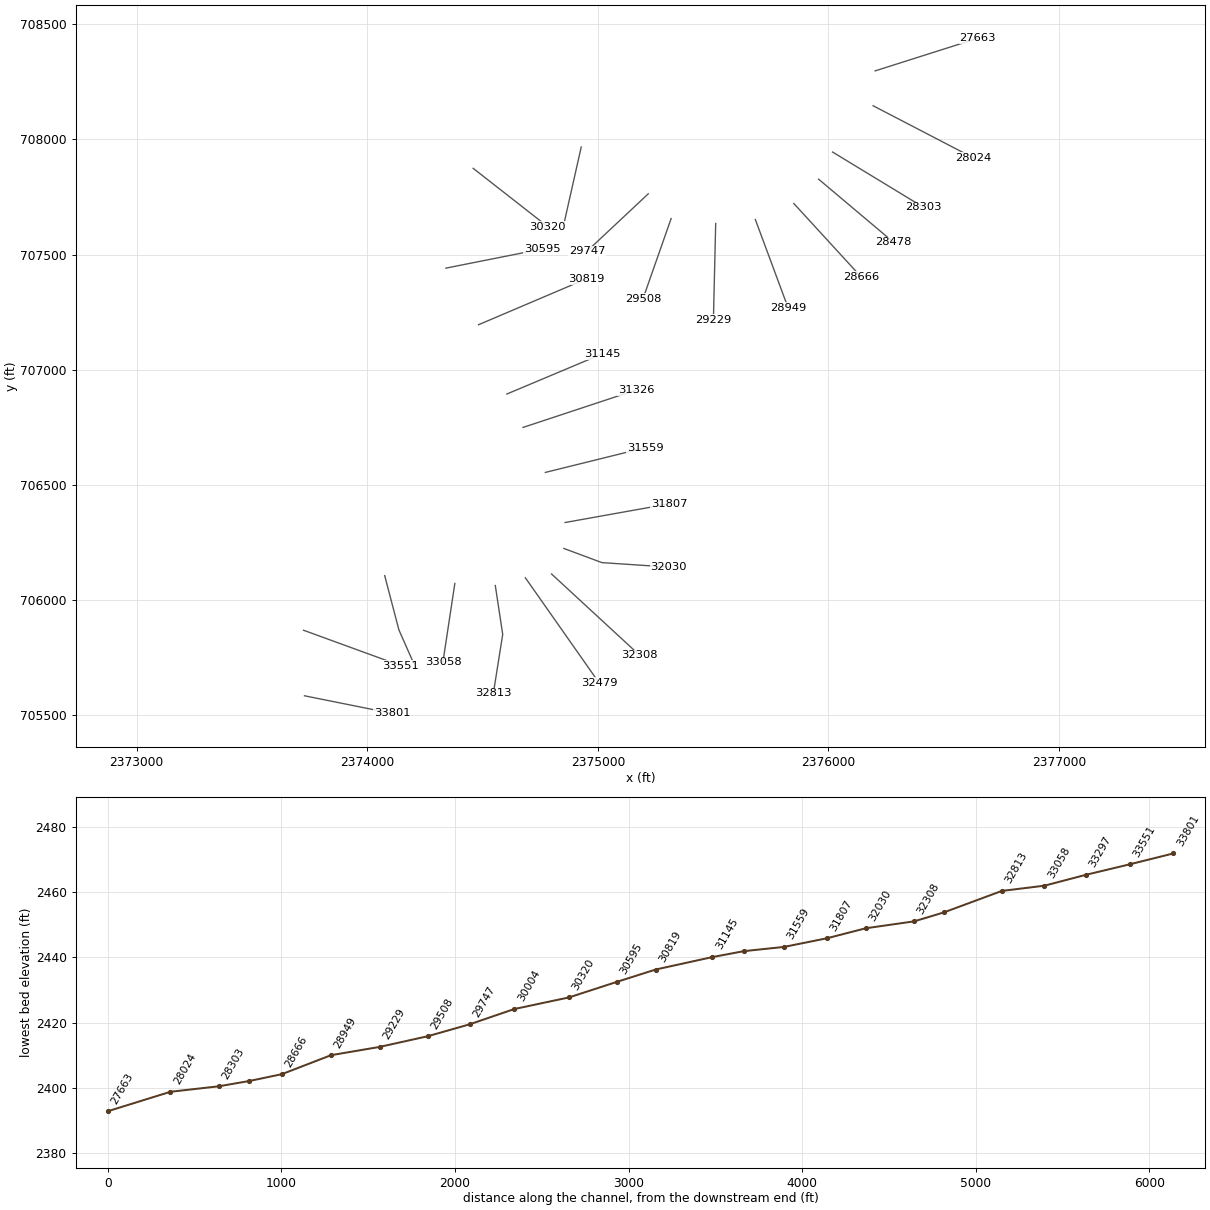
HEC-RAS study LAURELFK.prj: LAURELFK

--- LAURELFK.g01 (geometry) --- (continued)

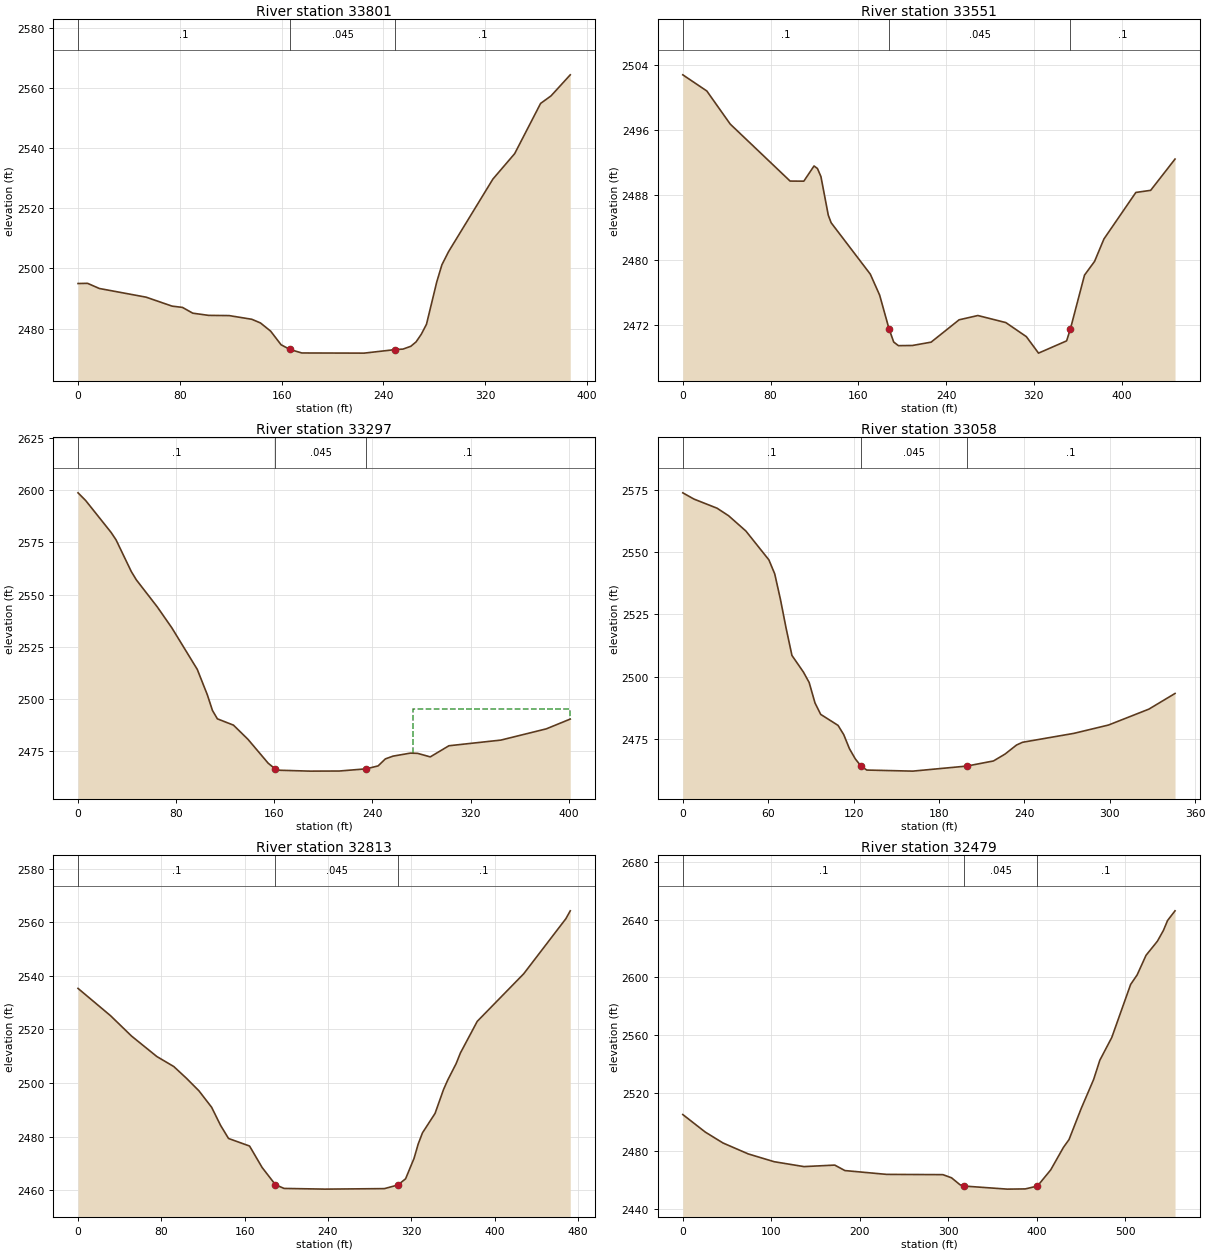
Type RM Length L Ch R = 1 ,33801   ,250.3,250.3,250.3
XS GIS Cut Line= 2
2373727.71013583705585.548216043  2374106.983176705509.186076549
#Sta/Elev= 30
       0    2495     7.5 2495.06    16.8 2493.34    53.5 2490.46    73.9 2487.48
    82.1 2487.05    90.2 2485.13   102.6  2484.4   118.8 2484.33   136.6  2483.1
   143.4 2481.88   151.4 2479.16   159.6 2474.63  166.462473.078   175.9 2471.89
   224.9 2471.84   249.4 2473.02   255.4 2473.18   261.6 2474.12   265.7 2475.57
   269.8 2478.11   273.9 2481.45     282 2495.58     286 2501.22   291.3 2505.64
   326.1 2529.75   343.2  2538.2   363.6 2554.92   371.8 2557.43   386.9 2564.43
#Mann= 3 ,-1,0
       0      .1       0  166.46    .045       0   249.4      .1       0
Bank Sta=166.46,249.4
XS Rating Curve= 0 ,0
Exp/Cntr=0.3,0.1

Type RM Length L Ch R = 1 ,33551   ,253.5,253.5,253.5
XS GIS Cut Line= 2
2373723.59860869705869.9831863342374144.98919451705716.254374191
#Sta/Elev= 30
       0 2502.78    21.9 2500.79    43.2 2496.72    97.8  2489.7   110.3 2489.69
   119.6 2491.56   122.7 2491.25   125.9 2490.25   132.6  2485.5   135.2 2484.57
   170.9 2478.24   179.4 2475.66     188 2471.49   192.2 2469.89   196.5 2469.44
   209.2 2469.46   226.3 2469.87   251.8 2472.62   268.9 2473.15   294.4 2472.28
   313.1 2470.55   324.2 2468.52   349.8 2470.03  353.252471.501   366.1 2478.12
   375.3 2479.82   383.8 2482.57   412.9  2488.3   426.4 2488.56   448.6 2492.41
#Mann= 3 ,-1,0
       0      .1       0     188    .045       0  353.25      .1       0
Bank Sta=188,353.25
XS Rating Curve= 0 ,0
Exp/Cntr(USF)=0,0
Exp/Cntr=0.3,0.1

Type RM Length L Ch R = 1 ,33297   ,239.1,239.1,239.1
XS GIS Cut Line= 3
2374075.51133353706107.1805693182374137.06319967705871.738967263
2374200.80895252705727.339878915
#Sta/Elev= 30
       0 2598.78     6.2 2595.11    26.9 2579.83      31 2576.22    43.4 2561.04
    47.5 2557.06    64.5 2544.14    76.5 2533.99    97.2 2514.09   105.4 2501.89
   109.6 2494.35   113.6 2490.37   126.7 2487.35   138.5 2480.56     155 2469.08
   160.8 2466.33   163.3 2465.73     189 2465.29   212.9 2465.34   234.9 2466.39
   244.6  2467.8   250.5 2471.16   256.8 2472.49   270.9 2473.93   276.8 2473.81
   287.1 2472.12   302.3 2477.46   344.7 2480.18   381.7 2485.57   401.2 2490.26
#Mann= 3 ,-1,0
       0      .1       0   160.8    .045       0   234.9      .1       0
#XS Ineff= 2 , 0
                          273.04            2495
Permanent Ineff=
       F       F
Bank Sta=160.8,234.9
XS Rating Curve= 0 ,0
Exp/Cntr=0.3,0.1

Type RM Length L Ch R = 1 ,33058   ,245.8,245.8,245.8
XS GIS Cut Line= 2
2374379.75314332706073.0039895522374327.94282539705731.055891219
#Sta/Elev= 30
       0 2573.91     7.9 2571.38    24.1 2567.72    32.2 2564.68    44.3 2558.57
    60.5 2546.94    64.6 2541.31    68.6 2531.09    72.6 2519.45    76.7  2508.5
    84.8 2501.78    88.8 2497.61    92.9 2489.39    96.9 2484.79   109.1 2480.36
   113.1 2476.64   117.1 2470.99   121.2  2466.9   125.2 2464.02   129.3 2462.39
   161.6 2461.96   199.7    2464   218.3 2466.05   226.4  2468.8   234.5 2472.45
   238.7 2473.56   274.9 2477.16   299.2 2480.51   327.5 2486.89   345.9  2493.2
#Mann= 3 ,-1,0
       0      .1       0   125.2    .045       0   199.7      .1       0
Bank Sta=125.2,199.7
XS Rating Curve= 0 ,0
Exp/Cntr(USF)=0,0
Exp/Cntr=0.3,0.1

Type RM Length L Ch R = 1 ,32813   ,333.5,333.5,333.5
XS GIS Cut Line= 3
2374555.23404917706064.0152351972374587.36261908705852.072571682
2374546.91223815705597.073335303
#Sta/Elev= 30
       0 2535.35    31.2 2525.16    51.4 2517.54    75.7 2509.89    91.9 2506.17
     104 2501.81   116.1 2497.08   128.3 2490.92   136.8 2484.22   144.5 2479.28
   164.7 2476.45   176.8 2468.41   189.5 2462.02   197.8 2460.61   237.2 2460.35
   294.2 2460.54   307.1  2461.9   314.5 2464.21   322.6 2471.83   326.6  2477.2
   330.7 2481.38   342.8 2488.65   350.9 2497.54     355 2501.14     363 2507.22
   367.1  2511.2   383.3 2523.04   427.9 2540.81   468.4  2561.4   472.6 2564.34
#Mann= 3 ,-1,0
       0      .1       0   189.5    .045       0   307.1      .1       0
Bank Sta=189.5,307.1
XS Rating Curve= 0 ,0
Exp/Cntr=0.3,0.1

Type RM Length L Ch R = 1 ,32479   ,171.3,171.3,171.3
XS GIS Cut Line= 2
2374685.53437845706097.7713251142375005.02265263705642.303684034
#Sta/Elev= 30
       0 2505.29    25.5 2493.15    45.4 2485.66      74 2478.09   103.3 2472.71
   136.9 2469.34   171.7 2470.38   183.2  2466.6   230.4 2463.96   293.9 2463.78
   303.7 2461.61   313.4 2456.75   318.2 2455.89   366.8 2453.78   387.1 2453.93
   400.8  2455.9   415.8 2467.07   430.2 2482.63   436.5 2488.01   450.2 2509.39
   464.3  2529.5   471.3 2542.79   484.8 2558.51   506.1 2595.12   513.5 2601.78
   523.5 2615.25   536.4 2625.05   543.1 2632.38   547.9 2639.36   556.3 2646.01
#Mann= 3 ,-1,0
       0      .1       0   318.2    .045       0   400.8      .1       0
Bank Sta=318.2,400.8
XS Rating Curve= 0 ,0
Exp/Cntr(USF)=0,0
Exp/Cntr=0.3,0.1

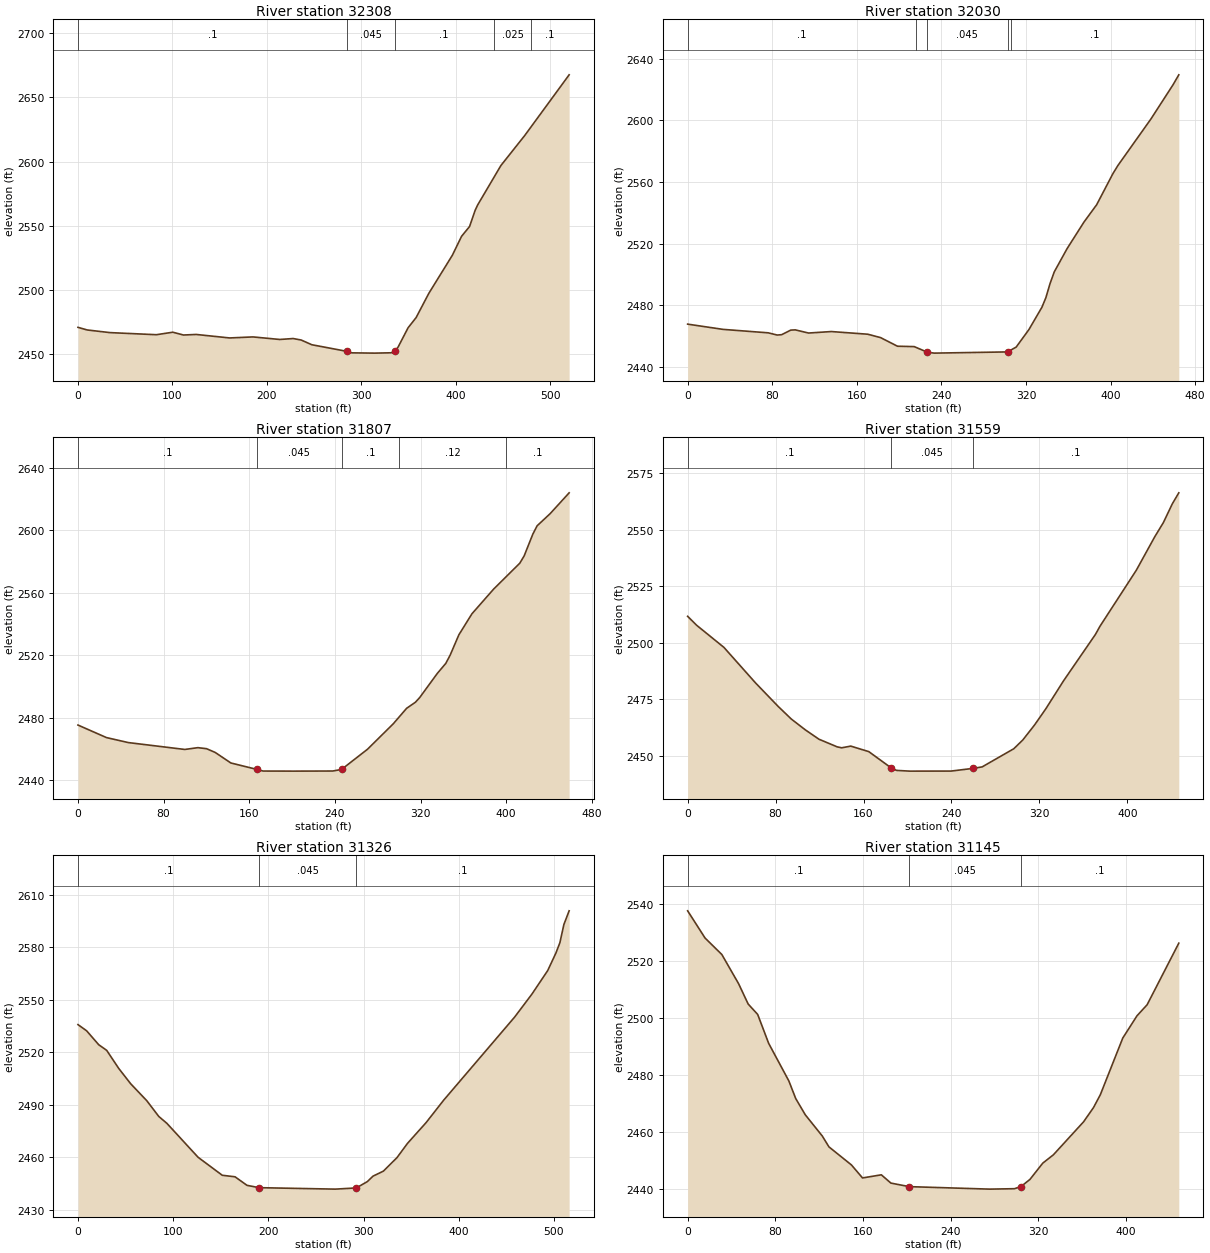
Type RM Length L Ch R = 1 ,32308   ,278.1,278.1,278.1
XS GIS Cut Line= 2
2374799.22492031706114.1334085922375181.27084167705761.305605728
#Sta/Elev= 30
       0 2471.09     9.8 2469.04      34 2466.99      83 2465.36   100.4  2467.3
   111.7 2465.12   125.2 2465.55   160.6 2462.84   185.3 2463.64   213.6 2461.66
   227.8 2462.38   236.3 2461.23   247.6 2457.56   284.7 2452.42   290.1 2451.25
   313.9 2451.04   331.6  2451.3   335.4 2452.45   338.9 2455.73   349.5 2470.76
     358 2478.68   371.5 2497.58   396.4 2527.18   406.1 2541.85   414.6 2549.51
   420.5 2562.09   423.1 2566.17   447.8 2596.94   473.1 2620.35     520 2667.42
#Mann= 5 ,-1,0
       0      .1       0   284.7    .045       0   335.4      .1       0
     440    .025       0     480      .1       0
Bank Sta=284.7,335.4
XS Rating Curve= 0 ,0
Exp/Cntr=0.3,0.1

Type RM Length L Ch R = 1 ,32030   ,222.7,222.7,222.7
XS GIS Cut Line= 3
2374852.77084339706224.901545581 2375017.7963005706163.496724331
 2375305.6314001706144.307717691
#Sta/Elev= 30
       0 2467.74    33.5 2464.34    76.2  2462.1    84.7 2460.66      89 2460.91
    97.5 2463.86   101.8 2464.02   114.4 2461.97   135.9 2462.93   170.4  2461.2
   182.5    2459   198.5 2453.41   214.3 2453.16   226.6 2449.57   233.1 2448.93
   302.7 2449.72   310.8 2452.88   322.8  2464.2   335.1 2478.68   338.8  2484.8
   342.8 2494.04   346.8 2501.65   358.9 2516.71   374.9 2533.98   386.9 2545.22
   402.2 2565.31     407 2570.69   438.2 2600.84   459.1 2623.02   464.6 2629.52
#Mann= 5 ,-1,0
       0      .1       0  216.08     .12       0   226.6    .045       0
   302.7     .12       0  306.08      .1       0
Bank Sta=226.6,302.7
XS Rating Curve= 0 ,0
Exp/Cntr(USF)=0,0
Exp/Cntr=0.3,0.1

Type RM Length L Ch R = 1 ,31807   ,247.7,247.7,247.7
XS GIS Cut Line= 2
2374857.95828377706337.5811901672375309.59318899706418.556094197
#Sta/Elev= 30
       0 2475.37    26.6 2467.35      47 2464.15    99.8 2459.75     112  2460.9
   120.1 2460.23   128.2 2457.84   142.8  2451.1     167    2447   172.9 2445.93
   201.3 2445.88     238 2445.95   246.2 2446.95   270.5 2459.91   294.5 2476.16
     307 2486.09   315.2 2489.97   319.2 2492.96   335.8 2508.54   343.6 2514.84
   347.7 2520.18   355.8 2533.12     368 2546.57   388.3 2562.39   412.7 2578.95
   416.8 2583.64   424.9 2597.57   428.9 2602.89   441.1 2610.68   458.8 2623.99
#Mann= 5 ,-1,0
       0      .1       0     167    .045       0   246.2      .1       0
     300     .12       0     400      .1       0
Bank Sta=167,246.2
XS Rating Curve= 0 ,0
Exp/Cntr=0.3,0.1

Type RM Length L Ch R = 1 ,31559   ,233.1,233.1,233.1
XS GIS Cut Line= 2
 2374772.1770155706554.9524597972375205.84856557706662.410896983
#Sta/Elev= 30
       0 2511.74     8.2 2507.77      33 2497.99    61.8 2482.24    82.4 2471.84
    94.3 2466.27   107.1 2461.47   119.5 2457.33     136 2453.97   140.1 2453.54
   148.4 2454.29   164.8 2451.85   185.4 2444.56   190.1 2443.54   201.9 2443.22
   239.6 2443.24   259.9 2444.45   267.9 2445.09   296.7 2453.13   304.9 2457.01
   315.6 2463.66   325.7 2470.71     342 2483.22   370.9 2503.67   375.1 2507.34
   408.1 2532.09     425 2547.01   432.7 2553.16   440.9 2561.52   446.8 2566.39
#Mann= 3 ,-1,0
       0      .1       0   185.4    .045       0   259.9      .1       0
Bank Sta=185.4,259.9
XS Rating Curve= 0 ,0
Exp/Cntr(USF)=0,0
Exp/Cntr=0.3,0.1

Type RM Length L Ch R = 1 ,31326   ,180.8,180.8,180.8
XS GIS Cut Line= 2
2374675.54172502706750.2926862992375165.42196616706912.397757241
#Sta/Elev= 30
       0 2535.85     9.1 2532.31    21.8 2524.36    30.2 2521.14    42.8 2510.84
    55.4 2502.06    72.3 2492.39    84.9  2483.4    93.4 2479.48   126.2 2460.09
   151.6 2449.82     165 2448.95   177.6 2444.07   190.3 2442.74   270.3 2441.91
   292.4 2442.59     304  2446.2   309.9  2449.3   320.9  2452.2   335.2 2459.93
   346.2 2468.04   365.7 2479.87   384.1 2492.64   458.7 2540.12   476.8 2553.18
   493.5 2566.71   502.1  2576.7   506.3 2582.64   510.5 2593.03     516 2600.81
#Mann= 3 ,-1,0
       0      .1       0   190.3    .045       0   292.4      .1       0
Bank Sta=190.3,292.4
XS Rating Curve= 0 ,0
Exp/Cntr=0.3,0.1

Type RM Length L Ch R = 1 ,31145   ,326.3,326.3,326.3
XS GIS Cut Line= 2
2374605.28984097706895.2483846582375018.23879899707068.989104802
#Sta/Elev= 30
       0 2537.55    15.9 2528.02    31.2 2522.25    46.5 2512.02    55.2 2504.92
    63.9 2501.26    73.9 2491.15    92.3    2478    98.6 2471.81   107.3 2466.13
   122.8 2458.71   128.9 2454.89   149.4 2448.57   159.5 2444.02   176.7 2445.11
   185.4 2442.21   202.2 2440.97   275.5  2440.1   298.2 2440.25   304.1 2441.02
   312.2 2443.49   323.9 2449.19   333.6 2452.12   361.1 2463.65   370.2 2468.66
   376.4 2473.13   396.9 2493.01   409.9 2500.81   419.1 2504.66     448 2526.23
#Mann= 3 ,-1,0
       0      .1       0   202.2    .045       0   304.1      .1       0
Bank Sta=202.2,304.1
XS Rating Curve= 0 ,0
Exp/Cntr(USF)=0,0
Exp/Cntr=0.3,0.1

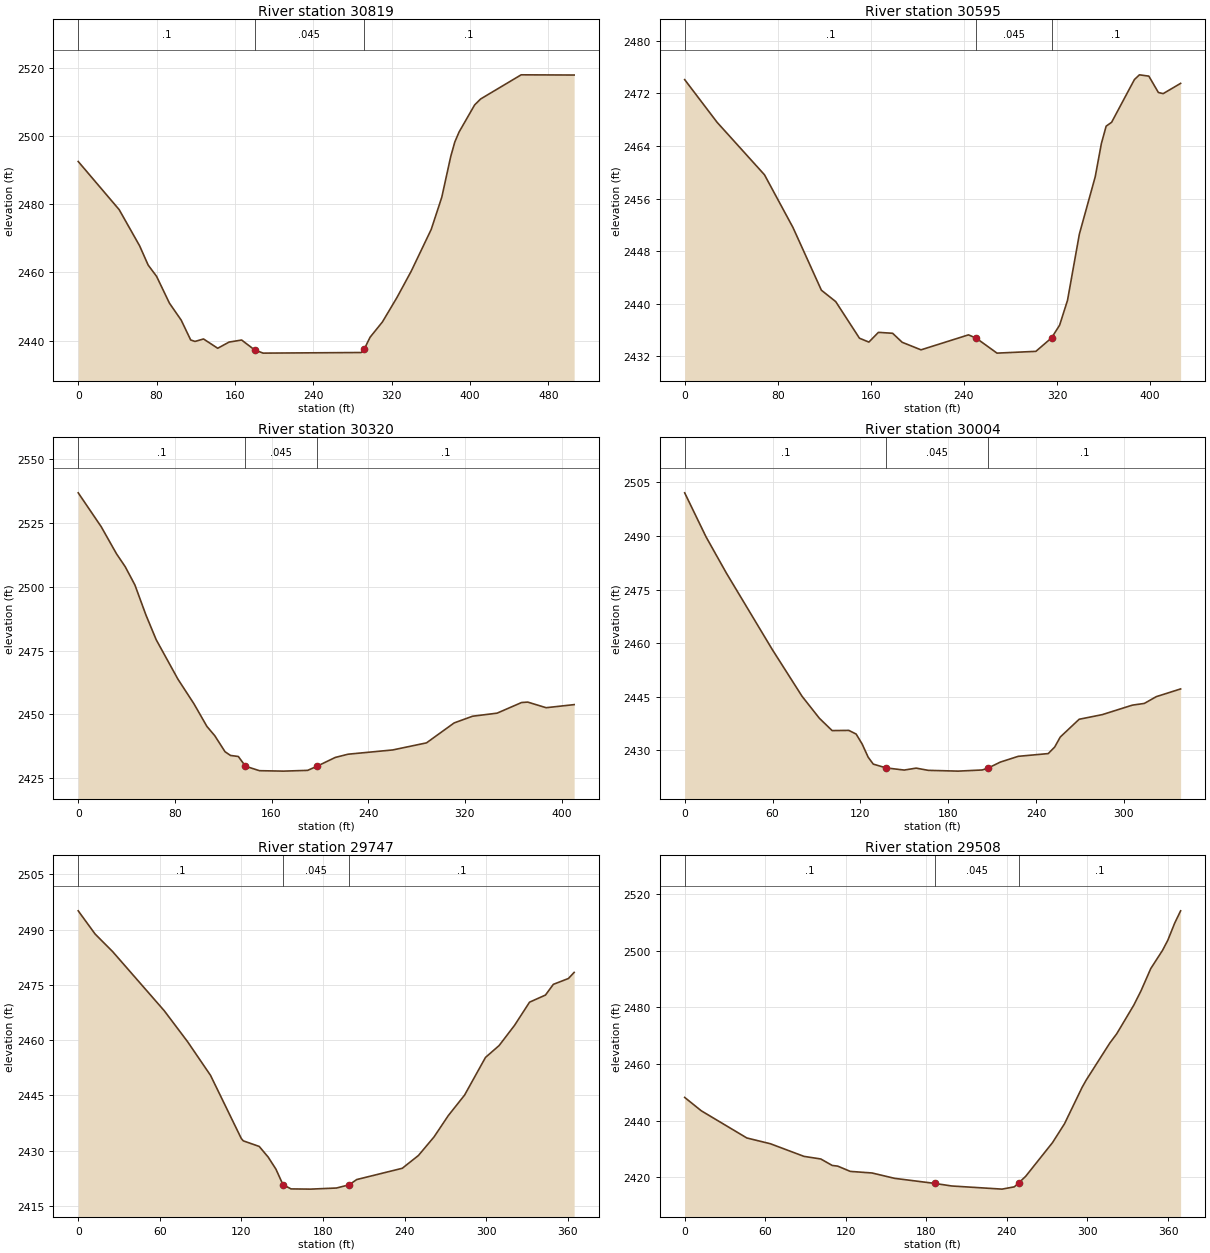
Type RM Length L Ch R = 1 ,30819   ,224.3,224.3,224.3
XS GIS Cut Line= 2
2374482.52959518707195.993741945 2374948.2264315707394.359956397
#Sta/Elev= 30
       0 2492.64    41.8 2478.48    62.7 2467.83    71.4 2462.18      80 2458.86
    93.1 2450.99   105.1    2446   114.8 2440.16   119.2 2439.73   127.9 2440.45
   142.4 2437.72     154 2439.54   166.8 2440.14     180 2437.25   188.7 2436.29
   288.8 2436.47   291.8 2437.38   297.9 2440.96   310.5 2445.46   325.4 2452.67
   339.9 2460.38   360.3 2472.66   371.1 2482.14   380.2 2494.07   384.4 2498.38
   388.7 2501.28   404.6 2509.26   410.7 2511.01   452.1 2518.12   506.2 2518.06
#Mann= 3 ,-1,0
       0      .1       0     180    .045       0   291.8      .1       0
Bank Sta=180,291.8
XS Rating Curve= 0 ,0
Exp/Cntr=0.3,0.1

Type RM Length L Ch R = 1 ,30595   ,275.2,275.2,275.2
XS GIS Cut Line= 2
2374340.90178857707441.650359604 2374758.8867095707524.743747499
#Sta/Elev= 30
       0 2474.11    27.8 2467.63    68.6 2459.63    93.1  2451.6   117.5 2442.07
   129.8 2440.34   150.2 2434.77   158.3 2434.18   166.5 2435.66   178.7 2435.52
   186.9 2434.15   203.1    2433   243.9 2435.28   250.7 2434.76   268.4  2432.5
   301.8 2432.77   315.3 2434.82   322.2 2436.75     329 2440.53   339.2 2450.62
   352.8 2459.32   358.1 2464.38   362.2 2467.03   366.9 2467.62   386.5 2474.12
   390.8 2474.84   398.9 2474.64   407.1 2472.15   411.2 2471.98   426.2 2473.54
#Mann= 3 ,-1,0
       0      .1       0   250.7    .045       0   315.3      .1       0
Bank Sta=250.7,315.3
XS Rating Curve= 0 ,0
Exp/Cntr(USF)=0,0
Exp/Cntr=0.3,0.1

Type RM Length L Ch R = 1 ,30320   ,315.3,315.3,315.3
XS GIS Cut Line= 2
2374459.22409437707874.8322209572374782.43386484707621.863802867
#Sta/Elev= 30
       0  2536.8      19 2523.54    31.7  2512.9    38.9 2507.85    46.9 2500.72
      56 2488.99    64.5 2479.27    82.5  2463.8    95.9 2454.04   106.5 2445.27
     113 2441.64   121.5 2435.35     126  2433.9   132.5 2433.48   138.4 2429.68
     150 2427.92     170 2427.75   189.9 2428.05   197.4 2429.61   212.7 2433.11
   223.3 2434.38   260.3 2436.05   288.2 2438.82   311.1 2446.64   326.3 2449.26
   346.6 2450.46   366.9 2454.63     372  2454.8   387.2  2452.6   410.4 2453.81
#Mann= 3 ,-1,0
       0      .1       0   138.4    .045       0   197.4      .1       0
Bank Sta=138.4,197.4
XS Rating Curve= 0 ,0
Exp/Cntr=0.3,0.1

Type RM Length L Ch R = 1 ,30004   ,257.3,257.3,257.3
XS GIS Cut Line= 2
2374927.90501616707967.424341843 2374853.5628728707637.014815796
#Sta/Elev= 30
       0 2502.06    14.6 2489.73    28.4 2479.66    59.7  2458.3    80.2 2445.11
      92 2438.98   100.7 2435.53   112.1 2435.59   117.1 2434.56   121.2 2431.78
   125.3  2428.1   128.8 2426.15   137.6 2425.09   149.9 2424.49   158.1 2425.03
   166.3 2424.41   186.8 2424.19   203.2 2424.51   207.3 2425.06   215.5 2426.71
   227.8 2428.33   248.3  2429.1   252.7 2430.93   256.5 2433.73   269.4  2438.7
   285.2    2440   305.7 2442.65   313.9 2443.13   322.1 2445.03   338.7 2447.19
#Mann= 3 ,-1,0
       0      .1       0   137.6    .045       0   207.3      .1       0
Bank Sta=137.6,207.3
XS Rating Curve= 0 ,0
Exp/Cntr(USF)=0,0
Exp/Cntr=0.3,0.1

Type RM Length L Ch R = 1 ,29747   ,239.3,239.3,239.3
XS GIS Cut Line= 2
2375218.66539908707764.2224833242374952.68573061707514.763291158
#Sta/Elev= 30
       0  2495.1    12.4 2488.81    25.4 2483.99    63.3 2467.95    80.5 2459.52
    97.3 2450.41   119.9 2433.28   121.4 2432.62   133.1 2431.11   139.7 2428.21
   145.4 2424.93   150.6 2420.71   156.5 2419.57   170.9 2419.51   189.9 2419.81
   199.2 2420.68   204.8 2422.11   238.3 2425.17   250.2 2428.65   261.7 2433.71
   272.1 2439.46   284.1 2445.04   299.5 2455.28   309.5  2458.5   320.9 2464.01
   331.9 2470.29   343.6 2472.22   349.4 2475.13   360.5 2476.72   364.7 2478.38
#Mann= 3 ,-1,0
       0      .1       0   150.6    .045       0   199.2      .1       0
Bank Sta=150.6,199.2
XS Rating Curve= 0 ,0
Exp/Cntr(USF)=0,0
Exp/Cntr=0.3,0.1

Type RM Length L Ch R = 1 ,29508   ,278.7,278.7,278.7
XS GIS Cut Line= 2
2375317.78825689707656.8393873592375195.53673226707308.257337379
#Sta/Elev= 30
       0 2448.23    12.4 2443.51    46.3 2433.93    63.8  2431.9    88.9 2427.44
   101.4 2426.52   109.9 2424.24     114    2424   123.4 2422.14   139.5 2421.59
   156.5 2419.68   186.2 2417.91   198.9    2417   236.4 2415.89   245.5 2416.69
   248.9 2418.12     254 2420.41     274 2432.31   282.9 2438.93     296 2451.76
   299.1 2454.37   316.7 2467.44   321.8 2470.67   334.5 2480.76   339.9 2485.83
   347.2 2493.71   355.9 2500.08   359.9  2503.7     365 2509.72   369.4 2514.04
#Mann= 3 ,-1,0
       0      .1       0   186.2    .045       0   248.9      .1       0
Bank Sta=186.2,248.9
XS Rating Curve= 0 ,0
Exp/Cntr(USF)=0,0
Exp/Cntr=0.3,0.1

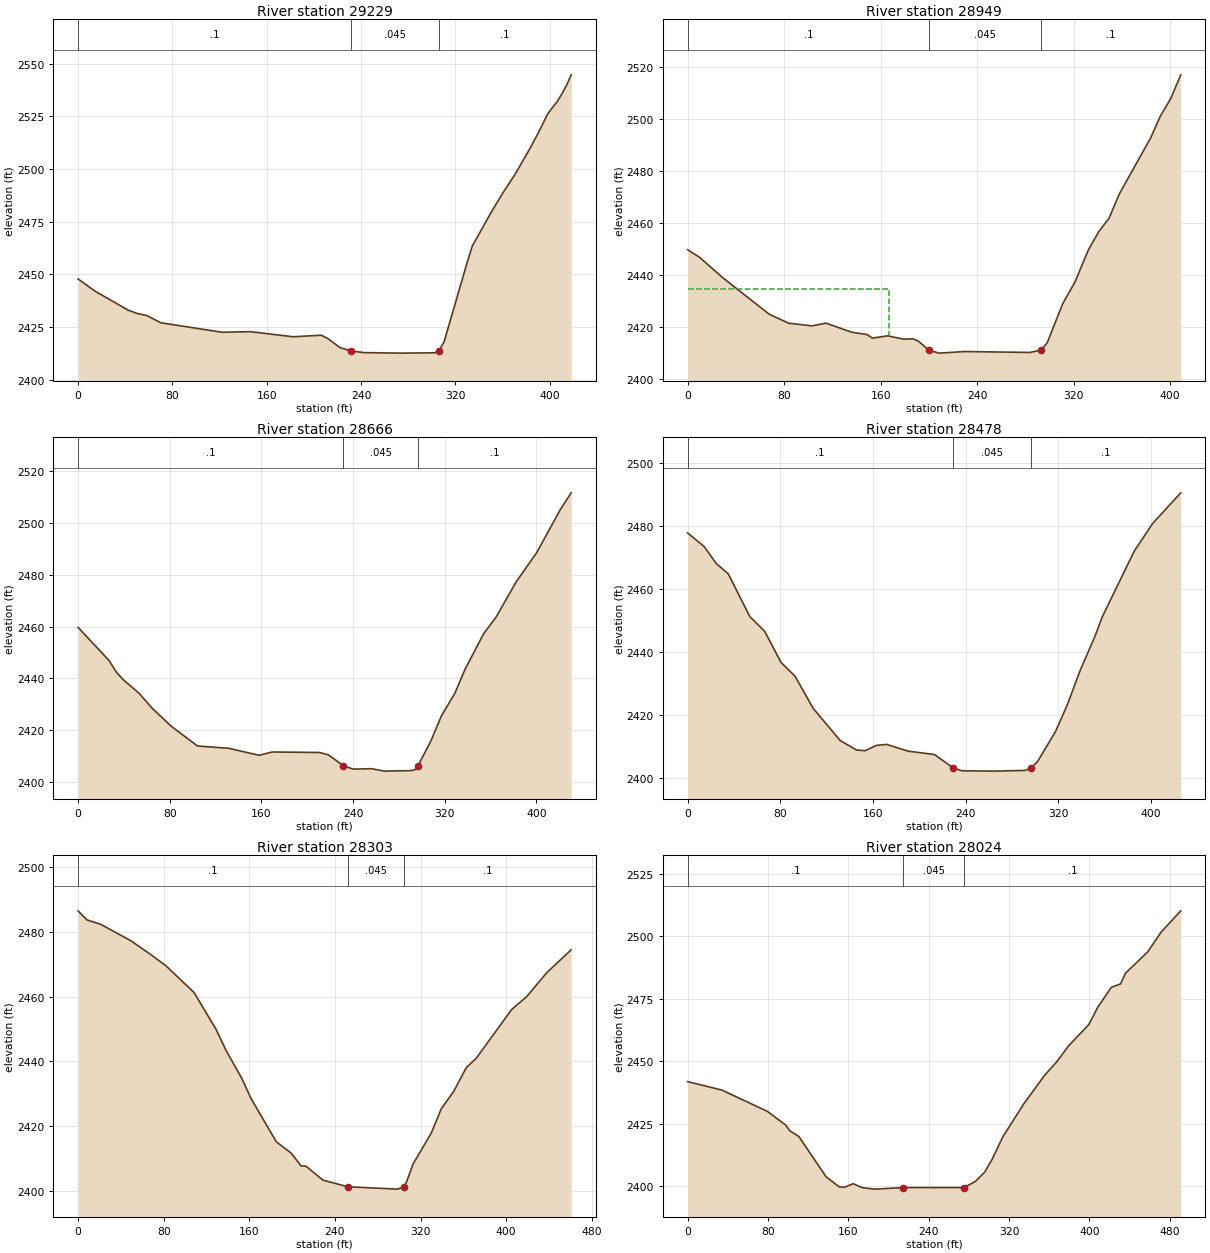
Type RM Length L Ch R = 1 ,29229   ,279.7,279.7,279.7
XS GIS Cut Line= 2
2375511.07782963707635.3627681662375501.16554385707217.394717716
#Sta/Elev= 30
       0 2447.85    14.2  2442.1    42.2 2433.09    50.2 2431.41    58.2 2430.47
    70.2 2427.01   122.2  2422.5   146.2 2422.79   182.2 2420.37   206.2 2421.11
   212.1 2419.41   222.2 2415.17   231.7 2413.63   242.3 2412.84   273.9  2412.6
   302.3 2412.75   305.9 2413.65   310.3 2417.91   330.3  2456.4   334.3 2463.52
   350.3  2479.5   360.6 2489.05   370.3 2497.32   382.3 2508.94   390.3 2517.27
   398.3 2526.34   406.3 2532.14   410.3 2535.78   414.3 2539.94   418.1 2544.76
#Mann= 3 ,-1,0
       0      .1       0   231.7    .045       0   305.9      .1       0
Bank Sta=231.7,305.9
XS Rating Curve= 0 ,0
Exp/Cntr(USF)=0,0
Exp/Cntr=0.3,0.1

Type RM Length L Ch R = 1 ,28949   ,283.8,283.8,283.8
XS GIS Cut Line= 2
2375683.05106668707652.6910129182375825.12716288707269.415962703
#Sta/Elev= 30
       0 2449.73     9.8 2446.85    29.3 2438.92    67.7 2424.98    83.8 2421.54
   103.2 2420.52   114.7 2421.57     136 2418.09   148.8  2417.2   153.1 2415.82
   165.9 2416.71   178.7 2415.45   187.1 2415.51   191.4 2414.64     200 2411.18
   208.5 2410.07   229.8 2410.68   283.7 2410.33     293 2411.23   298.1 2414.06
   310.9 2428.99   321.1 2437.34   332.2 2449.62   340.8 2456.64   349.3 2461.77
   357.8 2471.06   383.7 2492.48   391.9 2500.99   400.5 2507.72   408.8 2516.81
#Mann= 3 ,-1,0
       0      .1       0     200    .045       0     293      .1       0
#XS Ineff= 2 , 0
          167.33 2434.52
Permanent Ineff=
       F       F
Bank Sta=200,293
XS Rating Curve= 0 ,0
Exp/Cntr(USF)=0,0
Exp/Cntr=0.3,0.1

Type RM Length L Ch R = 1 ,28666   ,187.6,187.6,187.6
XS GIS Cut Line= 2
2375849.90787734707722.0770133872376140.66826026707404.883868382
#Sta/Elev= 30
       0 2459.71      27 2446.94    33.4 2442.47    39.2 2439.61    53.2 2434.32
    64.5 2428.58    81.5  2421.5   104.2 2413.95   131.4 2413.06     158 2410.35
   169.4 2411.63   210.5 2411.45   218.3 2410.56   231.6 2406.31     240 2405.03
   256.3 2405.19   267.1 2404.25     291 2404.45   294.2 2404.84   296.7 2406.38
     308    2416   317.1  2425.6   328.9 2434.39   337.6 2443.44   353.9 2457.27
   364.8  2463.7   382.2 2477.21     400 2488.41   421.2 2505.45   430.3 2511.62
#Mann= 3 ,-1,0
       0      .1       0   231.6    .045       0   296.7      .1       0
Bank Sta=231.6,296.7
XS Rating Curve= 0 ,0
Exp/Cntr(USF)=0,0
Exp/Cntr=0.3,0.1

Type RM Length L Ch R = 1 ,28478   ,175,175,175
XS GIS Cut Line= 2
 2375957.2909733707827.8080617232376282.74435646707553.568155103
#Sta/Elev= 30
       0 2477.73    14.2 2473.45    24.7 2468.04    35.1 2464.75    53.7 2451.19
    66.5 2446.54    80.6 2436.66    92.7 2432.28   108.4 2422.05   131.7 2411.86
   145.8 2408.85   153.1 2408.64   162.9 2410.32   171.7 2410.64   190.3  2408.5
     213 2407.43   228.7 2403.31   236.7 2402.26   265.3 2402.16   291.5 2402.39
   296.7 2403.29     302 2405.19   317.6 2414.77   328.1 2423.58   338.5 2433.86
   351.7 2445.07   357.9 2451.15   385.6 2472.07   401.3 2480.71   425.6 2490.47
#Mann= 3 ,-1,0
       0      .1       0   228.7    .045       0   296.7      .1       0
Bank Sta=228.7,296.7
XS Rating Curve= 0 ,0
Exp/Cntr(USF)=0,0
Exp/Cntr=0.3,0.1

Type RM Length L Ch R = 1 ,28303   ,278.9,278.9,278.9
XS GIS Cut Line= 2
2376018.08822785 707945.509222662376411.76382943 707705.99174974
#Sta/Elev= 30
       0 2486.49     8.3 2483.69    21.2 2482.32    49.3 2477.27    68.7  2472.8
      82 2469.56   108.4 2461.25   128.9 2449.93   138.2 2443.43   153.1 2434.69
   161.6 2428.54   185.3 2415.15   199.1 2411.68   208.4 2407.72   213.1 2407.61
   228.8 2403.33   252.1 2401.28   298.7 2400.55   304.2 2401.29   306.8 2402.65
   313.2 2408.39   330.2 2417.96   339.4 2425.36   351.1 2430.78   362.7 2438.03
   372.3 2441.06   405.1 2455.99   419.2 2459.99   437.9 2467.37   460.8 2474.47
#Mann= 3 ,-1,0
       0      .1       0   252.1    .045       0   304.2      .1       0
Bank Sta=252.1,304.2
XS Rating Curve= 0 ,0
Exp/Cntr=0.3,0.1

Type RM Length L Ch R = 1 ,28024   ,360.8,360.8,360.8
XS GIS Cut Line= 2
2376193.85115081708146.4285496932376629.46194189707919.810219071
#Sta/Elev= 30
       0 2441.86    34.2 2438.47    79.3 2429.98    97.3 2424.61   101.8 2422.17
   110.8 2419.88   137.9 2403.79   150.9 2399.76   155.9  2399.6   164.9 2401.02
     174 2399.43   186.5 2398.86   214.5 2399.49   275.5 2399.49   286.7 2402.01
   295.7 2405.61   303.3 2410.87   313.7 2419.69   334.8 2433.03   355.6 2444.48
   367.5 2449.78   379.3 2456.17   399.4 2464.66   408.4 2471.61   421.9  2479.6
     431 2480.95   436.1 2485.29     458 2493.71   471.5  2501.7     491 2510.18
#Mann= 3 ,-1,0
       0      .1       0   214.5    .045       0   275.5      .1       0
Bank Sta=214.5,275.5
XS Rating Curve= 0 ,0
Exp/Cntr(USF)=0,0
Exp/Cntr=0.3,0.1

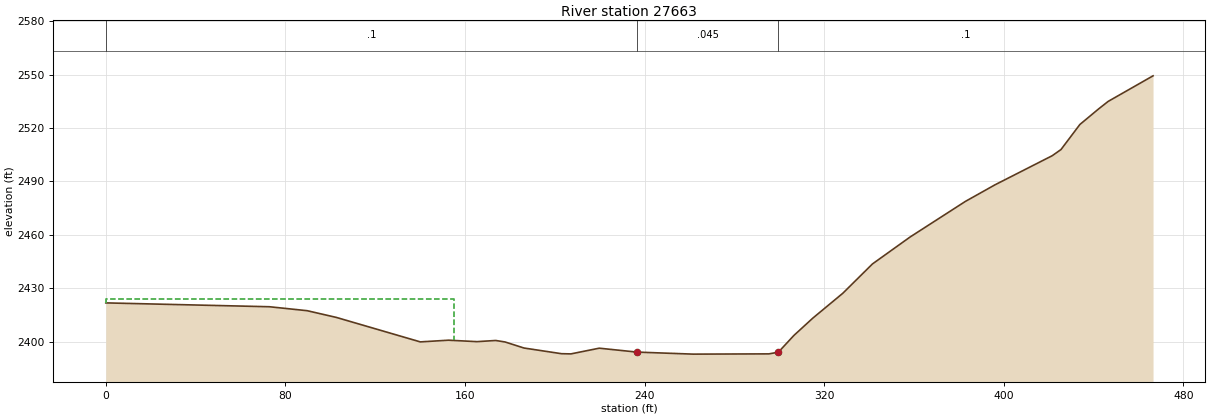
Type RM Length L Ch R = 1 ,27663   ,397.7,397.7,397.7
XS GIS Cut Line= 2
2376202.65821899708297.7808392012376647.22423629708439.030911586
#Sta/Elev= 30
       0 2421.72    72.9 2419.55    89.7 2417.33   102.7 2413.55   140.1 2399.79
   152.7 2400.74   165.3 2399.93   173.7 2400.58   177.9 2399.73   186.3 2396.34
     203 2393.15   207.2 2393.04   219.8 2396.25   236.6 2394.05   261.6 2392.91
   295.4 2393.05   299.6    2394   306.5 2403.39     315 2413.21   328.3 2427.12
   341.5 2443.61   358.3 2458.78   382.9 2478.77   396.1 2488.11   421.6 2504.48
   425.5 2507.95   433.9 2522.02   442.3 2530.83   446.5    2535   466.5 2549.39
#Mann= 3 ,-1,0
       0      .1       0   236.6    .045       0   299.6      .1       0
#XS Ineff= 2 , 0
          154.89  2424.1
Permanent Ineff=
       F       F
Bank Sta=236.6,299.6
XS Rating Curve= 0 ,0
Exp/Cntr(USF)=0,0
Exp/Cntr=0.3,0.1