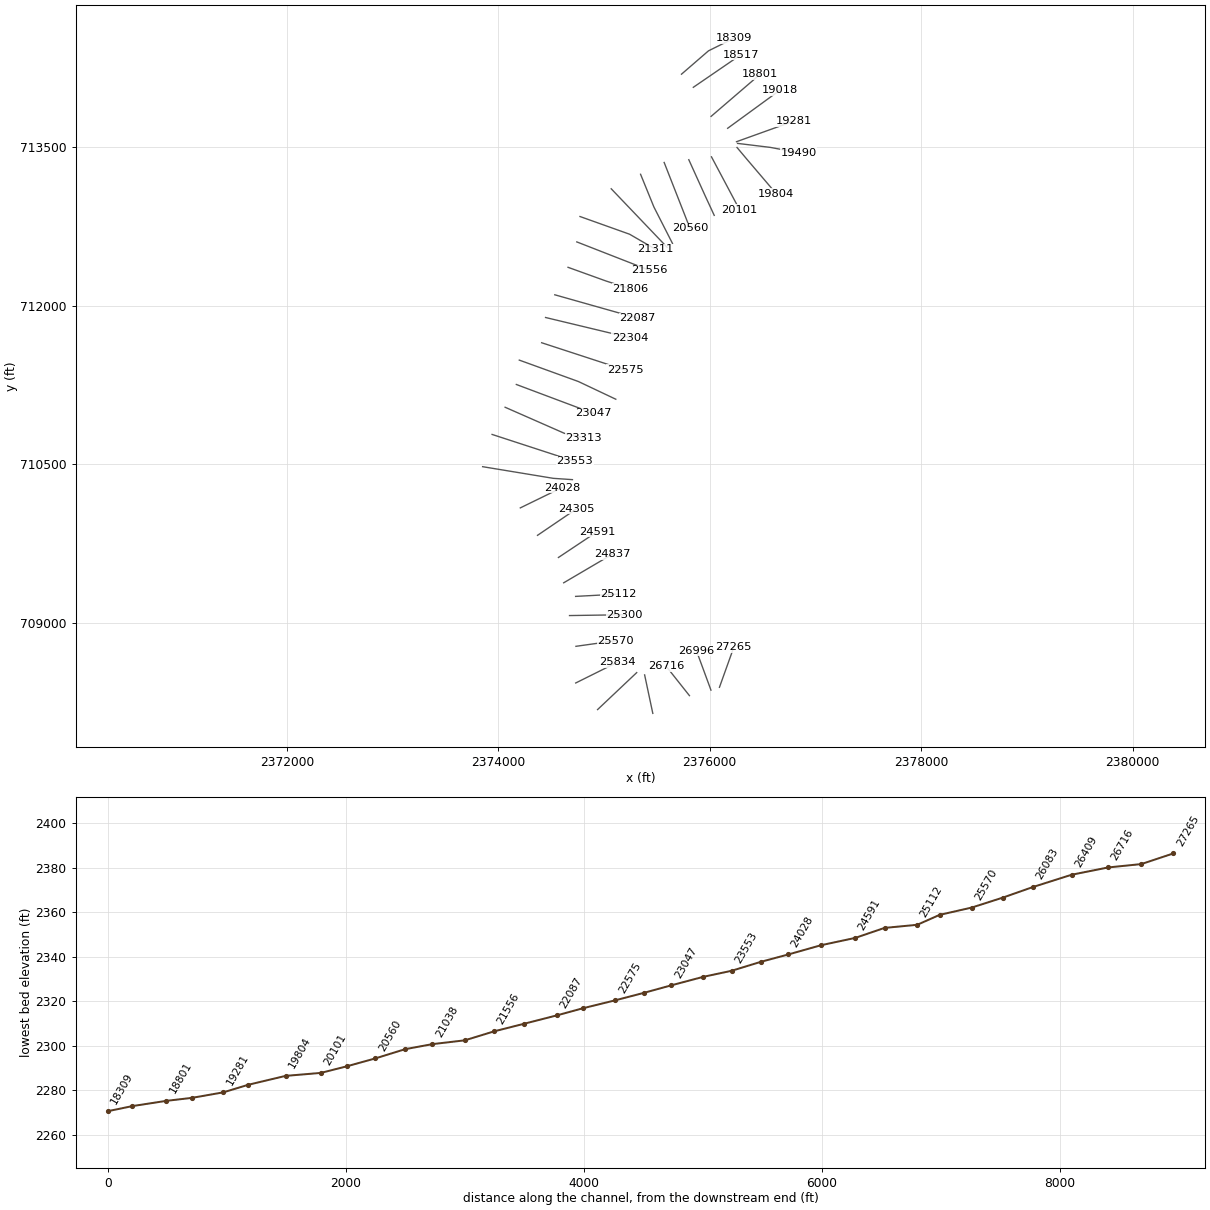
HEC-RAS study LAURELFK.prj: LAURELFK

--- LAURELFK.g01 (geometry) --- (continued)

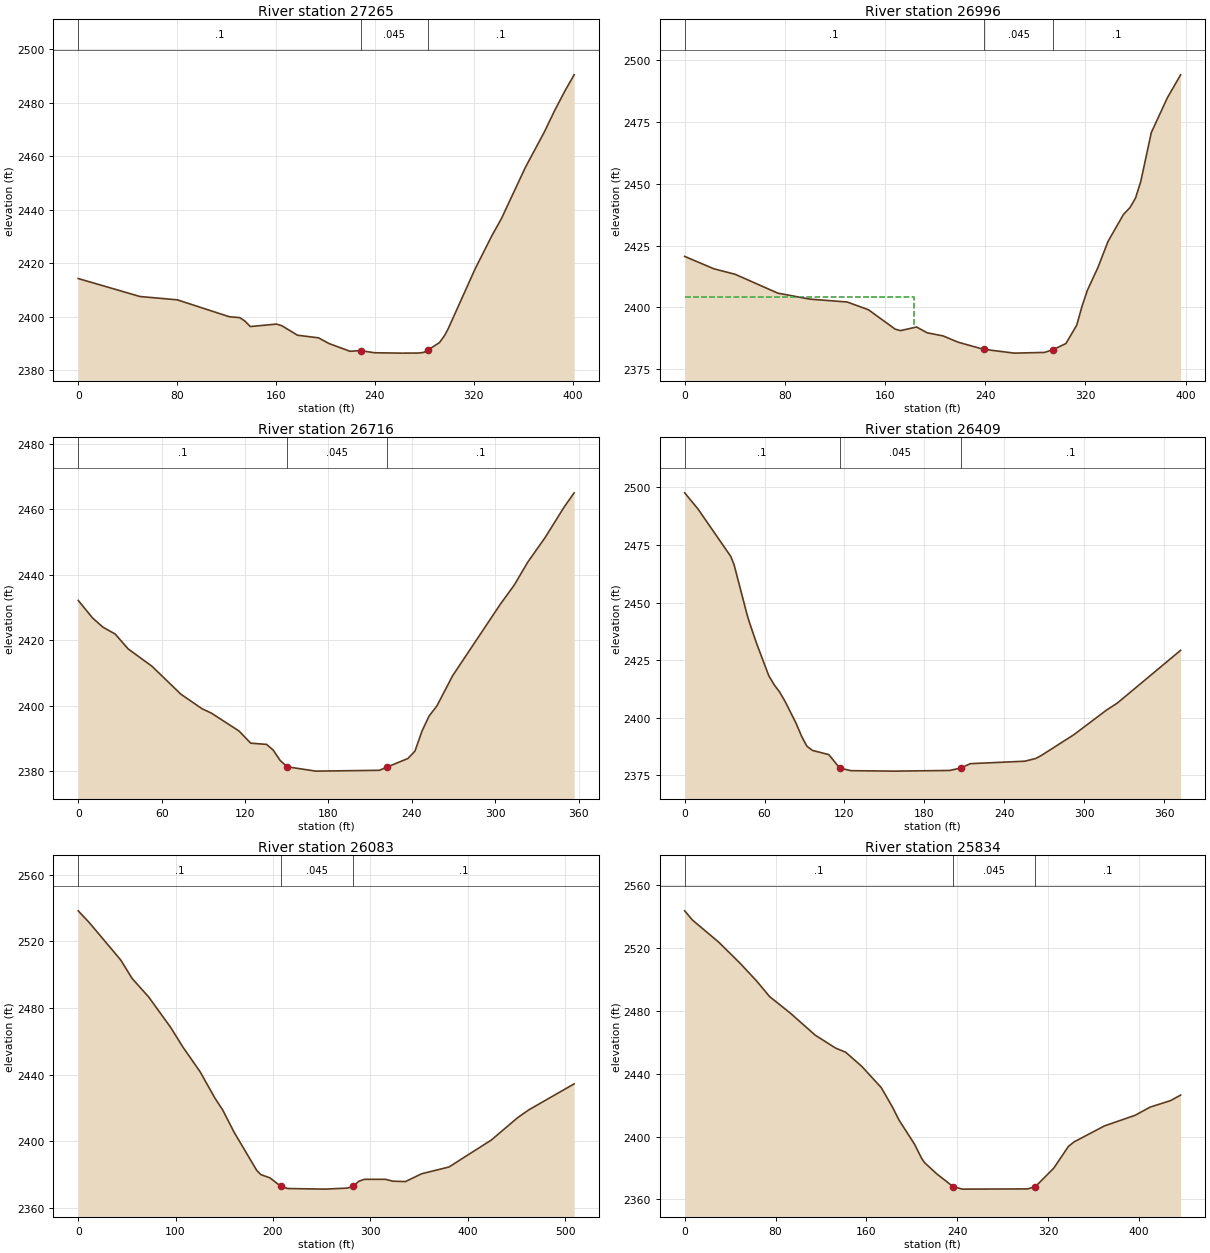
Type RM Length L Ch R = 1 ,27265   ,269.8,269.8,269.8
XS GIS Cut Line= 2
 2376092.7082172708390.1414060292376228.01091811708767.799494301
#Sta/Elev= 30
       0 2414.24      50 2407.52    80.2 2406.28   122.2 2399.97   130.7 2399.63
   134.9 2398.32   139.2  2396.3   160.4 2397.22   164.7 2396.62   177.4 2393.06
   194.4 2392.08   202.9 2389.95   219.9 2387.06   228.4 2387.31   239.7 2386.51
   261.6 2386.37   275.2  2386.4   279.4 2386.64   282.62387.444   292.2 2390.28
   296.4 2392.96   299.1 2395.28     321 2417.75   334.6 2430.21   342.4 2436.66
   361.7 2455.72   377.1 2469.01   385.6 2477.16   394.1 2484.65   401.2 2490.35
#Mann= 3 ,-1,0
       0      .1       0   228.4    .045       0   282.6      .1       0
Bank Sta=228.4,282.6
XS Rating Curve= 0 ,0
Exp/Cntr(USF)=0,0
Exp/Cntr=0.3,0.1

Type RM Length L Ch R = 1 ,26996   ,279.2,279.2,279.2
XS GIS Cut Line= 2
2376012.41870237708363.3782344192375875.62915858708735.088951222
#Sta/Elev= 30
       0 2420.63    23.4 2415.61    40.3 2413.41    74.4 2405.79     100 2403.38
   129.8 2402.22   146.8 2399.08   168.1 2391.27   172.4 2390.66   185.2 2392.13
   193.7 2389.79   206.5 2388.51   218.4 2385.99   238.7 2383.13   263.3 2381.58
   287.5 2381.87   294.5 2383.04   304.5 2385.45   313.1 2392.84   317.3 2400.38
   321.6 2406.91   330.1  2416.2   338.1 2426.66   350.5 2437.59   355.7 2440.35
   360.1  2444.2   364.2 2450.72   372.7 2470.62   385.5 2484.65   396.1 2493.93
#Mann= 3 ,-1,0
       0      .1       0   238.7    .045       0   294.5      .1       0
#XS Ineff= 2 , 0
          183.15 2404.42
Permanent Ineff=
       F       F
Bank Sta=238.7,294.5
XS Rating Curve= 0 ,0
Exp/Cntr(USF)=0,0
Exp/Cntr=0.3,0.1

Type RM Length L Ch R = 1 ,26716   ,307.2,307.2,307.2
XS GIS Cut Line= 2
2375808.72122956708311.3387340672375587.18164234708590.865193103
#Sta/Elev= 30
       0 2432.22    10.2 2426.91    17.7 2424.06    26.6 2421.94    35.9  2417.4
      53 2412.12    73.8 2403.58    89.1 2399.11    95.7  2397.8   115.6 2392.34
   124.1  2388.6   135.5 2388.23   140.2 2386.52   145.3 2383.29   150.4 2381.38
   170.8 2380.06   216.7 2380.31   221.8 2381.25   237.1 2383.91   242.2 2386.18
   247.3 2392.33   252.4 2396.91     258 2399.99   269.3 2409.21   303.5 2430.99
   313.7 2436.96   323.4 2443.96   335.8  2451.4   349.4 2460.67   356.7 2465.08
#Mann= 3 ,-1,0
       0      .1       0   150.4    .045       0   221.8      .1       0
Bank Sta=150.4,221.8
XS Rating Curve= 0 ,0
Exp/Cntr(USF)=0,0
Exp/Cntr=0.3,0.1

Type RM Length L Ch R = 1 ,26409   ,325.9,325.9,325.9
XS GIS Cut Line= 2
 2375462.2868415708143.325490072 2375384.9710124708507.601992539
#Sta/Elev= 30
       0 2497.68    10.1 2490.58    34.6 2470.06    37.1 2466.44    46.9 2444.67
    48.7 2441.27    53.9 2432.41    63.2 2418.17    67.4 2414.14    71.4 2411.07
    75.5 2406.96    83.7 2397.52    87.8 2391.92      91 2388.41    91.9 2387.56
    95.9 2385.79   108.2 2383.96   116.4 2378.13   124.8 2376.98   157.3 2376.78
     199 2377.07  207.532378.161   214.5 2380.02   255.4 2381.09   263.6 2382.27
   267.7 2383.54   292.2 2392.59     317  2403.4   324.9 2406.35   372.4 2429.27
#Mann= 3 ,-1,0
       0      .1       0   116.4    .045       0  207.53      .1       0
Bank Sta=116.4,207.53
XS Rating Curve= 0 ,0
Exp/Cntr(USF)=0,0
Exp/Cntr=0.3,0.1

Type RM Length L Ch R = 1 ,26083   ,249.8,249.8,249.8
XS GIS Cut Line= 2
2374939.89638803708179.1623085612375310.03966138  708529.1617303
#Sta/Elev= 30
       0 2538.37    11.4 2531.27    43.7 2508.83    55.4 2497.74    72.4 2486.63
      95 2468.33   107.7 2456.41   125.2 2441.74   140.3 2426.02   148.5  2418.7
   160.1 2405.45   183.4 2382.47   187.6 2379.96   196.9 2378.03   208.2 2372.92
   215.1 2371.62   253.6 2371.25   276.6 2371.87   282.4 2373.02   288.2 2375.95
     294 2377.15   315.7 2377.12   323.1 2376.02   336.2 2375.79   352.7 2380.47
   380.8 2384.53   424.3 2400.72   451.2 2414.08   462.8 2418.84   509.4 2434.47
#Mann= 3 ,-1,0
       0      .1       0   208.2    .045       0   282.4      .1       0
Bank Sta=208.2,282.4
XS Rating Curve= 0 ,0
Exp/Cntr(USF)=0,0
Exp/Cntr=0.3,0.1

Type RM Length L Ch R = 1 ,25834   ,263.1,263.1,263.1
XS GIS Cut Line= 2
2374733.22821593708431.0104569912375124.15791575708625.598143364
#Sta/Elev= 30
       0 2543.77     6.8 2537.94    30.1 2523.74    48.6 2510.54    63.5 2498.98
    74.8 2489.13    92.7 2478.84     115 2464.57   132.9 2456.36   141.8  2453.7
     156 2444.69   173.1 2431.19   182.8 2419.01   188.8 2410.45   202.4 2395.17
   208.8 2385.96   211.3 2383.37   222.2 2376.12   236.5 2368.07   244.6 2366.55
   302.1 2366.69   308.82368.153     325  2379.9   337.9 2393.76   342.9 2396.64
   369.7 2406.83   396.5 2413.53   409.9 2418.79   427.8  2422.9   436.7 2426.43
#Mann= 3 ,-1,0
       0      .1       0   236.5    .045       0   308.8      .1       0
Bank Sta=236.5,308.8
XS Rating Curve= 0 ,0
Exp/Cntr=0.3,0.1

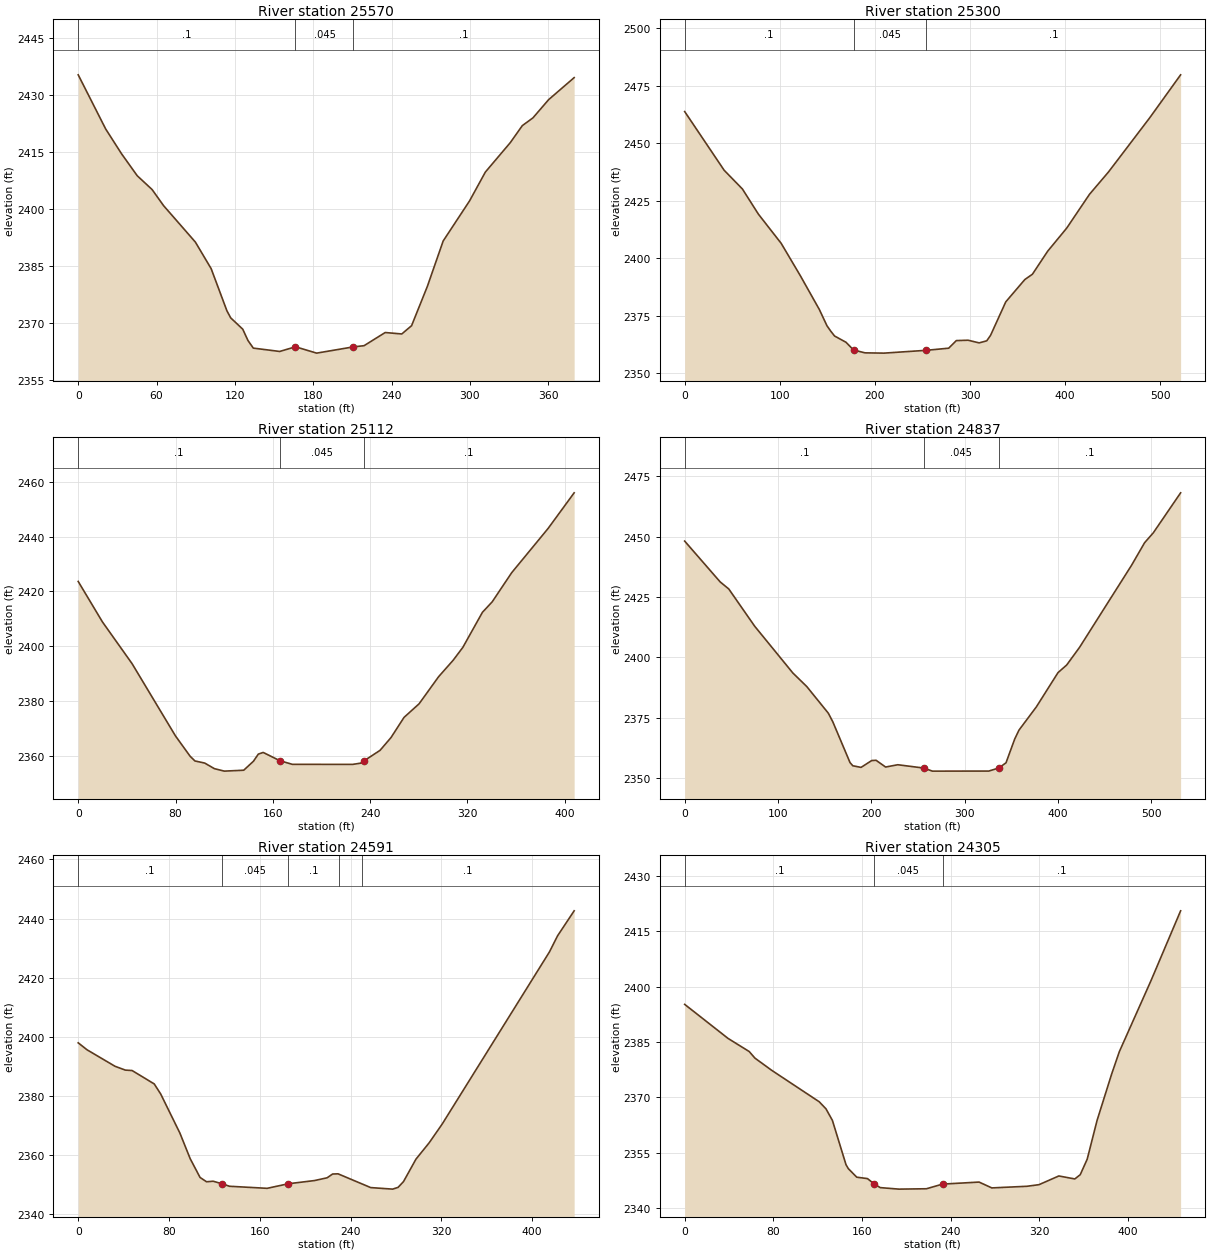
Type RM Length L Ch R = 1 ,25570   ,270.3,270.3,270.3
XS GIS Cut Line= 2
2374735.39599315708778.0458121792375111.53890131708830.892336466
#Sta/Elev= 30
       0  2435.4      21 2421.15    33.1 2414.64    45.2  2408.8    56.6 2405.16
    65.4 2400.91    89.7 2391.33   101.8 2384.32   113.9 2373.19   116.8 2371.34
     126 2368.36     130 2365.38   134.1 2363.37   154.3 2362.49   166.4 2363.72
   182.6 2362.05   210.8  2363.7   218.9 2364.01   235.1 2367.48   247.8  2367.1
   255.3 2369.28   267.4 2379.65   279.5 2391.61   299.7 2402.17   311.8 2409.77
   330.9 2417.53   340.1 2422.01   348.2 2424.04   360.3 2428.87   379.8 2434.66
#Mann= 3 ,-1,0
       0      .1       0   166.4    .045       0   210.8      .1       0
Bank Sta=166.4,210.8
XS Rating Curve= 0 ,0
Exp/Cntr(USF)=0,0
Exp/Cntr=0.3,0.1

Type RM Length L Ch R = 1 ,25300   ,187.8,187.8,187.8
XS GIS Cut Line= 2
 2374674.6393353709069.1367618482375195.95695497709076.952095379
#Sta/Elev= 30
       0 2463.77    41.5 2438.26    60.7 2430.11    77.5 2419.18   101.5 2406.46
   121.5 2392.48   141.6 2377.71   149.6 2370.65   153.6  2368.3   157.6  2366.2
   169.6 2363.48   177.6  2360.1   189.6 2358.88   209.6 2358.76   253.6 2359.97
   277.6 2360.91   285.6 2364.21     298 2364.37   309.6 2363.21   317.6 2364.12
   321.6  2366.5   337.6 2381.06   357.6 2390.74   365.6 2393.06   381.6 2403.05
   401.6 2413.08   425.6  2427.8   445.6 2437.52   488.9 2461.05   521.4 2479.74
#Mann= 3 ,-1,0
       0      .1       0   177.6    .045       0   253.6      .1       0
Bank Sta=177.6,253.6
XS Rating Curve= 0 ,0
Exp/Cntr=0.3,0.1

Type RM Length L Ch R = 1 ,25112   ,274.8,274.8,274.8
XS GIS Cut Line= 2
2374732.28737407709250.5559116932375139.51647299709272.316245223
#Sta/Elev= 30
       0 2423.67    19.9 2408.89    44.2 2393.67      80 2367.17      92 2359.76
      96 2358.02     104 2357.26     112 2355.21   120.1 2354.31   136.1 2354.64
   144.1 2357.93   148.1 2360.53   152.1 2361.14   165.9  2358.1   176.1 2356.79
   225.6 2356.77   232.2 2357.22  235.252358.135   248.2 2361.91   257.2 2366.58
   267.9 2373.95   280.3 2378.93   296.3 2388.81   308.3 2394.85   316.3 2399.59
   332.4  2412.4   340.4 2416.21   356.4 2426.85   386.4 2443.06   407.8 2456.08
#Mann= 3 ,-1,0
       0      .1       0   165.9    .045       0  235.25      .1       0
Bank Sta=165.9,235.25
XS Rating Curve= 0 ,0
Exp/Cntr(USF)=0,0
Exp/Cntr=0.3,0.1

Type RM Length L Ch R = 1 ,24837   ,246.3,246.3,246.3
XS GIS Cut Line= 2
2374619.41733117709379.2139508342375077.40918899709648.704141591
#Sta/Elev= 30
       0 2448.13      38 2431.25    47.3 2428.29      75  2412.9   115.9 2393.54
   130.8 2387.93   153.9  2376.9   158.7 2373.35   177.2 2356.42   180.2 2355.12
     189 2354.46   200.4 2357.29   205.1 2357.39   215.3  2354.6   228.3 2355.55
   256.3 2354.18   265.4 2352.91   325.8 2352.93  336.472354.187   344.3 2356.35
   353.6 2366.16   358.2 2369.88   376.8 2379.49     400 2393.67   409.3 2396.83
   423.2  2404.2   478.9 2438.16   492.8 2447.46   502.1 2451.54   531.4 2468.11
#Mann= 3 ,-1,0
       0      .1       0   256.3    .045       0  336.47      .1       0
Bank Sta=256.3,336.47
XS Rating Curve= 0 ,0
Exp/Cntr=0.3,0.1

Type RM Length L Ch R = 1 ,24591   ,286.4,286.4,286.4
XS GIS Cut Line= 2
2374569.65314621 709618.821482572374933.36157807709861.293770479
#Sta/Elev= 30
       0 2397.94     7.8 2395.58    32.4 2390.01    41.5 2388.71    47.5 2388.56
      67 2384.03    72.7 2380.62    89.6 2367.41    98.7 2358.72   107.4 2352.37
   113.1 2350.91   118.9  2351.1   126.8 2350.23   133.3 2349.39   166.5 2348.69
   185.2 2350.24   208.3 2351.32   219.4 2352.26   224.2 2353.53     229  2353.6
   257.8 2348.94   277.1 2348.42   281.9 2349.01   286.7 2350.97   297.7 2358.58
   309.3 2364.09   320.8 2370.45   415.3 2428.69   422.5 2434.17   437.1 2442.62
#Mann= 5 ,-1,0
       0      .1       0   126.8    .045       0   185.2      .1       0
     230     .08       0     250      .1       0
Bank Sta=126.8,185.2
XS Rating Curve= 0 ,0
Exp/Cntr(USF)=0,0
Exp/Cntr=0.3,0.1

Type RM Length L Ch R = 1 ,24305   ,276.3,276.3,276.3
XS GIS Cut Line= 2
2374371.74876362709828.4750011812374741.92890639710080.172001182
#Sta/Elev= 30
       0 2395.24    39.2    2386    58.2 2382.46    63.4 2380.67    78.6 2377.35
   121.4 2368.84   127.5 2366.93   133.3 2363.81   145.6 2351.78   147.7  2350.7
   155.3 2348.39     165    2348  171.112346.536   176.5 2345.56   193.3 2345.15
   218.2 2345.25   232.7 2346.51   265.7 2347.06   277.2 2345.48   308.9 2345.92
   319.8 2346.36   337.7 2348.72   352.1 2347.91     357 2349.06   363.3 2353.28
   372.2 2363.78   385.4 2376.39   392.3 2382.42     421 2401.76   447.6  2420.6
#Mann= 3 ,-1,0
       0      .1       0  171.11    .045       0   232.7      .1       0
Bank Sta=171.11,232.7
XS Rating Curve= 0 ,0
Exp/Cntr=0.3,0.1

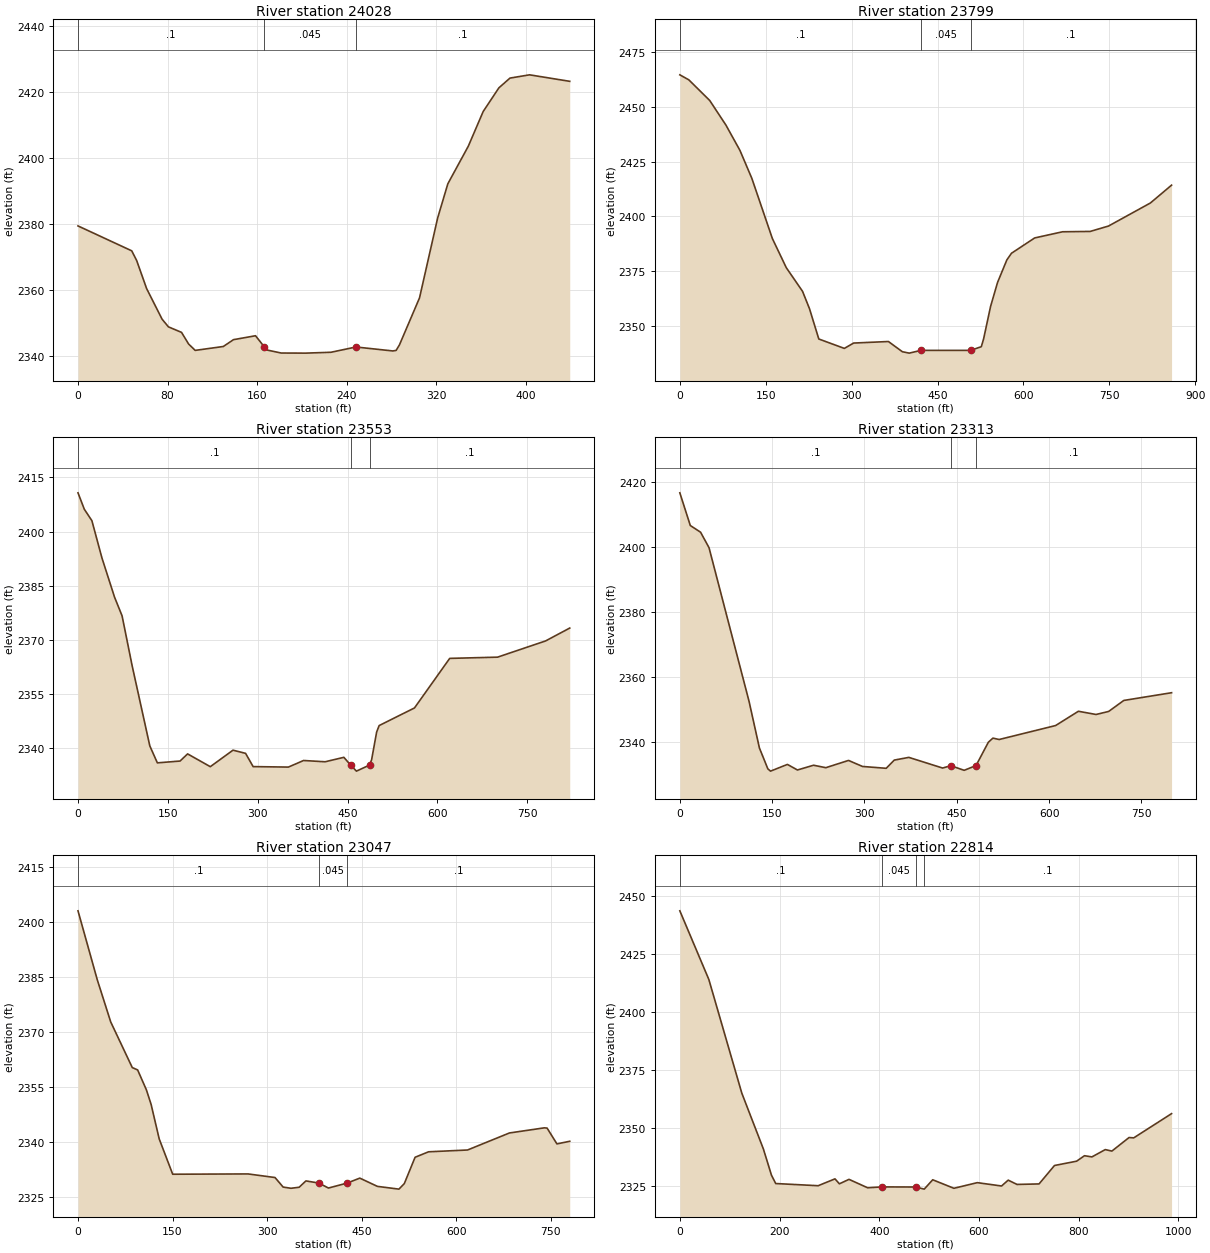
Type RM Length L Ch R = 1 ,24028   ,229.6,229.6,229.6
XS GIS Cut Line= 2
2374209.05333342710088.2229630082374603.84795604710280.957345705
#Sta/Elev= 30
       0 2379.54      48 2371.99    52.4 2369.06    61.3 2360.55    75.1 2351.28
    80.8 2348.94    92.5 2347.27    98.8 2343.75   104.7 2341.81   129.8 2342.99
   138.9 2345.06   158.6 2346.25   166.3 2342.94   168.2 2341.97   181.5 2341.01
   203.4 2340.98     226 2341.24   248.3 2342.84   281.2 2341.64   284.2  2341.8
   287.2  2343.5   305.1 2357.72   321.3 2381.94   330.4 2392.31   348.7 2403.71
     362 2414.23     376 2421.39   385.9 2424.35   403.4 2425.34   439.3 2423.37
#Mann= 3 ,-1,0
       0      .1       0   166.3    .045       0   248.3      .1       0
Bank Sta=166.3,248.3
XS Rating Curve= 0 ,0
Exp/Cntr(USF)=0,0
Exp/Cntr=0.3,0.1

Type RM Length L Ch R = 1 ,23799   ,245.4,245.4,245.4
XS GIS Cut Line= 3
2373852.71623756710478.2139046212374521.28304917710367.911904621
2374702.08247512710355.643237561
#Sta/Elev= 30
       0 2464.54    15.7 2462.25    52.2 2452.84    80.5 2441.63   104.9 2430.13
   125.7 2417.39   161.6 2389.92   185.9 2376.64   214.3 2365.86   226.5  2357.9
   242.7 2344.13   287.3 2339.84   303.5 2342.28   364.3 2342.98   388.6 2338.33
   400.6 2337.69   421.1 2338.95   507.9 2338.95   526.5 2340.62   530.5 2344.15
   542.7 2358.98   554.9 2369.92   571.1 2380.17   579.2 2383.21   619.7 2390.19
   668.4    2393   716.7 2393.16   748.7 2395.62   821.8 2406.12   858.8 2414.25
#Mann= 3 ,-1,0
       0      .1       0   421.1    .045       0   507.9      .1       0
Bank Sta=421.1,507.9
XS Rating Curve= 0 ,0
Exp/Cntr=0.3,0.1

Type RM Length L Ch R = 1 ,23553   ,239.9,239.9,239.9
XS GIS Cut Line= 2
2373942.15907831710783.4194946142374722.73332823 710528.82359231
#Sta/Elev= 30
       0 2410.71    10.5 2406.18    23.2 2402.99      40 2392.67      61 2381.84
    73.6 2376.65    90.5 2362.76   119.9 2340.65   132.5 2335.96   170.4 2336.46
     183 2338.44   220.9  2334.9   258.8 2339.47   279.8 2338.59   292.4 2334.92
   351.3 2334.79   376.6 2336.61   412.6 2336.26   443.9 2337.49   455.5 2335.28
   464.9 2333.67   486.7 2335.34   490.2 2336.81   498.6 2344.48   502.8 2346.28
   561.8 2351.16   620.6 2364.88   700.5 2365.22   780.7 2369.71     821 2373.27
#Mann= 3 ,-1,0
       0      .1       0   455.5    .045       0   486.7      .1       0
Bank Sta=455.5,486.7
XS Rating Curve= 0 ,0
Exp/Cntr(USF)=0,0
Exp/Cntr=0.3,0.1

Type RM Length L Ch R = 1 ,23313   ,266.3,266.3,266.3
XS GIS Cut Line= 3
     2374065.292      711040.7182374626.55747748710793.782999409
2374807.92218958710753.220762439
#Sta/Elev= 30
       0 2416.76      17 2406.68    33.7 2404.61    47.4 2399.85   112.4  2352.5
   129.3 2338.07     143 2331.63   147.4 2330.93   174.8    2333   191.1 2331.28
   217.3 2332.75   237.2 2331.99   274.1 2334.23   296.8 2332.37   335.3  2331.8
   348.4 2334.33   372.1 2335.17     427 2331.88   440.2  2332.6     462 2331.18
   481.3 2332.65   501.3 2339.84   508.7 2341.11   518.8 2340.68   610.6 2344.99
   647.6 2349.39   676.3  2348.4   696.8 2349.34   721.4 2352.73     799 2355.11
#Mann= 3 ,-1,0
       0      .1       0   440.2    .045       0   481.3      .1       0
Bank Sta=440.2,481.3
XS Rating Curve= 0 ,0
Exp/Cntr=0.3,0.1

Type RM Length L Ch R = 1 ,23047   ,233.3,233.3,233.3
XS GIS Cut Line= 2
 2374171.5751661711256.2404560352374901.78978699710982.060253554
#Sta/Elev= 30
       0 2402.98    30.5 2384.24    51.9  2372.7    86.1 2360.27    94.6 2359.63
   108.5  2354.2     116 2350.22   128.8 2340.84   150.2 2331.21   269.8 2331.29
   312.5 2330.31   325.4 2327.71   337.9 2327.38   350.8 2327.66   361.5 2329.39
   381.8 2328.81   397.3 2327.45   426.8 2328.79     447 2330.15   474.9  2327.9
   509.1 2327.15   517.6 2328.66   534.7 2335.83   556.1 2337.32   617.9 2337.81
   684.3 2342.45   739.8 2343.85   744.1 2343.78   759.7 2339.47     780 2340.19
#Mann= 3 ,-1,0
       0      .1       0   381.8    .045       0   426.8      .1       0
Bank Sta=381.8,426.8
XS Rating Curve= 0 ,0
Exp/Cntr(USF)=0,0
Exp/Cntr=0.3,0.1

Type RM Length L Ch R = 1 ,22814   ,238.4,238.4,238.4
XS GIS Cut Line= 3
2374199.34519076711486.9298572272374758.24695379711284.304237561
2375112.37847689 711116.71490403
#Sta/Elev= 30
       0 2443.61    58.2 2414.02   124.3 2365.07   167.5 2341.07   183.8 2329.73
   192.3 2326.14   277.4  2325.2   311.2 2328.15     320 2326.02   339.3 2327.94
   376.7 2324.31   405.6 2324.68   473.2 2324.64   490.2 2323.73   507.2 2327.76
   549.7 2324.09   596.6 2326.52   645.3 2325.08   658.6  2327.6   676.3 2325.75
   720.5 2325.97   751.5 2333.91   795.8 2335.76   811.6 2338.12   826.6 2337.61
   853.3 2340.76   866.6 2340.12     901 2345.95   910.4 2345.81   986.3 2356.25
#Mann= 4 ,-1,0
       0      .1       0   405.6    .045       0   473.2     .08       0
     490      .1       0
Bank Sta=405.6,473.2
XS Rating Curve= 0 ,0
Exp/Cntr=0.3,0.1

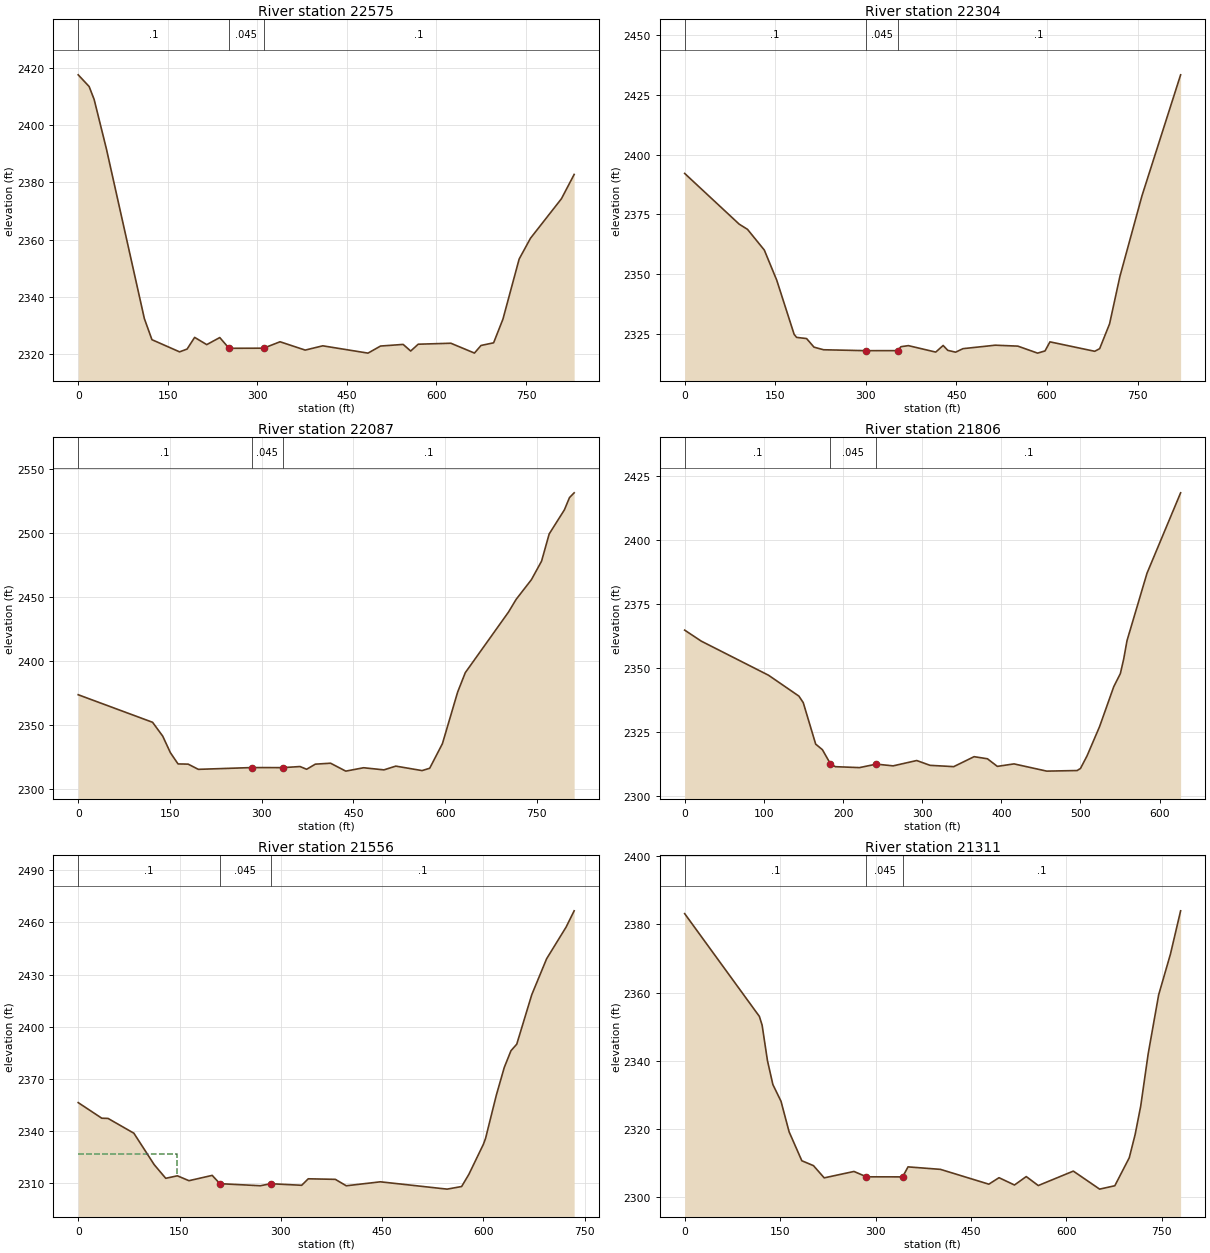
Type RM Length L Ch R = 1 ,22575   ,271.3,271.3,271.3
XS GIS Cut Line= 2
2374410.81449333 711651.321413382375200.40373857711393.306030093
#Sta/Elev= 30
       0  2417.5    18.3 2413.42    26.7  2408.9    47.2 2391.69   110.8 2332.45
   123.5  2325.1   169.8 2320.85   182.4 2321.83     195  2325.9   215.3 2323.38
   237.1 2325.84  252.682322.094  310.462322.132   338.1 2324.37   380.2 2321.47
   409.6 2322.96   485.4 2320.41   506.4 2322.88   544.3 2323.45   556.9 2321.14
   569.5 2323.52   624.2 2323.86   663.7 2320.43   674.7 2323.08   695.8 2324.01
   711.4 2332.26   738.6 2353.24   757.6  2360.5   809.4 2374.27   830.7 2382.74
#Mann= 3 ,-1,0
       0      .1       0  252.68    .045       0  310.46      .1       0
Bank Sta=252.68,310.46
XS Rating Curve= 0 ,0
Exp/Cntr(USF)=0,0
Exp/Cntr=0.3,0.1

Type RM Length L Ch R = 1 ,22304   ,217.6,217.6,217.6
XS GIS Cut Line= 2
 2374447.8896425711890.2641920312375246.61721195711698.404596016
#Sta/Elev= 30
       0 2392.09    90.3 2370.85     104 2368.69   131.9 2360.01   152.5 2347.38
   181.3 2324.71   185.4 2323.44   201.9 2322.95   214.2 2319.35     230 2318.26
   299.7 2317.88   352.7 2317.89   358.2 2319.54   370.5 2319.99   415.8 2317.28
   428.1 2320.06   435.7 2318.02   448.7 2317.25     461 2318.72   514.5 2320.17
   551.8 2319.78   584.5 2316.85   596.8 2317.77     605 2321.57   679.1 2317.62
   687.3 2318.72   703.7 2329.08   720.9 2349.02   757.4 2382.73   821.4 2433.38
#Mann= 3 ,-1,0
       0      .1       0   299.7    .045       0   352.7      .1       0
Bank Sta=299.7,352.7
XS Rating Curve= 0 ,0
Exp/Cntr=0.3,0.1

Type RM Length L Ch R = 1 ,22087   ,280.1,280.1,280.1
XS GIS Cut Line= 2
2374535.15925636 712105.179798442375315.42264437711884.467844062
#Sta/Elev= 30
       0 2373.45   121.6 2351.89   138.2 2341.04   150.7 2328.12   163.2 2319.31
   179.8 2319.14   196.4 2315.06   283.7 2316.45   334.6 2316.41   362.7 2317.26
   373.5 2315.12   387.7 2319.12   412.6 2319.86   437.5 2313.67   466.6 2316.31
   499.9 2314.66   519.3 2317.59   562.2 2314.09   574.7 2315.92   595.5 2335.15
   620.4 2375.52   632.9 2390.72   703.6 2438.19   716.1 2448.14     741 2463.49
   757.6 2477.98   770.1 2499.31     795 2518.19   803.3 2527.76   810.9 2531.47
#Mann= 3 ,-1,0
       0      .1       0   283.7    .045       0   334.6      .1       0
Bank Sta=283.7,334.6
XS Rating Curve= 0 ,0
Exp/Cntr(USF)=0,0
Exp/Cntr=0.3,0.1

Type RM Length L Ch R = 1 ,21806   ,250.5,250.5,250.5
XS GIS Cut Line= 3
 2374660.4786645712365.2141129192375020.98686853712235.180370973
2375252.61153791712160.988018549
#Sta/Elev= 30
       0 2364.78    20.9  2360.5     106 2347.19   144.3 2339.07   149.8 2336.52
   165.5 2320.36     174 2318.19   184.2 2312.64   190.4 2311.57   220.8 2311.21
   242.1 2312.57   263.3 2311.89   293.1 2313.97   310.1 2312.09   339.9 2311.59
   365.6 2315.47   382.4 2314.66     395 2311.69     416 2312.66   457.4 2309.84
   495.8 2310.07     500 2310.89   508.3 2315.79   524.2 2327.25     542 2342.72
   550.4 2347.87   554.6 2353.54   558.8  2360.7     584 2386.92   626.5 2418.28
#Mann= 3 ,-1,0
       0      .1       0   184.2    .045       0   242.1      .1       0
Bank Sta=184.2,242.1
XS Rating Curve= 0 ,0
Exp/Cntr=0.3,0.1

Type RM Length L Ch R = 1 ,21556   ,244.7,244.7,244.7
XS GIS Cut Line= 2
2374743.43673443712605.667469636 2375427.3329311712338.326229121
#Sta/Elev= 30
       0 2356.26    34.9 2347.28    44.2 2347.15    82.4 2338.65   112.5 2320.54
   129.6 2312.68   146.8 2314.12     164 2311.31   198.4 2314.36  209.792309.586
   269.6  2308.4     285 2309.56   330.9 2308.66   340.6  2312.4   380.7 2312.08
   396.9 2308.38   447.4 2310.66   546.2 2306.45   567.7 2307.95   578.4 2314.95
   599.8 2332.17   603.1 2335.63   619.2 2360.74   630.8 2376.46   640.7  2386.1
   649.3 2389.89   671.5 2418.34   693.5 2439.06   722.3 2457.26   734.3 2466.68
#Mann= 3 ,-1,0
       0      .1       0  209.79    .045       0     285      .1       0
#XS Ineff= 2 , 0
          146.89 2326.47
Permanent Ineff=
       F       F
Bank Sta=209.79,285
XS Rating Curve= 0 ,0
Exp/Cntr(USF)=0,0
Exp/Cntr=0.3,0.1

Type RM Length L Ch R = 1 ,21311   ,272.9,272.9,272.9
XS GIS Cut Line= 3
2374773.61399837 712845.98527823 2375242.6797016712678.399463716
2375486.06887016712537.283666124
#Sta/Elev= 30
       0 2383.16   117.4 2353.05   121.7 2350.49   130.1 2340.09   138.6 2333.09
   151.4 2328.18   164.1 2319.24   184.1 2310.76   202.4 2309.32   219.3 2305.74
   266.1 2307.62  285.632306.046   342.5 2306.03     351 2308.96     402 2308.23
     478 2303.89     494 2305.79   518.3 2303.65   536.8 2306.12   555.7 2303.49
   610.8 2307.72   652.1 2302.44     676 2303.43   698.7 2311.64   707.9 2318.43
   716.7 2326.78   728.4 2342.06   744.9 2359.38   763.4  2371.3   779.4 2383.99
#Mann= 3 ,-1,0
       0      .1       0  285.63    .045       0   342.5      .1       0
Bank Sta=285.63,342.5
XS Rating Curve= 0 ,0
Exp/Cntr=0.3,0.1

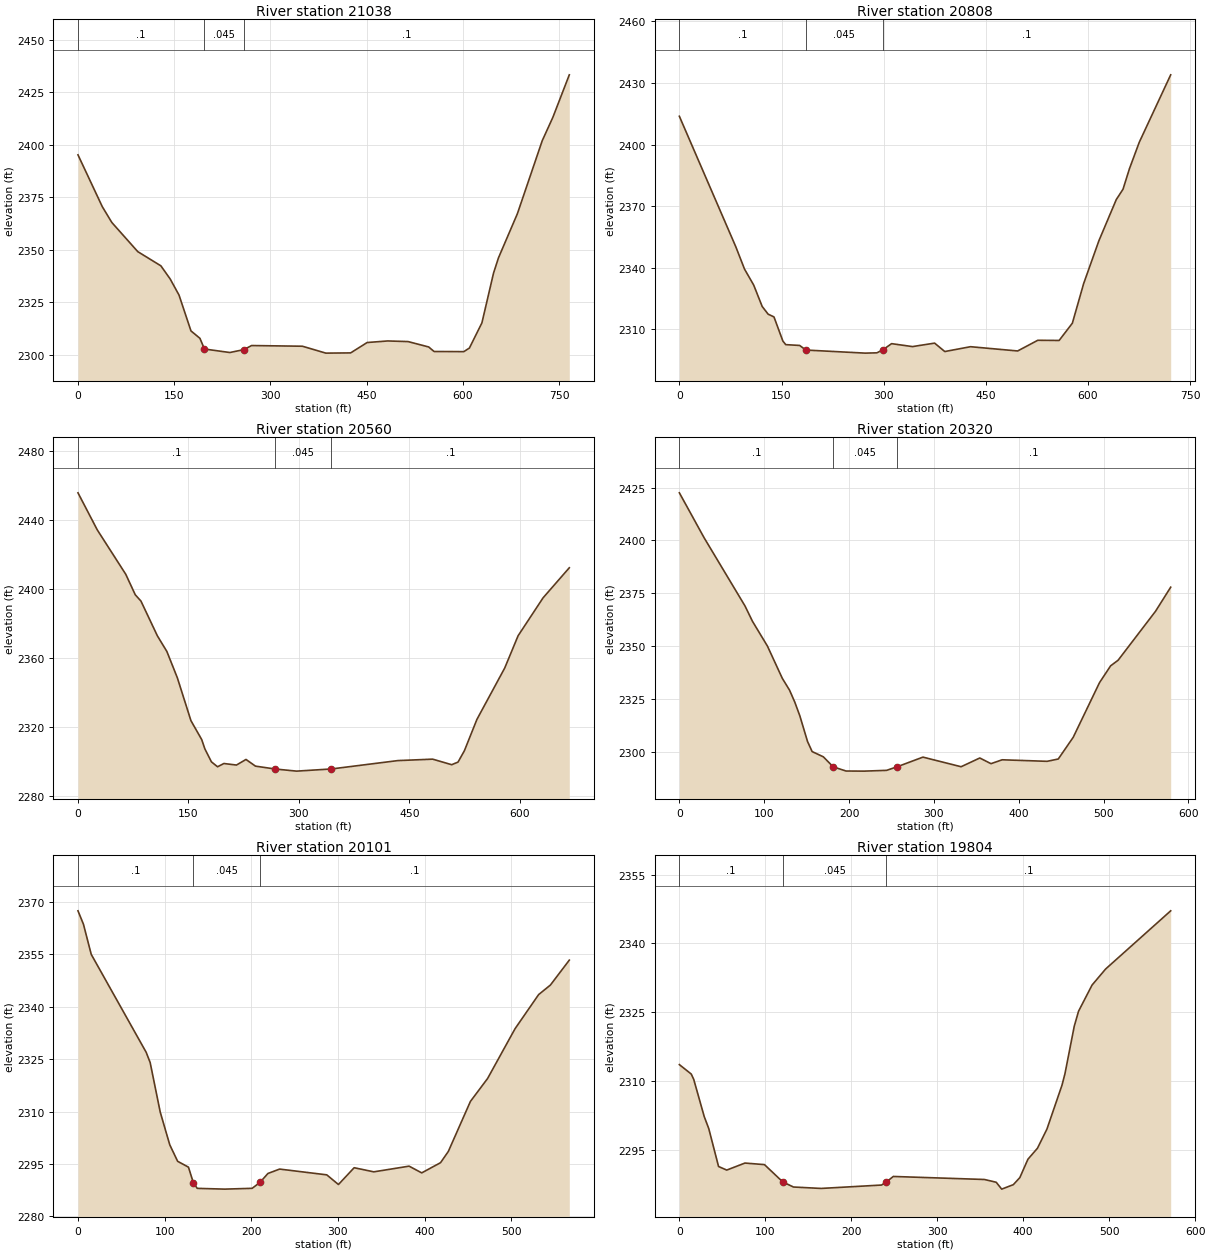
Type RM Length L Ch R = 1 ,21038   ,229.8,229.8,229.8
XS GIS Cut Line= 2
2375068.94809824713108.5751351612375597.72420303712554.619215862
#Sta/Elev= 30
       0  2395.2    37.9  2370.5    52.8 2362.96    93.2 2349.08   129.2 2342.32
   143.7 2336.06   157.5 2328.37   176.1 2311.31   190.1 2307.77   197.1 2302.68
   236.7 2301.01  258.452302.385   270.6 2304.33   349.8 2304.01   386.3 2300.72
     425 2300.83   450.7 2305.77   482.8 2306.52   514.5 2306.22   546.6 2303.66
     555  2301.5   601.4 2301.43   610.1 2303.15   629.6 2315.15   647.7 2338.84
   655.4 2346.11   684.9 2367.17   723.6 2401.93   740.2 2413.09   765.8 2433.33
#Mann= 3 ,-1,0
       0      .1       0   197.1    .045       0  258.45      .1       0
Bank Sta=197.1,258.45
XS Rating Curve= 0 ,0
Exp/Cntr(USF)=0,0
Exp/Cntr=0.3,0.1

Type RM Length L Ch R = 1 ,20808   ,248.6,248.6,248.6
XS GIS Cut Line= 3
2375346.69679597713245.8274838912375472.81975887712935.947537911
2375648.41948064 712591.28387016
#Sta/Elev= 30
       0 2413.78    82.8 2350.29    95.7 2339.34   109.1 2331.62   121.6 2321.17
   130.3 2317.43   138.9 2316.08     152 2304.32   156.2 2302.58   176.6 2302.19
   185.8 2299.95   272.8 2298.45     290 2298.59   298.7 2300.04   311.6 2303.06
   342.2 2301.63   374.8 2303.32   389.7 2299.22   427.5 2301.58   496.7  2299.5
   526.2  2304.7   557.6 2304.62     577 2313.01   593.6 2332.31     616 2353.18
   641.5 2373.21   651.4 2378.26   660.9 2388.29   675.2 2401.07   721.4 2433.96
#Mann= 3 ,-1,0
       0      .1       0   185.8    .045       0   298.7      .1       0
Bank Sta=185.8,298.7
XS Rating Curve= 0 ,0
Exp/Cntr=0.3,0.1

Type RM Length L Ch R = 1 ,20560   ,240.2,240.2,240.2
XS GIS Cut Line= 2
2375569.74663134713357.5755231282375813.15150497712736.473431793
#Sta/Elev= 30
       0 2455.91    26.2 2434.39    64.9 2408.61    77.8  2396.7    85.5 2393.07
   107.8 2372.88   120.7 2363.79   134.9 2348.54   153.4  2323.6     168 2312.65
   172.3 2307.23   181.2 2299.71   189.5 2296.86   198.1 2298.75   215.2 2297.86
   228.1 2301.11     241 2297.23  267.782295.552   296.9 2294.33   344.1 2295.59
   434.2 2300.44   481.6 2301.28   507.4 2298.06     516 2299.56   524.6 2306.12
   541.7 2324.39   579.4 2354.18   597.6 2372.94   631.5 2394.95   667.1  2412.4
#Mann= 3 ,-1,0
       0      .1       0  267.78    .045       0   344.1      .1       0
Bank Sta=267.78,344.1
XS Rating Curve= 0 ,0
Exp/Cntr(USF)=0,0
Exp/Cntr=0.3,0.1

Type RM Length L Ch R = 1 ,20320   ,218.2,218.2,218.2
XS GIS Cut Line= 3
2375802.74529515713383.7045580862375958.45479503713040.130171836
2376043.32796128712856.924411324
#Sta/Elev= 30
       0 2422.55    29.1 2401.32    77.4 2368.95    86.2 2361.69   103.8 2349.98
   121.3 2334.74   129.9 2329.08     136 2323.49     142 2316.94   151.1 2304.76
   156.5 2300.02   169.7 2297.54   181.3 2292.81   196.4 2290.82     218 2290.77
   244.3 2291.14   256.8 2292.85   287.1  2297.4   332.1 2292.85   354.1 2296.99
   367.3  2294.3   380.5 2296.14   433.4 2295.41   446.6 2296.51   464.2 2306.78
   495.2 2332.66   508.3 2340.63   517.1 2343.27   561.2 2366.45   579.1 2377.86
#Mann= 3 ,-1,0
       0      .1       0   181.3    .045       0   256.8      .1       0
Bank Sta=181.3,256.8
XS Rating Curve= 0 ,0
Exp/Cntr=0.3,0.1

Type RM Length L Ch R = 1 ,20101   ,297,297,297
XS GIS Cut Line= 2
2376017.38777825713410.7329093242376283.17470923 712909.93437622
#Sta/Elev= 30
       0  2367.5     6.3 2363.67    15.3 2355.03    78.7 2326.99    83.3 2324.06
    94.9 2309.89   105.9 2300.52     115 2295.78   127.5  2294.1   133.1 2289.67
   137.6 2288.03   169.3 2287.81     201 2288.04   210.1 2289.75   219.2 2292.29
   232.7 2293.55   287.1  2291.9   300.6 2289.13   318.7 2293.94   341.4 2292.76
   382.1 2294.39   396.7 2292.46   418.4 2295.38   427.4  2298.6   452.9 2312.93
   472.7 2319.49   504.4 2333.75   531.6 2343.51   545.2 2346.25     567 2353.38
#Mann= 3 ,-1,0
       0      .1       0   133.1    .045       0   210.1      .1       0
Bank Sta=133.1,210.1
XS Rating Curve= 0 ,0
Exp/Cntr(USF)=0,0
Exp/Cntr=0.3,0.1

Type RM Length L Ch R = 1 ,19804   ,314.1,314.1,314.1
XS GIS Cut Line= 3
2376258.82757214713499.3395509392376353.64047607713386.458904974
 2376628.7200007713063.527095965
#Sta/Elev= 30
       0 2313.59    13.8 2311.54    16.7 2310.38    28.9 2302.28    34.2 2299.65
    45.6 2291.39    55.1 2290.61    76.3 2292.14      99  2291.8   120.3 2288.03
   132.7 2286.92   164.9 2286.61   235.2 2287.35   240.9 2288.03   248.9 2289.22
   354.9 2288.56   368.6 2287.96     375 2286.46   388.5 2287.43   396.1 2288.97
   405.5 2292.97   416.6 2295.37   427.6 2299.53   445.2 2309.14   448.6 2311.61
   459.4 2321.95   464.4 2325.22   480.1 2330.92   495.9 2334.42   571.6  2347.1
#Mann= 3 ,-1,0
       0      .1       0   120.3    .045       0   240.9      .1       0
Bank Sta=120.3,240.9
XS Rating Curve= 0 ,0
Exp/Cntr=0.3,0.1

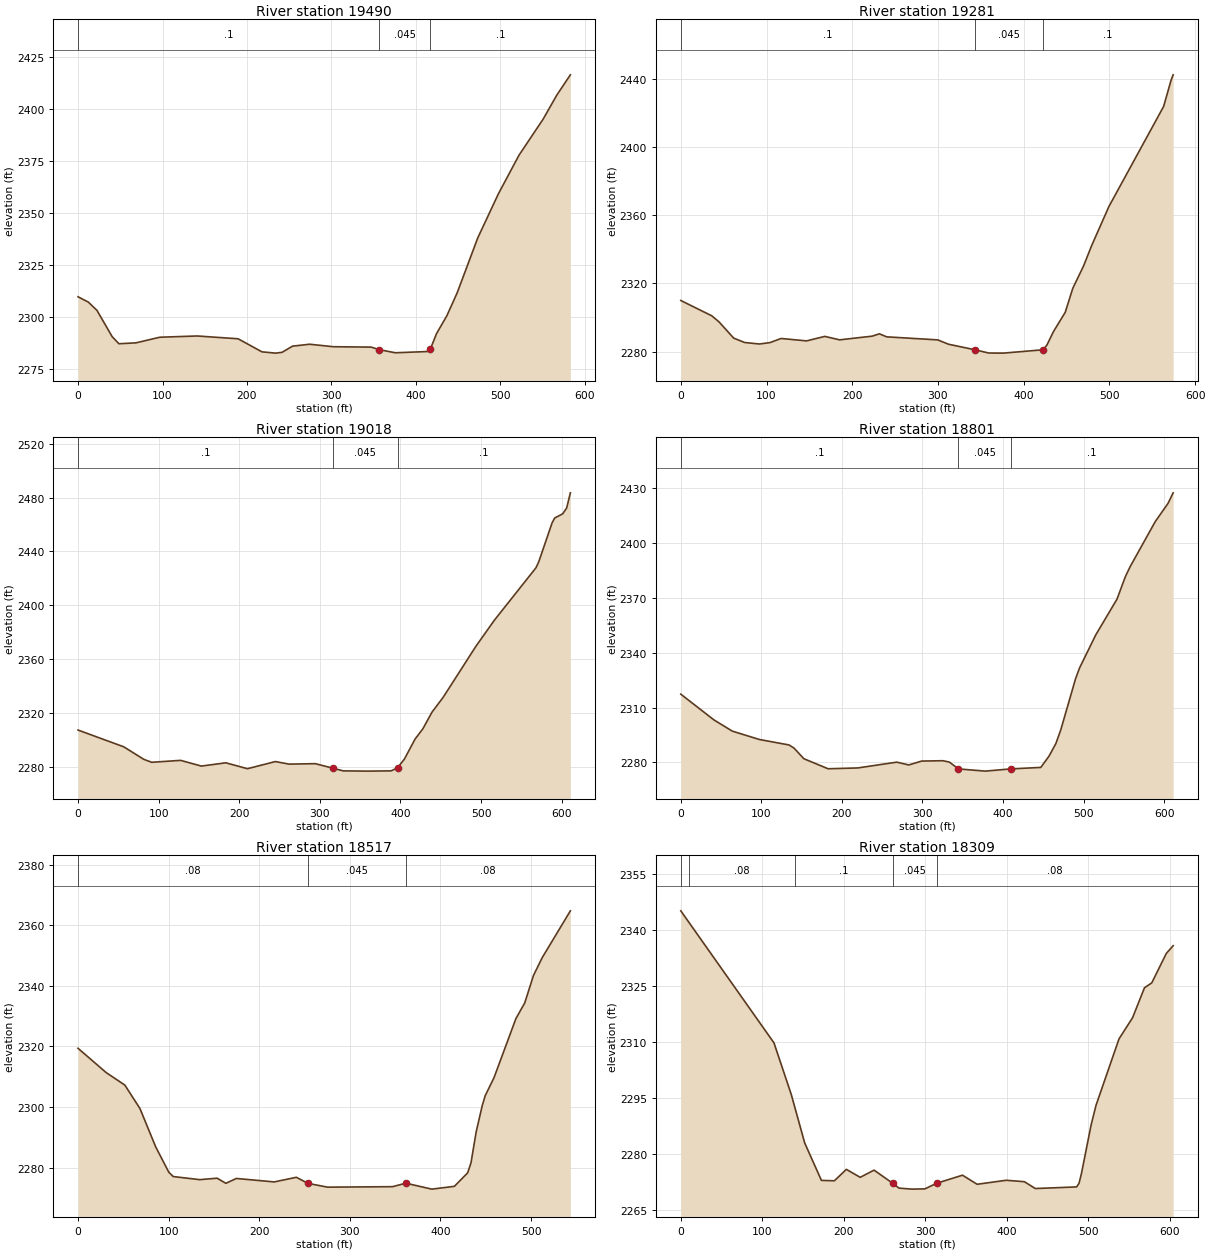
Type RM Length L Ch R = 1 ,19490   ,209,209,209
XS GIS Cut Line= 3
2376264.10474728713538.0425062482376574.14145472713500.261138705
 2376839.9283857713449.901509678
#Sta/Elev= 30
       0 2309.58    12.2 2307.02    22.4 2303.05    40.4  2290.4    48.4 2286.98
    68.6 2287.41    96.8 2290.12   141.1 2290.72   189.5 2289.37   217.7 2283.09
   233.8 2282.47   241.5 2282.85   253.9 2285.82   274.1 2286.75   302.3 2285.55
     347 2285.36   356.2 2284.18   375.5 2282.64   412.1 2283.21   416.2 2283.51
  417.012284.388   424.3  2291.8   436.6 2300.48   448.7 2311.38   473.2 2337.94
   497.6 2359.12     522 2377.71   550.5 2395.02   566.8 2406.65   582.8 2416.36
#Mann= 3 ,-1,0
       0      .1       0   356.2    .045       0  417.01      .1       0
Bank Sta=356.2,417.01
XS Rating Curve= 0 ,0
Exp/Cntr(USF)=0,0
Exp/Cntr=0.3,0.1

Type RM Length L Ch R = 1 ,19281   ,263.1,263.1,263.1
XS GIS Cut Line= 2
2376254.11988061713554.0978236162376794.58432911713748.466206946
#Sta/Elev= 30
       0 2309.94    36.2 2300.94    44.6  2297.4    61.7 2287.88    74.4 2285.31
    91.8 2284.42   104.1 2285.25     117 2287.66   146.7 2286.25     168 2288.88
   185.3 2286.86   223.2 2289.02   231.7 2290.39   240.2 2288.62   299.7 2286.84
   312.5 2284.27   342.72281.078   359.3 2279.13   376.1 2279.07   422.8 2281.04
   427.3 2283.94   434.6 2291.57   448.5    2303   457.3 2317.07   469.8 2330.11
   479.2 2342.01   499.5  2365.1   563.3 2423.76   571.8 2438.84   574.4  2442.3
#Mann= 3 ,-1,0
       0      .1       0   342.7    .045       0   422.8      .1       0
Bank Sta=342.7,422.8
XS Rating Curve= 0 ,0
Exp/Cntr=0.3,0.1

Type RM Length L Ch R = 1 ,19018   ,217.4,217.4,217.4
XS GIS Cut Line= 2
2376170.34190035713681.1605949512376663.86626481714041.231942495
#Sta/Elev= 30
       0 2307.16    56.7  2294.7    81.5 2285.41    91.4 2283.17   127.3 2284.61
   153.1 2280.35   183.3 2282.79   210.2  2278.4   244.9 2283.72   261.8 2281.81
   294.4 2282.15   316.2 2278.79   329.1 2276.78   359.7  2276.6   388.5  2276.8
   396.4 2279.04     405  2285.6   418.2 2300.47   427.9 2308.12   439.3 2320.57
   452.9 2331.38   493.7 2369.48   516.6 2388.87   568.2 2427.86   571.7 2432.36
   588.2 2461.28   591.5 2464.91   601.4 2468.02   606.3 2472.36   610.9 2483.62
#Mann= 3 ,-1,0
       0      .1       0   316.2    .045       0   396.4      .1       0
Bank Sta=316.2,396.4
XS Rating Curve= 0 ,0
Exp/Cntr(USF)=0,0
Exp/Cntr=0.3,0.1

Type RM Length L Ch R = 1 ,18801   ,283.3,283.3,283.3
XS GIS Cut Line= 2
2376013.55756466 713793.630684122376476.98319805714192.103464823
#Sta/Elev= 30
       0  2317.3    41.2 2303.22    63.9 2297.11    97.5 2292.53   134.3 2289.55
   140.6 2287.82   152.7 2282.04   182.8 2276.53   219.7 2276.98   268.2 2280.15
     283 2278.61   298.9 2280.73   325.2 2280.93   333.4 2280.18   344.7 2276.45
     378 2275.24   409.7 2276.46   446.9 2277.27   457.1 2283.44   465.6  2290.3
   471.7  2297.8   490.1 2325.82   495.1 2331.72   515.2 2349.75   541.5 2369.25
   551.8 2381.43   557.6 2386.82     589 2411.63   604.8 2421.55   611.2 2427.34
#Mann= 3 ,-1,0
       0      .1       0   344.7    .045       0   409.7      .1       0
Bank Sta=344.7,409.7
XS Rating Curve= 0 ,0
Exp/Cntr=0.3,0.1

Type RM Length L Ch R = 1 ,18517   ,208.4,208.4,208.4
XS GIS Cut Line= 2
2375845.52229312 714068.929738462376293.72299146714376.123475526
#Sta/Elev= 30
       0  2319.4    30.9 2311.42    51.7 2307.24    68.3 2299.54    85.7 2286.87
   100.2 2278.48   105.1 2277.05   134.4 2276.03   153.5 2276.51   163.2 2274.82
   174.7 2276.42   216.6 2275.28     241 2276.81   253.72274.804   275.4 2273.55
   347.1 2273.71   361.7 2274.86   390.5  2272.9   415.4 2273.83     430 2278.27
   433.7 2281.56   439.4 2291.77   446.2 2300.57   449.4 2303.75   459.1 2309.69
   483.3 2329.22     493 2334.37   502.7 2343.47   512.4 2349.38   543.4 2364.79
#Mann= 3 ,-1,0
       0     .08       0   253.7    .045       0   361.7     .08       0
Bank Sta=253.7,361.7
XS Rating Curve= 0 ,0
Exp/Cntr(USF)=0,0
Exp/Cntr=0.3,0.1

Type RM Length L Ch R = 1 ,18309   ,242.9,242.9,242.9
XS GIS Cut Line= 3
2375733.73503274714193.1949312732375988.87411621714414.034932899
 2376227.6403355714532.461500813
#Sta/Elev= 30
       0  2345.1   114.3 2309.75   135.5 2295.95     152 2282.95   172.5 2272.93
   188.4 2272.82   203.1 2275.88   220.1 2273.75   237.1 2275.68   260.3  2272.1
   267.7 2270.86   283.6 2270.59   299.5 2270.66   313.7 2272.15   345.6 2274.32
   363.5 2271.89   399.2 2272.96   421.5 2272.58   434.9 2270.75   485.5 2271.18
   488.5 2272.12   491.5 2274.76   503.4 2287.82   509.4 2293.05   537.6 2310.82
   554.2 2316.47   568.8 2324.49   577.8 2325.82   595.6 2333.69     604 2335.76
#Mann= 5 ,-1,0
       0      .1       0      10     .08       0     140      .1       0
   260.3    .045       0   313.7     .08       0
Bank Sta=260.3,313.7
XS Rating Curve= 0 ,0
Exp/Cntr=0.3,0.1