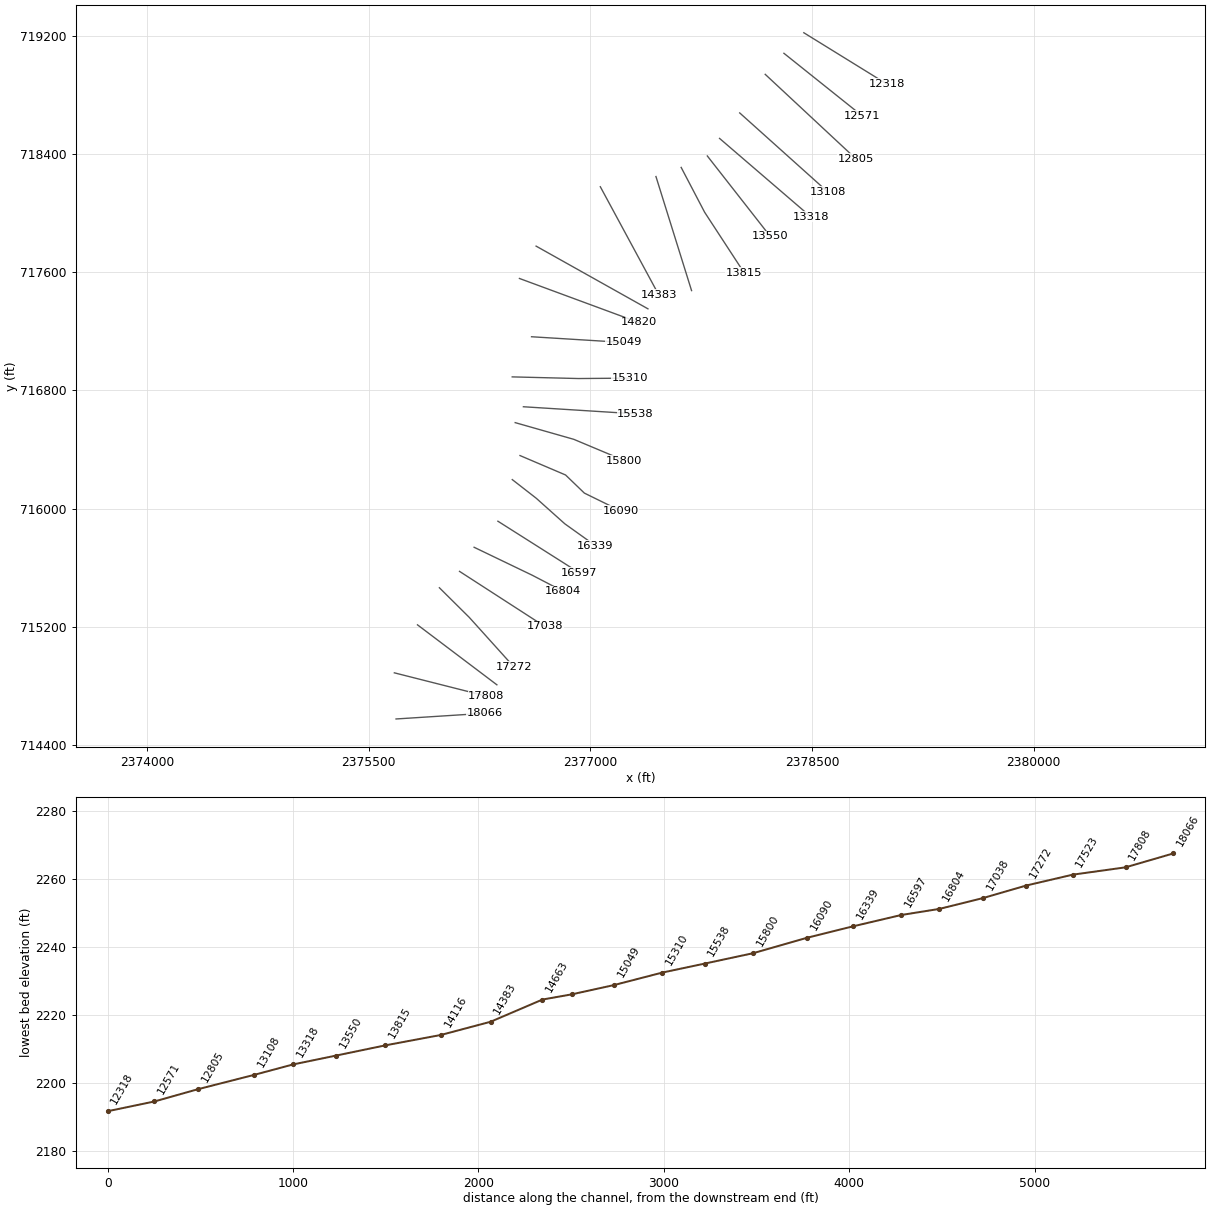
HEC-RAS study LAURELFK.prj: LAURELFK

--- LAURELFK.g01 (geometry) --- (continued)

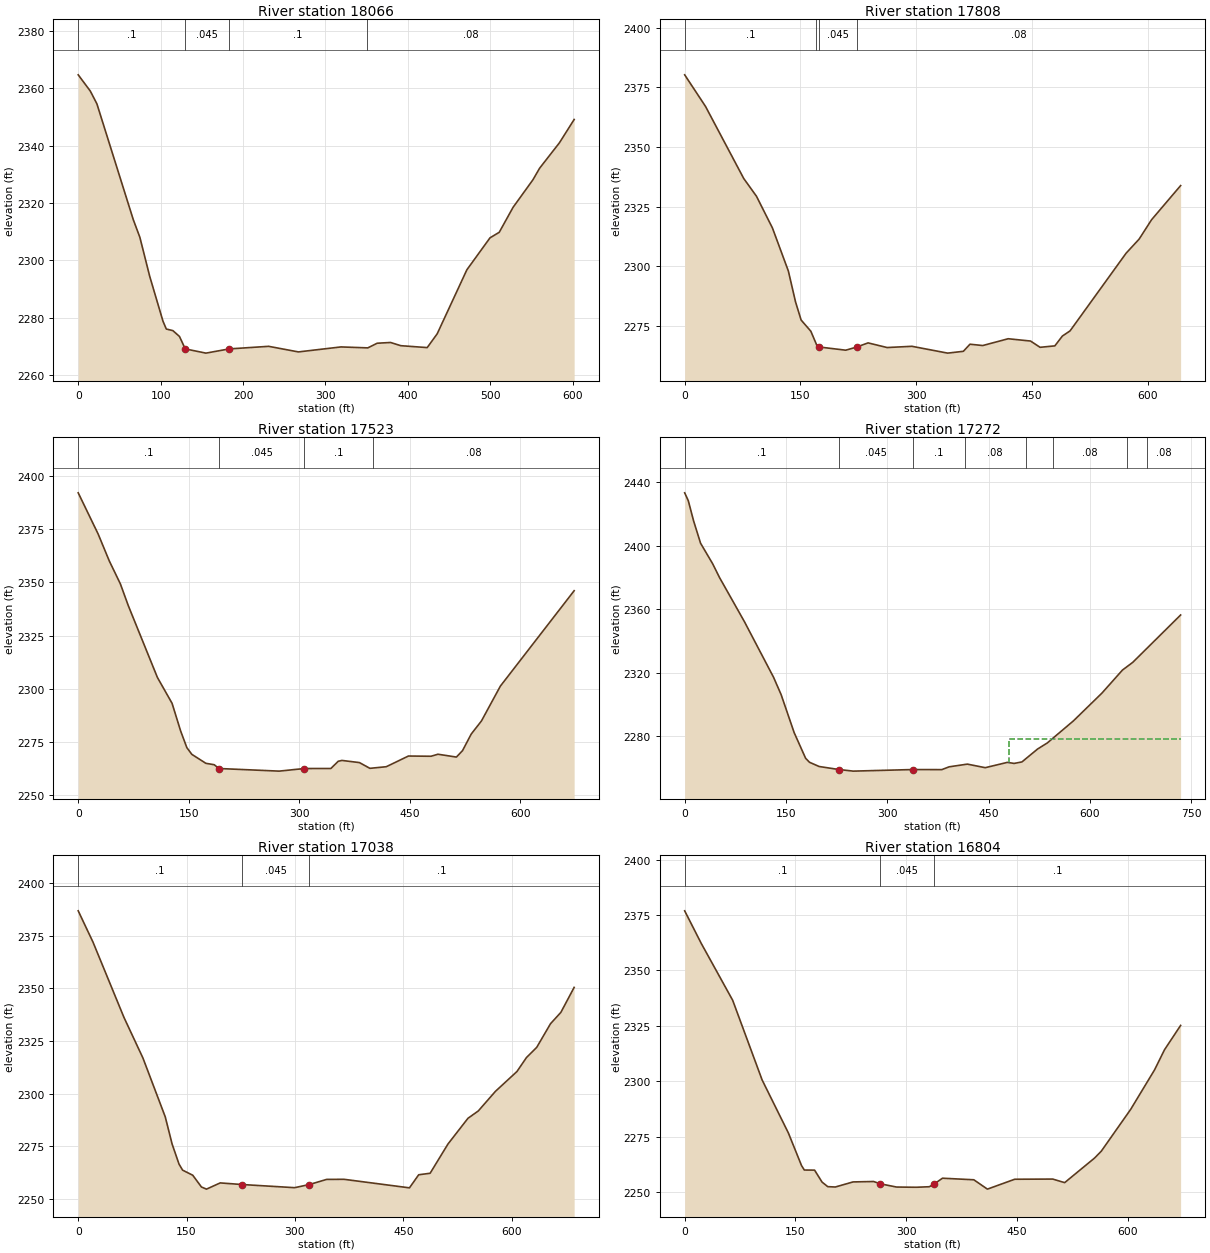
Type RM Length L Ch R = 1 ,18066   ,258.5,258.5,258.5
XS GIS Cut Line= 2
2375685.51027102714577.3335273222376286.04884717714615.858643527
#Sta/Elev= 30
       0 2364.65    14.7 2358.98    22.7 2354.53    66.8 2314.19    74.8 2308.03
    86.8 2294.38   102.9 2278.74   106.9 2276.04   114.9 2275.48   122.9 2273.44
  129.882269.116     155 2267.64   183.2 2269.11   231.1 2270.01   267.2 2268.06
   318.8  2269.8   351.4 2269.47   362.8 2271.09     379 2271.35   391.5 2270.23
   423.5 2269.57   435.6 2274.37   471.6 2296.68   499.7 2307.83   510.9 2309.76
   527.7 2318.47   551.8 2328.07   559.9  2332.1   583.9 2340.94   601.8 2349.08
#Mann= 4 ,-1,0
       0      .1       0  129.88    .045       0   183.2      .1       0
     350     .08       0
Bank Sta=129.88,183.2
XS Rating Curve= 0 ,0
Exp/Cntr(USF)=0,0
Exp/Cntr=0.3,0.1

Type RM Length L Ch R = 1 ,17808   ,284.6,284.6,284.6
XS GIS Cut Line= 2
2375673.99635405714889.5036290272376296.58866775      714731.637
#Sta/Elev= 30
       0 2380.21      27 2366.96    76.5 2336.74      93  2329.3   113.7 2315.98
   134.3 2297.94   143.6 2284.98   150.8 2277.42   163.4 2272.71   171.4 2266.62
   173.9 2266.12   208.6 2264.77   222.6 2266.07   237.5 2267.83   262.2 2265.88
   294.3  2266.4   340.6 2263.54   360.9  2264.3   369.5 2267.28     386 2266.72
     419 2269.57   447.9 2268.61   460.3 2265.98   479.4 2266.58   489.2 2270.71
   499.1 2272.86   571.7 2305.43   588.6 2311.35   604.7 2319.47   642.3 2333.77
#Mann= 4 ,-1,0
       0      .1       0     170     .08       0   173.9    .045       0
   222.6     .08       0
Bank Sta=173.9,222.6
XS Rating Curve= 0 ,0
Exp/Cntr=0.3,0.1

Type RM Length L Ch R = 1 ,17523   ,250.5,250.5,250.5
XS GIS Cut Line= 2
2375830.54600262 715214.131036372376367.63144619714808.484224556
#Sta/Elev= 30
       0 2392.04    27.1 2372.67    42.1 2360.13    57.2 2349.31    67.9 2339.14
   107.5 2305.35   127.4 2293.21   138.9 2280.35   147.4 2272.44   154.2 2269.26
   173.2 2265.06   184.6 2264.38  191.092262.608   272.7 2261.38   306.9  2262.6
   342.9 2262.62   352.9    2266   357.9  2266.4   381.7 2265.39   395.9 2262.69
   418.1 2263.45   448.2 2268.47   478.8 2268.36   488.3 2269.31   513.3 2267.98
   521.6    2271   533.4 2278.78   547.3 2284.94     573 2301.31   673.1 2346.08
#Mann= 4 ,-1,0
       0      .1       0  191.09    .045       0   306.9      .1       0
     400     .08       0
Bank Sta=191.09,306.9
XS Rating Curve= 0 ,0
Exp/Cntr(USF)=0,0
Exp/Cntr=0.3,0.1

Type RM Length L Ch R = 1 ,17272   ,234.4,234.4,234.4
XS GIS Cut Line= 3
2375978.78653628715464.9537233972376180.99705565715264.457517735
2376481.79492581714930.686350797
#Sta/Elev= 30
       0 2433.14     5.4 2428.12    13.2  2415.5    23.5 2401.48    41.4 2388.56
    51.7  2379.8    88.5  2352.1   131.5 2317.24   142.8 2306.24     162 2282.46
     179 2266.28   184.7 2263.77   199.1 2261.09  228.472259.185   249.6 2258.19
   337.5 2259.18   380.7 2259.14   391.5  2260.9   418.4 2262.59   444.9 2260.35
   477.6 2263.69   487.6 2263.03   499.2 2263.97   522.5 2272.12   536.9 2275.94
   575.4 2289.77   617.6 2307.22     648 2321.71   663.2 2326.55   734.1 2356.34
#Mann= 8 ,-1,0
       0      .1       0  228.47    .045       0   337.5      .1       0
  414.76     .08       0  504.76      .1       0  544.76     .08       0
  654.76      .1       0  684.76     .08       0
#XS Ineff= 2 , 0
                          479.37         2278.19
Permanent Ineff=
       F       F
Bank Sta=228.47,337.5
XS Rating Curve= 0 ,0
Exp/Cntr=0.3,0.1

Type RM Length L Ch R = 1 ,17038   ,233.9,233.9,233.9
XS GIS Cut Line= 2
2376114.99481823715575.8242387562376691.61257059715203.162983954
#Sta/Elev= 30
       0 2386.98    20.5 2372.06    63.3 2336.26    89.6 2316.91   120.5  2288.9
     130 2275.95   139.5 2266.46   144.5 2263.53   158.6 2261.08   170.6  2255.5
   177.6 2254.48   196.6 2257.44  226.932256.669   299.6 2255.17  320.032256.665
   343.9 2259.11   368.1 2259.15   458.6 2255.09   471.4 2261.32   487.2 2262.03
   511.9 2275.95   539.6 2288.21   553.9  2291.7   577.7 2301.06   607.4 2310.47
   620.6 2317.12   634.8 2321.99   653.9 2333.24   668.2 2338.63   686.6 2350.53
#Mann= 3 ,-1,0
       0      .1       0  226.93    .045       0  320.03      .1       0
Bank Sta=226.93,320.03
XS Rating Curve= 0 ,0
Exp/Cntr(USF)=0,0
Exp/Cntr=0.3,0.1

Type RM Length L Ch R = 1 ,16804   ,206.7,206.7,206.7
XS GIS Cut Line= 3
2376213.61794273 715738.865278232376606.56512821715549.849296778
 2376815.5406492715441.339740319
#Sta/Elev= 30
       0 2376.93    22.3 2362.31      65 2336.55   104.9 2300.56   140.4 2276.67
   158.2 2261.96     162 2259.93   175.9 2259.89     186 2254.49   193.7 2252.43
     204 2252.27     228 2254.56   255.8 2254.75   264.7 2253.72   286.9 2252.25
   313.5 2252.15   331.3 2252.39  338.19 2253.72   349.1 2256.24   391.5 2255.53
   409.9 2251.31   446.9 2255.77   498.3 2255.85   514.5 2254.24     555 2265.34
   564.1 2268.44   603.9 2287.32   636.2 2305.13   649.7 2314.23   671.5  2325.2
#Mann= 3 ,-1,0
       0      .1       0   264.7    .045       0  338.19      .1       0
Bank Sta=264.7,338.19
XS Rating Curve= 0 ,0
Exp/Cntr=0.3,0.1

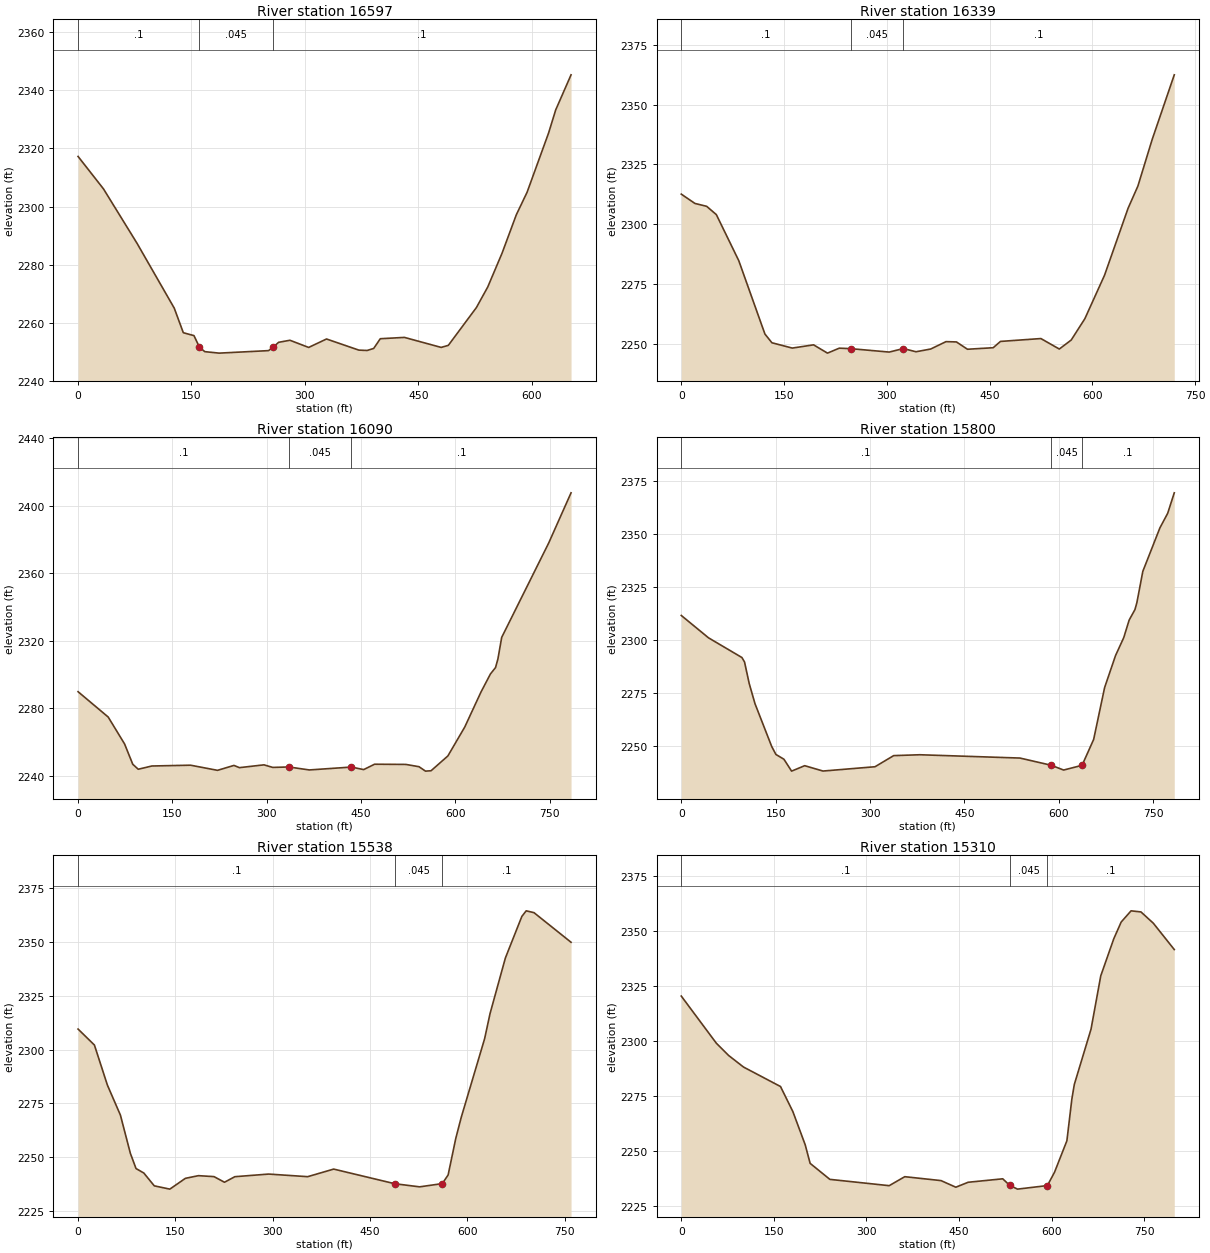
Type RM Length L Ch R = 1 ,16597   ,258.8,258.8,258.8
XS GIS Cut Line= 2
2376374.58346979715915.168235375 2376925.2660132715566.176006217
#Sta/Elev= 30
       0 2317.26    33.6 2306.09      78 2287.33   127.2 2265.01   139.2 2256.53
   153.3 2255.53   160.6 2251.52   167.6 2250.01   186.6  2249.5   251.9 2250.36
  258.16 2251.59   265.3 2253.23   280.2 2253.93     305 2251.46   328.6 2254.37
   371.3 2250.54   382.3 2250.41     391 2251.12   399.7 2254.46   431.6 2254.92
   480.2 2251.47   489.7 2252.18   526.8 2265.19   541.8 2272.27   560.7  2283.9
   579.6 2297.16   593.9 2304.95   622.3 2325.34   631.7 2333.29     652 2345.38
#Mann= 3 ,-1,0
       0      .1       0   160.6    .045       0  258.16      .1       0
Bank Sta=160.6,258.16
XS Rating Curve= 0 ,0
Exp/Cntr(USF)=0,0
Exp/Cntr=0.3,0.1

Type RM Length L Ch R = 1 ,16339   ,248.5,248.5,248.5
XS GIS Cut Line= 4
2376471.79395788716196.6871129192376634.05666459716070.397429714
 2376827.3230439715897.558170264     2377034.571715749.508114691
#Sta/Elev= 30
       0 2312.62    19.9 2308.73      37 2307.53    51.2 2304.05    83.9 2284.83
   122.1 2254.15   132.3 2250.51     162 2248.29   193.1 2249.64   213.4 2246.18
   230.6 2248.25   247.6 2248.04   303.5 2246.62   324.1 2248.08   342.6 2246.75
   364.1  2247.9   386.4 2250.98   401.6 2250.86   417.7  2247.8   455.3 2248.44
   465.9 2251.07   524.9 2252.27   551.8 2247.89   569.2 2251.66   589.1 2260.57
   617.8 2278.72   652.2 2306.73   666.5 2315.98   687.2 2335.33   719.6 2362.47
#Mann= 3 ,-1,0
       0      .1       0   247.6    .045       0   324.1      .1       0
Bank Sta=247.6,324.1
XS Rating Curve= 0 ,0
Exp/Cntr=0.3,0.1

Type RM Length L Ch R = 1 ,16090   ,290.3,290.3,290.3
XS GIS Cut Line= 4
  2376524.151568716359.3401633952376832.35249765716227.901531634
2376959.25876279716105.5276330982377204.00655987715985.419917868
#Sta/Elev= 30
       0 2289.87    47.9 2274.87      74  2258.9      87 2246.87    95.7 2243.92
   117.4 2245.85   178.9 2246.32   221.8 2243.28   247.9 2246.19   256.6 2244.87
   295.7 2246.53   309.6 2245.01   335.1 2245.27   367.8 2243.51   434.8 2245.22
   454.2 2243.71   471.5  2246.9   521.3 2246.78   542.2 2245.43   552.5 2242.81
   561.4 2243.04   588.1  2251.8   614.9  2268.9   640.8  2289.7   655.8 2300.38
   663.9 2304.17   667.7  2309.3   673.7 2322.05   748.4 2377.94     784 2407.71
#Mann= 3 ,-1,0
       0      .1       0   335.1    .045       0   434.8      .1       0
Bank Sta=335.1,434.8
XS Rating Curve= 0 ,0
Exp/Cntr(USF)=0,0
Exp/Cntr=0.3,0.1

Type RM Length L Ch R = 1 ,15800   ,262.1,262.1,262.1
XS GIS Cut Line= 3
 2376491.5576846716582.0520286732376888.24781274 716469.04098655
2377230.21558336716325.468443541
#Sta/Elev= 30
       0 2311.66    43.3 2301.11    96.3 2291.84   100.5 2289.73     108  2279.5
   117.1 2270.09   143.6 2249.95   150.4 2246.12   163.1 2243.88   175.3 2238.27
   196.1 2240.83   225.2 2238.31   307.9 2240.34   337.5 2245.58   379.1 2245.99
   538.2 2244.43   587.8 2241.04   607.6 2238.78   636.9 2241.01   655.3 2253.22
   672.7 2277.66     690  2292.7   703.1 2301.21   711.7 2309.48   720.9 2314.43
     724 2317.72   733.4 2332.44   760.6 2352.97   772.9  2359.8   783.4 2369.48
#Mann= 3 ,-1,0
       0      .1       0   587.8    .045       0   636.9      .1       0
Bank Sta=587.8,636.9
XS Rating Curve= 0 ,0
Exp/Cntr=0.3,0.1

Type RM Length L Ch R = 1 ,15538   ,228.3,228.3,228.3
XS GIS Cut Line= 2
2376547.05182869716689.4939778912377305.15813012716641.768157462
#Sta/Elev= 30
       0 2309.51    25.2 2302.09    45.2  2283.5    65.3 2269.53    80.5  2251.9
    89.3 2244.76   101.3 2242.68   117.4 2236.73   141.4  2235.2   165.4 2240.21
   185.5 2241.45   209.5    2241   225.6 2238.39   241.6 2240.97   293.7 2242.19
   353.8 2240.98   393.9  2244.5   487.8 2237.72   526.2 2236.26   561.2 2237.76
   570.2 2241.77     582 2258.77   590.3 2268.42   626.4    2305   634.8 2316.72
   658.4 2342.49   683.8 2361.81   690.5  2364.4   702.5 2363.55   759.6  2349.8
#Mann= 3 ,-1,0
       0      .1       0   487.8    .045       0   561.2      .1       0
Bank Sta=487.8,561.2
XS Rating Curve= 0 ,0
Exp/Cntr(USF)=0,0
Exp/Cntr=0.3,0.1

Type RM Length L Ch R = 1 ,15310   ,260.8,260.8,260.8
XS GIS Cut Line= 3
2376471.41589876716891.5462867272376919.74265593716880.385271505
2377270.14691221716883.212042123
#Sta/Elev= 30
       0 2320.26    56.8 2298.85    76.8 2293.26   100.9 2288.01   160.8 2279.17
   180.8  2267.8   200.8 2252.72   208.8 2244.27   240.8 2236.99   336.9 2234.13
   362.2 2238.21   420.9 2236.43   444.9 2233.43   464.9 2235.68   520.9 2237.25
  532.262234.258   544.9 2232.56   593.3 2234.18   604.9 2240.27   624.9 2254.54
   632.9 2273.41   636.9 2280.09     664 2305.23   679.8 2329.48   700.9 2346.32
   712.9 2353.91   728.9 2358.99   744.9 2358.49   764.9 2353.38   798.9  2341.4
#Mann= 3 ,-1,0
       0      .1       0  532.26    .045       0   593.3      .1       0
Bank Sta=532.26,593.3
XS Rating Curve= 0 ,0
Exp/Cntr=0.3,0.1

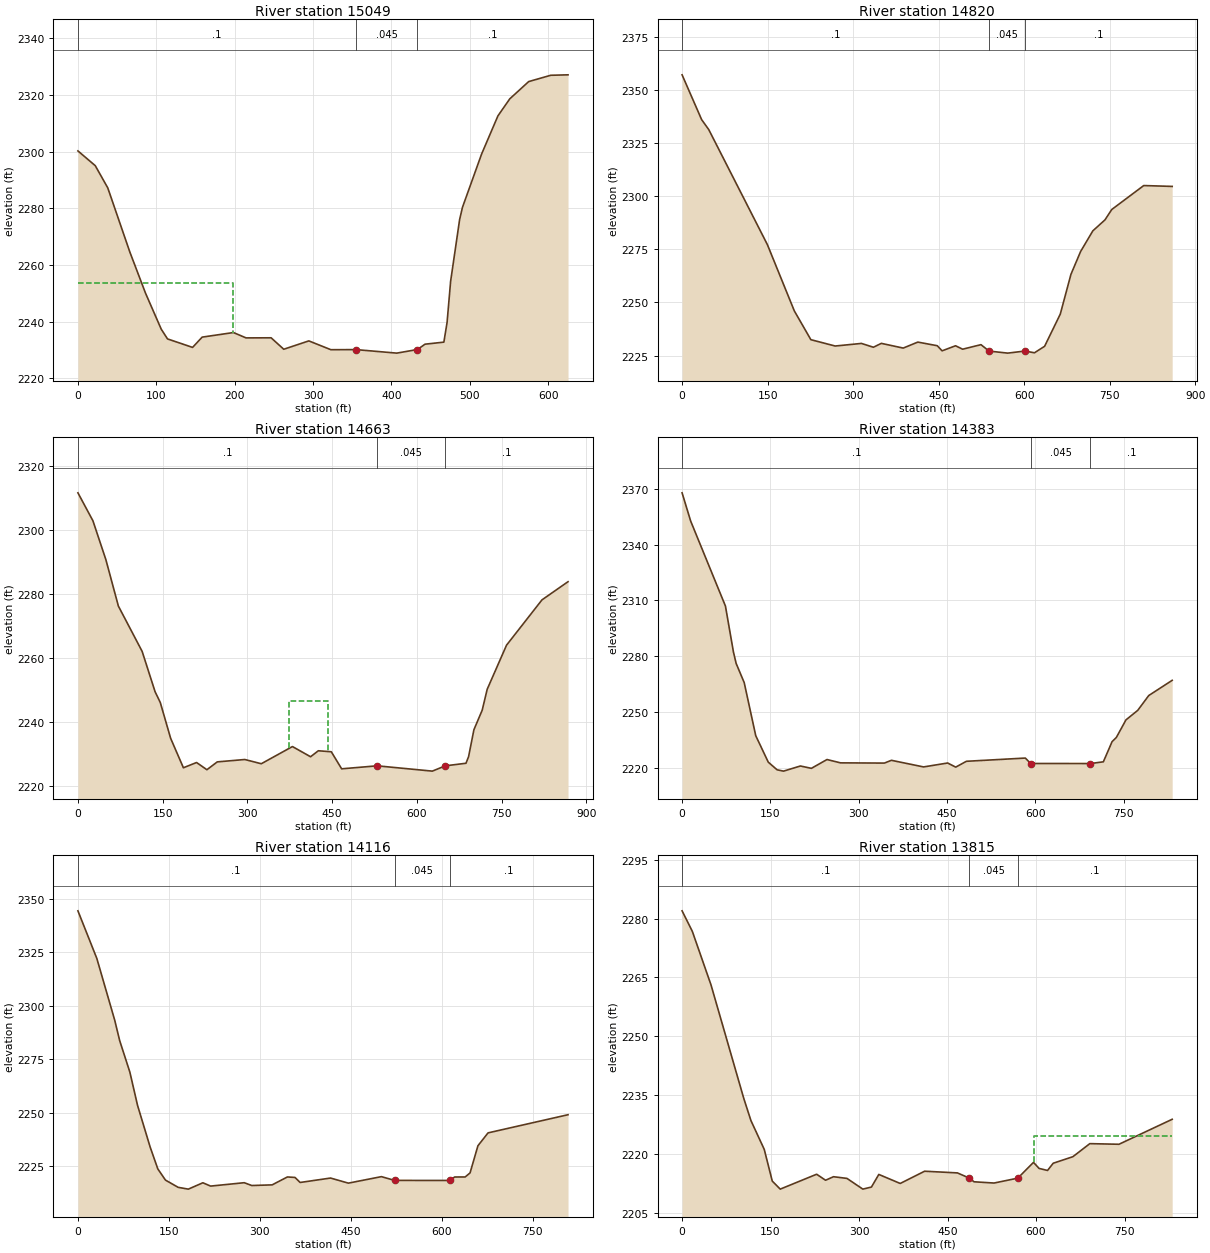
Type RM Length L Ch R = 1 ,15049   ,228.4,228.4,228.4
XS GIS Cut Line= 2
2376602.12008303717163.0809652252377226.22696557717124.533187187
#Sta/Elev= 30
       0 2300.29    22.1 2295.09    38.1 2287.23    66.2 2264.62    86.2 2250.09
   106.3 2237.34   114.3  2233.9   146.3  2230.9   158.5 2234.53   198.4 2236.15
   214.5 2234.26   246.5 2234.29   262.6 2230.25   294.6  2233.2   322.7 2230.09
   354.8 2230.12   406.8 2228.88   433.2 2230.16   442.9 2232.04   466.9 2232.76
     471 2239.74   475.5 2254.22     487 2276.05   490.6 2280.35     515 2299.16
   535.9 2312.68     551 2318.68   575.1 2324.77   603.2    2327   625.3 2327.16
#Mann= 3 ,-1,0
       0      .1       0   354.8    .045       0   433.2      .1       0
#XS Ineff= 2 , 0
          198.25 2253.62
Permanent Ineff=
       F       F
Bank Sta=354.8,433.2
XS Rating Curve= 0 ,0
Exp/Cntr(USF)=0,0
Exp/Cntr=0.3,0.1

Type RM Length L Ch R = 1 ,14820   ,157.1,157.1,157.1
XS GIS Cut Line= 2
2376520.27827936717557.374275538 2377326.7810153717259.696741946
#Sta/Elev= 30
       0 2357.28    34.3 2336.17    46.8 2331.47   149.6 2277.29   196.9 2246.03
   225.9 2232.48   268.5 2229.49   314.6 2230.71   335.6 2228.91   349.5 2230.74
   387.9 2228.52   413.5 2231.34   447.6 2229.63   456.1 2227.22   479.7 2229.61
   492.1 2227.99   524.3 2230.13   538.52227.106   571.2 2226.14   601.3 2227.12
   618.1  2226.3   635.9 2229.35   663.4 2244.52   682.1 2263.26   699.1 2274.05
   720.5 2283.75   741.8 2288.93   753.7 2293.82   809.8  2305.1   859.7  2304.7
#Mann= 3 ,-1,0
       0      .1       0   538.5    .045       0   601.3      .1       0
Bank Sta=538.5,601.3
XS Rating Curve= 0 ,0
Exp/Cntr=0.3,0.1

Type RM Length L Ch R = 1 ,14663   ,280.3,280.3,280.3
XS GIS Cut Line= 2
2376633.00193044717776.1722799092377389.68053639717351.942764984
#Sta/Elev= 30
       0 2311.58    26.6 2302.83    49.5 2290.69    71.6  2276.2   113.7 2262.03
   136.6 2249.42   145.8 2246.06   164.1 2234.89   186.7 2225.67     210 2227.31
   228.3 2225.06   246.7 2227.51   295.4 2228.25   324.6 2226.93   379.7  2232.3
   411.8 2229.11   425.5 2230.98   448.5 2230.67   466.8 2225.34  529.672226.277
   627.3 2224.62   650.2 2226.27   686.9 2227.08   691.5 2229.15   700.9 2237.54
   715.6 2243.67   724.4 2250.18   758.6 2263.96   821.4 2278.13   867.5 2283.81
#Mann= 3 ,-1,0
       0      .1       0  529.67    .045       0   650.2      .1       0
#XS Ineff= 1 ,-1
  374.16  442.95 2246.39
Permanent Ineff=
       F
Bank Sta=529.67,650.2
XS Rating Curve= 0 ,0
Exp/Cntr(USF)=0,0
Exp/Cntr=0.3,0.1

Type RM Length L Ch R = 1 ,14383   ,267.1,267.1,267.1
XS GIS Cut Line= 2
2377067.42927024718177.9665801032377463.10487551717445.762753862
#Sta/Elev= 30
       0 2367.84    14.5  2352.7    73.6 2306.94    87.3 2282.05    91.8 2276.04
   105.5 2265.71   125.1 2237.14   146.4 2222.89   161.4 2218.77   172.3 2218.07
   200.9 2220.83   219.6 2219.57   246.1 2224.31   269.1 2222.52   343.5  2222.4
   355.5 2223.89   410.1 2220.33     451 2222.44   464.7 2220.22   482.8 2223.36
   582.9  2225.1     592 2222.17  693.532222.154   715.4 2223.08   730.2 2233.91
   737.5 2236.21   753.8 2245.65   773.8 2250.77   792.5 2258.75   832.3 2266.94
#Mann= 3 ,-1,0
       0      .1       0     592    .045       0  693.53      .1       0
Bank Sta=592,693.53
XS Rating Curve= 0 ,0
Exp/Cntr(USF)=0,0
Exp/Cntr=0.3,0.1

Type RM Length L Ch R = 1 ,14116   ,301.4,301.4,301.4
XS GIS Cut Line= 2
2377443.83932057718246.9973221062377684.68492942717475.344696332
#Sta/Elev= 30
       0 2344.37    31.2 2322.09    60.6 2293.31    68.9 2283.65    85.7  2268.9
    98.3 2253.43   119.2 2233.83   131.8 2223.65   144.4 2218.43   165.3 2215.04
   182.1  2214.2   206.1 2217.17   218.9 2215.62   274.3  2217.2   286.8 2215.89
   320.4 2216.19   345.5 2219.89   358.1 2219.66   366.5 2217.31   416.7 2219.38
   446.1    2217   500.6 2220.04   522.3 2218.28   613.7 2218.25   621.3 2219.87
   638.8 2219.89   646.8 2221.79   659.8 2234.49   676.5 2240.51   808.4    2249
#Mann= 3 ,-1,0
       0      .1       0   522.3    .045       0   613.7      .1       0
Bank Sta=522.3,613.7
XS Rating Curve= 0 ,0
Exp/Cntr=0.3,0.1

Type RM Length L Ch R = 1 ,13815   ,264.8,264.8,264.8
XS GIS Cut Line= 3
2377614.38990726718308.610462089 2377773.1236492718005.336942727
2378040.13059356717596.309202408
#Sta/Elev= 30
       0 2281.97    17.4 2276.73      49 2263.13   104.6  2234.2   116.7 2228.58
   139.3 2221.23   152.9 2213.16   166.4 2211.12   228.1 2214.91   243.2 2213.38
   256.7 2214.28   279.5 2213.85   306.4 2211.12     321 2211.65   333.5 2214.86
   369.8 2212.56   411.1 2215.68   466.7 2215.25   486.9 2213.93   494.9 2212.99
   528.8 2212.67  569.062213.914   595.7 2217.93   605.2 2216.39   619.5 2215.87
   629.1 2217.71   662.5 2219.38   691.2  2222.7   740.6 2222.54   830.8  2228.9
#Mann= 3 ,-1,0
       0      .1       0   486.9    .045       0  569.06      .1       0
#XS Ineff= 2 , 0
                          595.82         2224.77
Permanent Ineff=
       F       F
Bank Sta=486.9,569.06
XS Rating Curve= 0 ,0
Exp/Cntr=0.3,0.1

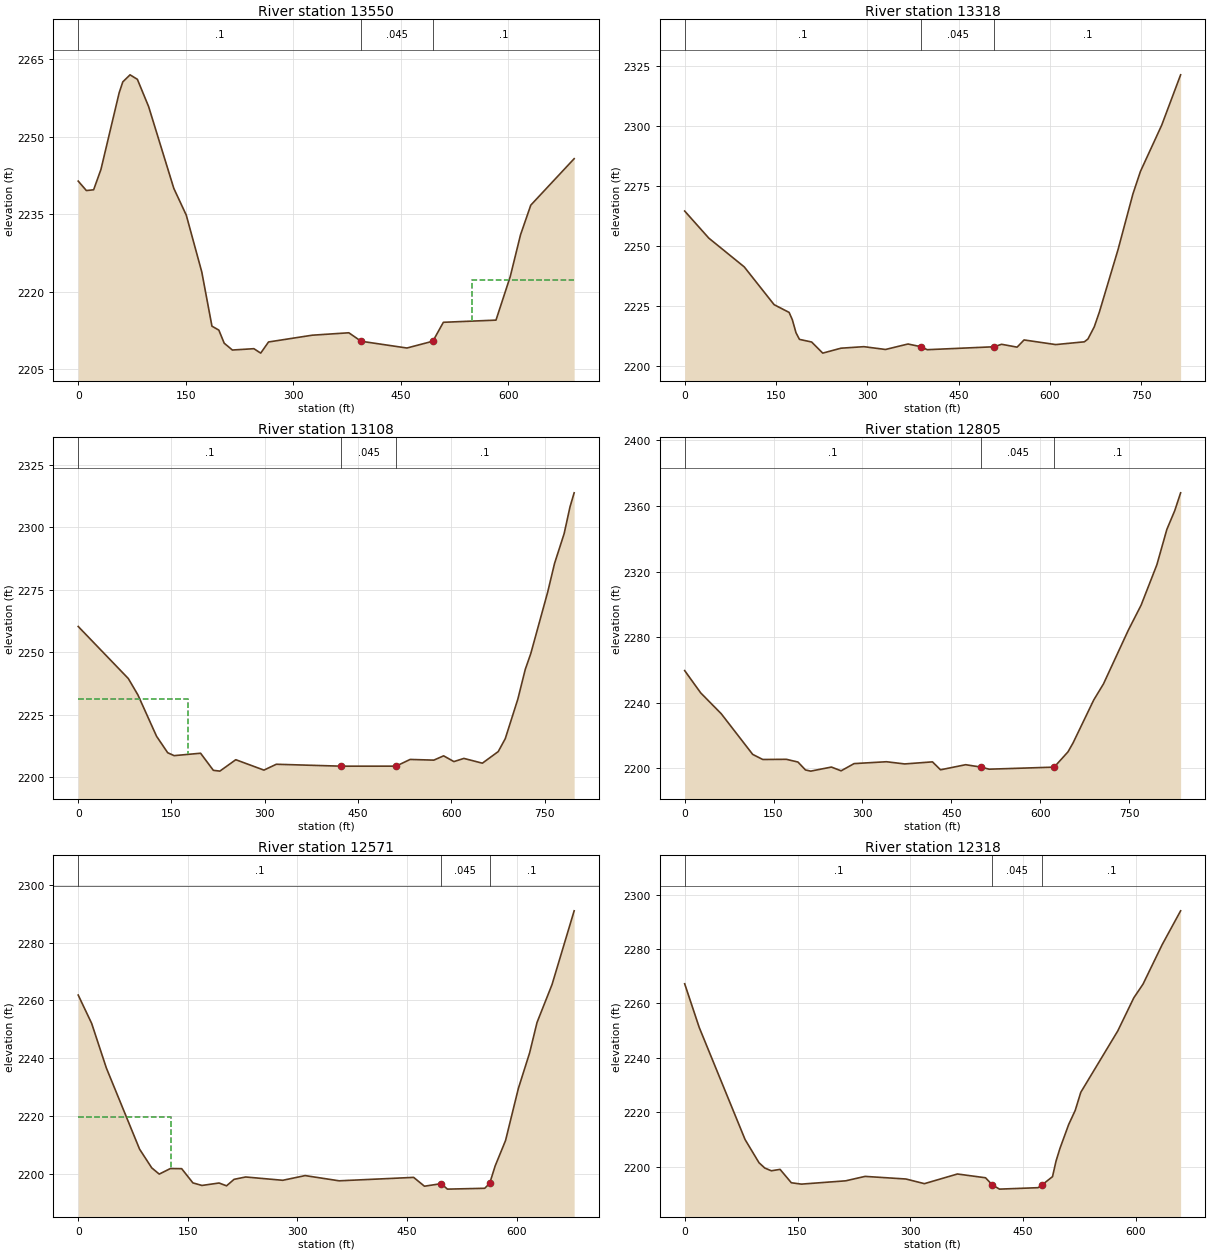
Type RM Length L Ch R = 1 ,13550   ,232,232,232
XS GIS Cut Line= 2
2377791.30738564718386.1414046682378217.57646554717841.577556183
#Sta/Elev= 30
       0 2241.43    11.4  2239.6    21.5 2239.75    31.7 2243.69    57.1 2258.53
    62.2 2260.65    72.3 2262.01    82.5 2261.14    98.2 2255.86   133.3 2240.03
   150.7 2234.84   172.3 2223.85   186.5 2213.34   196.1 2212.58   203.6 2210.04
     215 2208.72     245 2208.98   254.5 2208.12   265.4 2210.28   326.3 2211.59
   377.4 2212.06   394.5 2210.42   458.4 2209.11   494.6 2210.43   509.2 2214.09
   582.6 2214.51   602.5 2222.96   616.8 2231.02   631.1 2236.77   691.6 2245.77
#Mann= 3 ,-1,0
       0      .1       0   394.5    .045       0   494.6      .1       0
#XS Ineff= 2 , 0
                          549.63         2222.34
Permanent Ineff=
       F       F
Bank Sta=394.5,494.6
XS Rating Curve= 0 ,0
Exp/Cntr(USF)=0,0
Exp/Cntr=0.3,0.1

Type RM Length L Ch R = 1 ,13318   ,209.7,209.7,209.7
XS GIS Cut Line= 2
     2377874.064      718504.9182378491.77347867717974.159569319
#Sta/Elev= 30
       0  2264.7    39.7  2253.4    97.8 2241.44   146.9 2225.69   171.5 2222.47
   176.8 2219.43   182.8    2214   188.5 2211.24   208.5 2210.14   226.7 2205.51
   256.6 2207.56   294.2  2208.2   329.8 2207.03   366.7 2209.31   387.8 2208.19
   398.3 2206.94  508.332208.164   520.4 2209.19   545.9    2208   557.3    2211
   609.3 2209.07   656.3 2210.22   662.2 2211.39   672.6 2216.46   680.9 2222.56
   711.6 2248.61   736.1 2271.85   748.4  2281.2   783.3 2300.45   814.4 2321.45
#Mann= 3 ,-1,0
       0      .1       0   387.8    .045       0  508.33      .1       0
Bank Sta=387.8,508.33
XS Rating Curve= 0 ,0
Exp/Cntr=0.3,0.1

Type RM Length L Ch R = 1 ,13108   ,303.4,303.4,303.4
XS GIS Cut Line= 2
2378010.41988642718677.2859324682378604.15991265718144.732855505
#Sta/Elev= 30
       0 2260.36    80.6 2239.51      96 2232.97     126  2216.4   143.9 2209.81
   154.3 2208.64   196.8 2209.61   217.3 2202.77   227.8 2202.44   253.4 2207.01
   298.7 2202.85   318.6 2205.19   423.4 2204.42   511.2 2204.43   533.8 2207.12
   571.9 2206.84   587.7 2208.56   604.2 2206.26   620.3 2207.53     650 2205.62
   675.5 2210.27   686.8 2215.43   707.1 2231.33     719 2243.21   727.8 2249.46
     755  2274.1   766.1 2285.63   781.5 2297.53   790.9 2308.22   797.6 2313.88
#Mann= 3 ,-1,0
       0      .1       0   423.4    .045       0   511.2      .1       0
#XS Ineff= 2 , 0
          176.82 2231.51
Permanent Ineff=
       F       F
Bank Sta=423.4,511.2
XS Rating Curve= 0 ,0
Exp/Cntr(USF)=0,0
Exp/Cntr=0.3,0.1

Type RM Length L Ch R = 1 ,12805   ,234,234,234
XS GIS Cut Line= 2
2378183.01931175718938.2527306432378795.41201736718367.698543718
#Sta/Elev= 30
       0 2259.56      27 2245.99    61.7 2233.25   114.8 2208.43   131.8 2205.32
   171.7 2205.43   191.2 2203.76   203.9 2198.93   212.8 2198.22   247.6  2200.7
     264 2198.41   285.9 2202.81   340.5 2203.95   371.3 2202.61   418.2 2203.87
   431.8 2199.03   474.2 2202.14   499.7  2200.7   513.8  2199.4   623.6 2200.66
   646.9 2209.98   655.4 2215.38   690.4 2241.66   706.8 2251.44   748.7 2284.21
   770.3 2299.49   796.9 2324.14   813.8 2345.76   827.1 2357.19     837 2368.06
#Mann= 3 ,-1,0
       0      .1       0   499.7    .045       0   623.6      .1       0
Bank Sta=499.7,623.6
XS Rating Curve= 0 ,0
Exp/Cntr=0.3,0.1

Type RM Length L Ch R = 1 ,12571   ,252.6,252.6,252.6
XS GIS Cut Line= 2
2378309.55608284719080.666560975 2378839.8429765718656.890282711
#Sta/Elev= 30
       0 2261.87    18.4 2252.05    38.5 2236.61      84 2208.47   100.6    2202
   110.9 2199.83   126.2 2201.76   141.6 2201.71     157 2196.78   169.4 2195.89
   192.8 2196.74     203 2195.76   213.3 2198.01   229.2 2198.83   279.9 2197.68
   310.6 2199.31   357.2  2197.5   459.1 2198.69   473.9 2195.63   496.7 2196.51
   505.4 2194.62   556.4 2194.91  563.162196.607   570.7 2202.66   584.9 2211.46
   602.4 2229.47   617.8  2241.8     628 2252.38   648.5 2265.49   678.8 2291.06
#Mann= 3 ,-1,0
       0      .1       0   496.7    .045       0  563.16      .1       0
#XS Ineff= 2 , 0
          126.63 2219.72
Permanent Ineff=
       F       F
Bank Sta=496.7,563.16
XS Rating Curve= 0 ,0
Exp/Cntr(USF)=0,0
Exp/Cntr=0.3,0.1

Type RM Length L Ch R = 1 ,12318   ,262,262,262
XS GIS Cut Line= 2
     2378444.157      719219.7232379005.08080541718873.235708274
#Sta/Elev= 30
       0  2267.2    19.3 2251.18    80.3 2209.96    98.8 2201.45   106.5 2199.49
   115.2 2198.48   126.8    2199   141.8 2194.08   155.2 2193.58     214 2194.79
   239.8 2196.42   294.1 2195.46   318.7 2193.75   362.6  2197.3     400 2195.91
   408.7 2193.34   418.5 2191.74   469.8 2192.27  475.322193.334     489 2196.33
   493.7 2202.06   498.8 2206.63   510.5 2215.49   519.2 2220.68   526.6 2227.33
   575.7 2249.85   597.1 2262.06   609.3 2267.06   634.7 2281.54   659.3 2294.01
#Mann= 3 ,-1,0
       0      .1       0   408.7    .045       0  475.32      .1       0
Bank Sta=408.7,475.32
XS Rating Curve= 0 ,0
Exp/Cntr=0.3,0.1