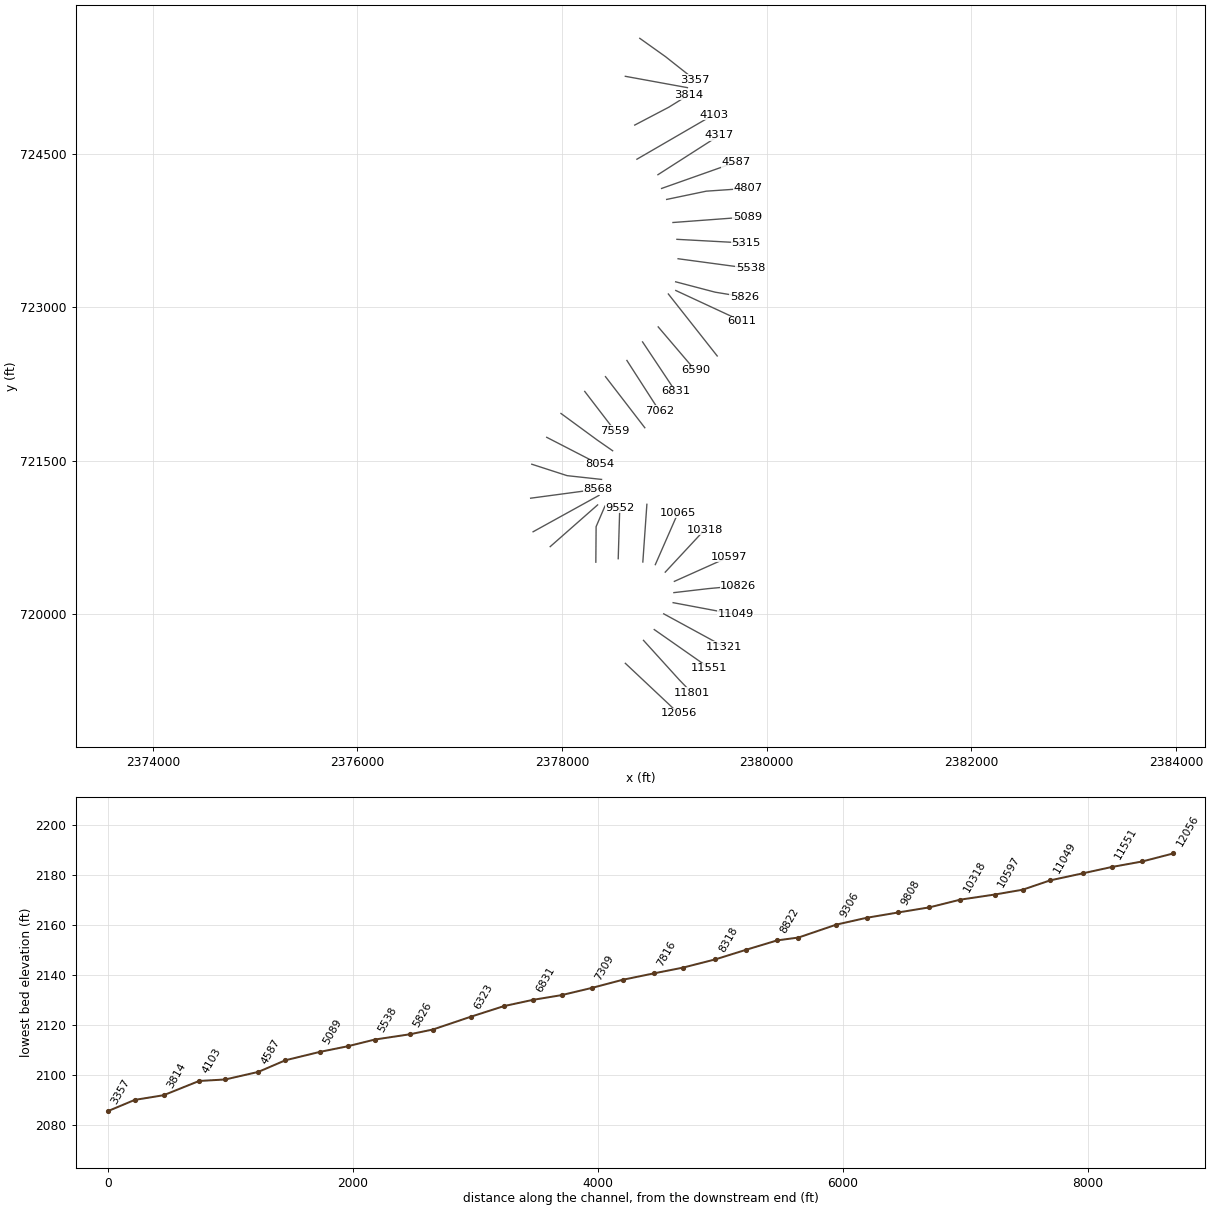
HEC-RAS study LAURELFK.prj: LAURELFK

--- LAURELFK.g01 (geometry) --- (continued)

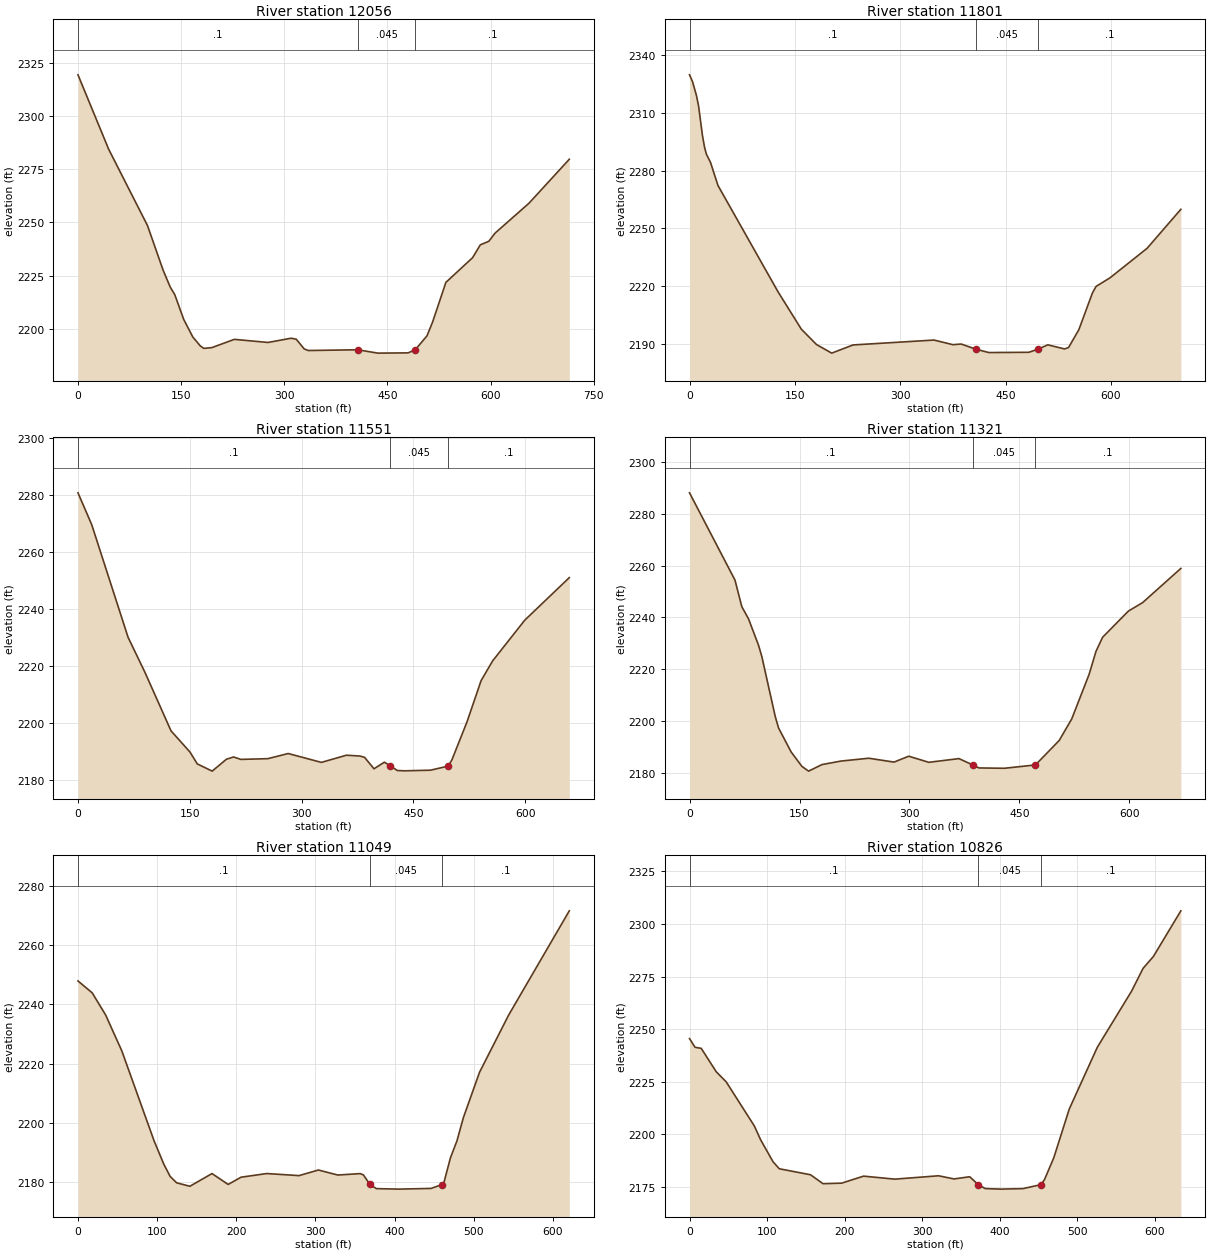
Type RM Length L Ch R = 1 ,12056   ,254.7,254.7,254.7
XS GIS Cut Line= 2
2378618.52971541719518.6024456172379138.91254869719028.994941186
#Sta/Elev= 30
       0 2319.34    44.6  2284.4   101.1 2248.49   123.8 2227.54   134.1 2219.64
   140.8 2215.99   153.8 2204.37     167 2196.13     178  2191.9     183 2190.78
   194.6 2191.13   227.4 2195.02   276.4 2193.56   309.8 2195.55   317.3 2195.12
     329 2190.53   334.8 2189.78   406.8 2190.12   436.1 2188.55   480.1 2188.67
  490.442190.131   507.5 2196.66   515.8 2203.25     535 2221.79   573.8 2233.39
   585.1 2239.44   597.5 2241.12   606.4  2244.9   655.9 2259.01   714.5 2279.66
#Mann= 3 ,-1,0
       0      .1       0   406.8    .045       0  490.44      .1       0
Bank Sta=406.8,490.44
XS Rating Curve= 0 ,0
Exp/Cntr(USF)=0,0
Exp/Cntr=0.3,0.1

Type RM Length L Ch R = 1 ,11801   ,250.2,250.2,250.2
XS GIS Cut Line= 3
     2378795.981      719743.1652379143.16533912719359.820788047
2379269.55419458719228.600017373
#Sta/Elev= 30
       0 2329.75     4.4 2326.06      10 2318.82    12.9 2313.51    18.5 2298.01
    21.4 2292.16    24.1  2288.5    29.9 2284.27    40.5 2272.31   126.1 2217.08
   159.2 2197.73   180.8 2189.77   202.4 2185.32   232.7 2189.56   348.1  2192.1
     375  2189.7   386.7 2190.04   407.4  2187.4   426.1 2185.62     483 2185.75
  496.182187.399     510 2189.62   533.9 2187.49   539.6 2188.25   554.2 2197.47
   573.5 2216.51   578.7 2219.93   598.6 2224.41   651.3  2239.7   699.4 2259.96
#Mann= 3 ,-1,0
       0      .1       0   407.4    .045       0  496.18      .1       0
Bank Sta=407.4,496.18
XS Rating Curve= 0 ,0
Exp/Cntr=0.3,0.1

Type RM Length L Ch R = 1 ,11551   ,230.5,230.5,230.5
XS GIS Cut Line= 2
2378901.10318939719848.7377914622379441.07032285719471.040573758
#Sta/Elev= 30
       0 2280.66    18.4 2269.53    67.2 2230.01      90 2217.63   124.8 2197.22
   150.2  2189.8     160 2185.64     180  2183.1     199 2187.25   208.7 2188.06
   218.5 2187.21   254.7 2187.47     282 2189.27   326.5 2186.16   360.1 2188.68
   378.2 2188.39   384.5 2187.91     397 2183.92     411 2186.24   418.82184.939
   428.4 2183.31   438.9 2183.21   472.9 2183.43   496.8 2184.88   501.7 2187.15
   521.8 2200.37   540.7 2214.83   556.2 2221.76   599.3 2236.03     659 2250.93
#Mann= 3 ,-1,0
       0      .1       0   418.8    .045       0   496.8      .1       0
Bank Sta=418.8,496.8
XS Rating Curve= 0 ,0
Exp/Cntr(USF)=0,0
Exp/Cntr=0.3,0.1

Type RM Length L Ch R = 1 ,11321   ,271.4,271.4,271.4
XS GIS Cut Line= 2
     2378993.592      720002.6562379581.95024254719682.001073658
#Sta/Elev= 30
       0 2288.13      62 2254.42    71.3 2244.16    80.4  2239.5    94.1 2229.27
    98.6 2224.91   116.8 2201.86   121.4 2197.32   138.6 2188.04   153.3 2182.46
   162.4 2180.63   180.6 2183.15   206.4 2184.51   244.4 2185.61   278.9 2184.12
     299 2186.39   326.4 2184.03   367.4 2185.47   386.3 2183.03   394.7 2181.86
   429.4 2181.73   471.8 2183.02   504.2 2192.47   521.3 2200.81     545 2218.03
   554.4 2226.92   563.4 2232.34   598.6 2242.46   617.9 2245.71   670.1 2258.93
#Mann= 3 ,-1,0
       0      .1       0   386.3    .045       0   471.8      .1       0
Bank Sta=386.3,471.8
XS Rating Curve= 0 ,0
Exp/Cntr=0.3,0.1

Type RM Length L Ch R = 1 ,11049   ,223.1,223.1,223.1
XS GIS Cut Line= 2
2379085.75516249720111.7269652712379695.66622516719997.018921376
#Sta/Elev= 30
       0 2247.89      18 2243.88      35  2236.4    55.4 2224.32    96.1 2194.05
   108.3 2186.24   116.4 2182.05   124.6 2179.89   141.3 2178.72   169.3    2183
   189.7 2179.34     206 2181.78   238.5 2183.01   279.2 2182.31   303.7  2184.2
   328.1 2182.51   356.6 2182.99   360.6 2182.53   368.8 2179.33   376.9 2177.93
   405.1 2177.76     446    2178   459.9  2179.3   462.4 2180.14   470.5 2188.33
   478.7 2194.03   486.8 2201.84   507.2 2217.12   543.8 2236.31   620.6 2271.52
#Mann= 3 ,-1,0
       0      .1       0   368.8    .045       0   459.9      .1       0
Bank Sta=368.8,459.9
XS Rating Curve= 0 ,0
Exp/Cntr(USF)=0,0
Exp/Cntr=0.3,0.1

Type RM Length L Ch R = 1 ,10826   ,228.8,228.8,228.8
XS GIS Cut Line= 3
2379093.15229951720210.0106949272379426.86553093720248.944045171
2379723.41902781720276.434350244
#Sta/Elev= 30
       0 2245.54     7.1 2241.42    15.1 2240.91    34.4 2229.82    47.3    2225
    83.6 2204.05    91.6 2197.57   107.7 2187.06   115.8 2183.71   156.1 2180.86
   172.2 2176.63   196.3 2176.88   224.5 2180.21   264.8 2178.78   321.2 2180.38
   341.3 2178.88   361.4 2179.92   372.6 2176.13   381.5 2174.31   401.6 2174.04
   430.1 2174.28  453.112176.154   457.8 2178.48   469.9 2188.93   489.9 2212.13
   526.1 2241.45   570.3 2268.11   585.1 2278.92   598.4 2284.55   633.8 2306.23
#Mann= 3 ,-1,0
       0      .1       0   372.6    .045       0  453.11      .1       0
Bank Sta=372.6,453.11
XS Rating Curve= 0 ,0
Exp/Cntr=0.3,0.1

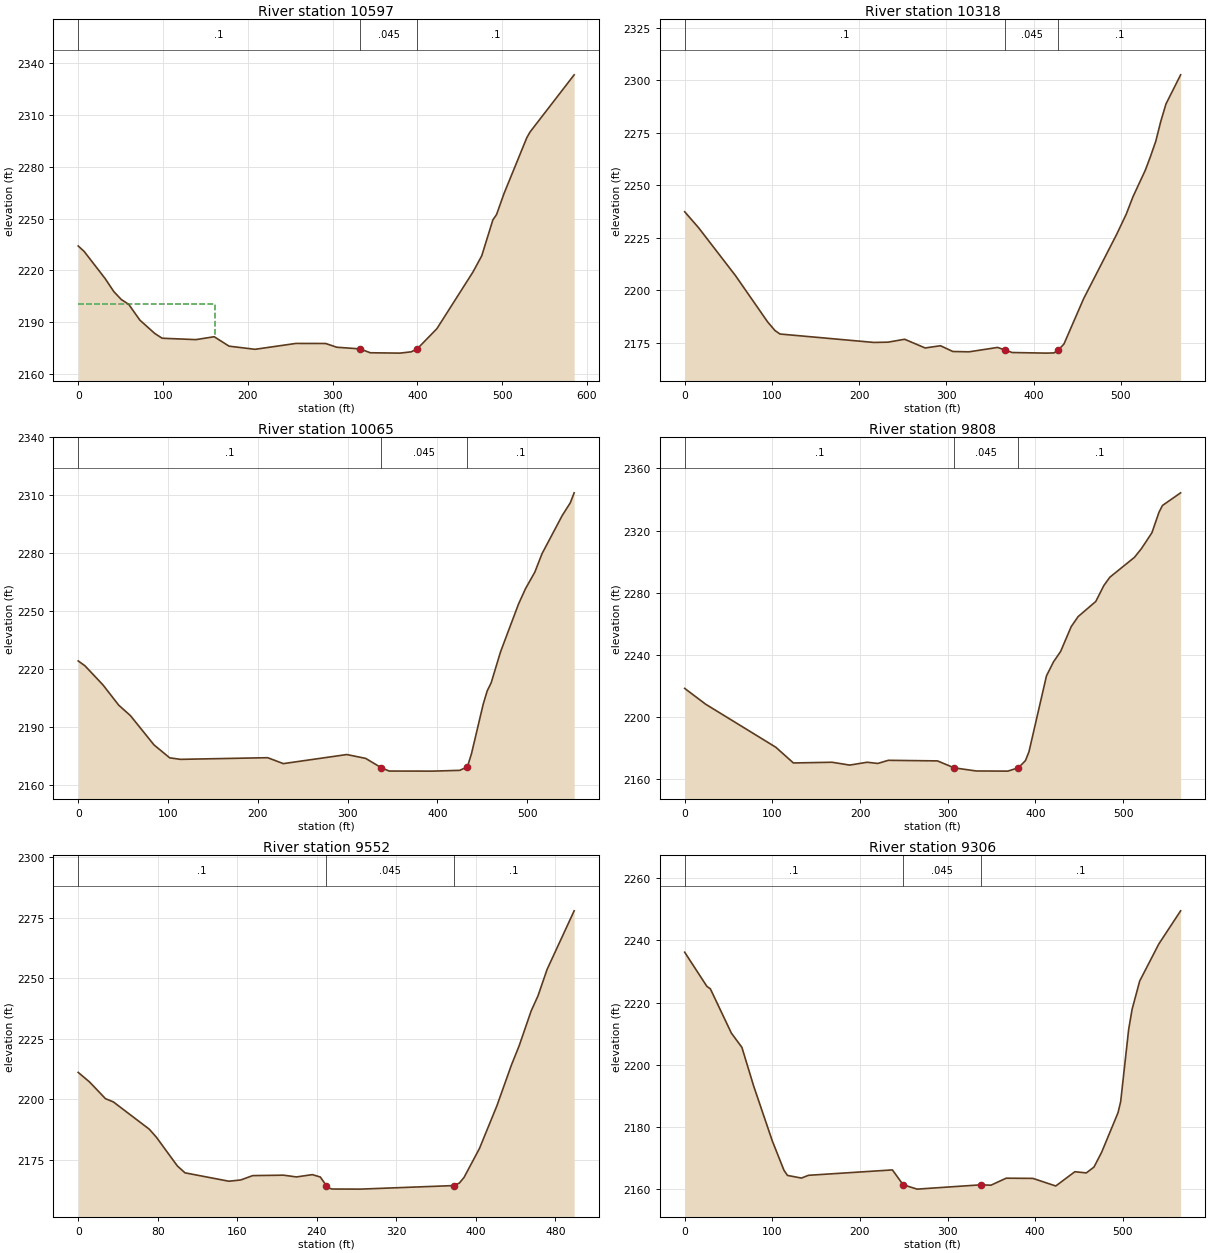
Type RM Length L Ch R = 1 ,10597   ,279.9,279.9,279.9
XS GIS Cut Line= 2
2379097.80598659720320.1701937222379631.61805428720559.378431601
#Sta/Elev= 30
       0 2234.16       7    2231    31.8 2215.25      42 2207.73    50.8 2203.16
    59.6 2200.34    72.7 2191.23    90.3 2183.49      99 2180.73   138.8 2179.92
   160.4  2181.6   177.9 2176.14   208.6 2174.31   256.8 2177.72   291.9 2177.68
     305 2175.51   332.5 2174.55   344.5 2172.31   379.6  2172.1   392.7 2172.85
   399.8 2174.51   423.1 2186.27   465.7 2219.12     476 2228.46   489.1 2249.22
   493.5 2252.39   502.3 2264.55   529.2 2296.91     533 2300.18     585 2333.26
#Mann= 3 ,-1,0
       0      .1       0   332.5    .045       0   399.8      .1       0
#XS Ineff= 2 , 0
          161.07 2200.82
Permanent Ineff=
       F       F
Bank Sta=332.5,399.8
XS Rating Curve= 0 ,0
Exp/Cntr(USF)=0,0
Exp/Cntr=0.3,0.1

Type RM Length L Ch R = 1 ,10318   ,252.9,252.9,252.9
XS GIS Cut Line= 2
2379008.50323315720410.3853391242379395.59296143720826.851664698
#Sta/Elev= 30
       0 2237.39    15.9 2229.81    58.3 2206.95    95.1 2184.94   103.6  2180.8
   109.3 2179.17   216.9 2175.16   233.2 2175.29   252.2 2176.67   275.7 2172.53
   293.3 2173.59   307.4 2170.85     326 2170.69   358.8 2172.79   366.9 2171.58
   375.5 2170.36     415 2170.07   423.5 2170.18   428.4 2171.61   434.8 2174.38
   457.4    2196   495.3 2226.66   506.2 2236.19     514 2244.55   528.1 2257.16
   534.2  2263.9   540.1 2270.93   545.9  2280.5   551.8  2288.7   568.6 2302.59
#Mann= 3 ,-1,0
       0      .1       0   366.9    .045       0   428.4      .1       0
Bank Sta=366.9,428.4
XS Rating Curve= 0 ,0
Exp/Cntr=0.3,0.1

Type RM Length L Ch R = 1 ,10065   ,256.3,256.3,256.3
XS GIS Cut Line= 2
2378911.47535919 720483.838988062379133.05772691720989.953259784
#Sta/Elev= 30
       0 2224.11     7.6 2221.55    27.7 2211.61    45.1  2201.2    58.2 2195.74
    84.4  2180.6   101.9 2173.87   113.9 2173.09   211.1 2173.94   228.5 2170.87
   299.2 2175.58   320.2 2173.59   337.7 2168.73   346.4 2167.02   394.5 2166.98
     425 2167.38   432.8 2169.05   433.8 2169.55   438.1 2175.97   451.2 2201.71
   455.6 2208.54     460  2212.7   470.5 2228.84   490.5 2253.58   498.3 2261.57
   508.7 2270.16   516.7  2279.7   539.1  2299.4   548.2 2306.09   552.5 2311.26
#Mann= 3 ,-1,0
       0      .1       0   337.7    .045       0   432.8      .1       0
Bank Sta=337.7,432.8
XS Rating Curve= 0 ,0
Exp/Cntr(USF)=0,0
Exp/Cntr=0.3,0.1

Type RM Length L Ch R = 1 ,9808    ,256.7,256.7,256.7
XS GIS Cut Line= 2
 2378789.4839788720509.474572272 2378829.0700212721073.828250521
#Sta/Elev= 30
       0 2218.26    23.8 2208.11     104 2180.31     124  2170.2   168.1 2170.65
   188.2 2168.82   208.2 2170.66   220.2 2169.88   232.3  2171.9   288.4 2171.52
   307.3 2167.06   332.5 2165.03   368.6 2164.93   380.7 2167.11   388.7 2171.71
   392.7 2177.37   412.7 2226.34   420.7 2235.36   428.8 2242.03   440.9 2258.06
   448.8 2264.53   468.9 2274.26   478.1  2284.5   484.9 2289.86     513  2302.7
     521 2308.33     533 2318.62     541 2331.72     545 2336.14   565.7 2344.29
#Mann= 3 ,-1,0
       0      .1       0   307.3    .045       0   380.7      .1       0
Bank Sta=307.3,380.7
XS Rating Curve= 0 ,0
Exp/Cntr=0.3,0.1

Type RM Length L Ch R = 1 ,9552    ,246.2,246.2,246.2
XS GIS Cut Line= 2
2378548.88603019720541.752561442 2378563.9939189721040.312888811
#Sta/Elev= 30
       0 2211.05    11.4  2207.1    27.4  2200.2    35.4 2198.84    71.5 2187.57
    78.6 2184.27    99.7  2172.4   107.4 2169.54   151.5 2166.07   163.5 2166.59
   175.5 2168.39   206.5 2168.57   219.5 2167.84   235.5 2168.79   243.5 2167.81
   249.5 2164.28   251.5 2163.29   255.5 2162.84   283.6  2162.8  377.85 2164.27
   383.3 2165.29   388.1 2167.67   403.6 2179.64   421.1 2197.25   435.6 2213.98
   443.6 2222.19   455.6 2236.51   462.4 2242.66   471.6 2253.64   498.8 2277.84
#Mann= 3 ,-1,0
       0      .1       0   249.5    .045       0  377.85      .1       0
Bank Sta=249.5,377.85
XS Rating Curve= 0 ,0
Exp/Cntr(USF)=0,0
Exp/Cntr=0.3,0.1

Type RM Length L Ch R = 1 ,9306    ,310,310,310
XS GIS Cut Line= 3
2378330.13217338720507.8687842252378332.82709274720855.636499187
2378419.21376212721056.025021802
#Sta/Elev= 30
       0 2236.17    25.3 2225.22    29.3 2224.42    53.3 2210.19    65.3 2205.62
    78.7 2193.23     100 2175.58   113.3 2166.16   117.3 2164.49   133.3 2163.64
   141.3 2164.53   237.1 2166.26   249.3 2161.49   265.3 2160.09   337.9 2161.47
   349.5 2161.35   366.9  2163.6   397.4 2163.54   423.5  2161.1   445.3 2165.68
   458.4  2165.3   467.1 2167.17   475.8 2171.89   494.6 2184.65   497.6 2188.23
   506.7 2211.36   510.6 2217.81   519.3 2226.92   541.1 2238.81     566 2249.46
#Mann= 3 ,-1,0
       0      .1       0   249.3    .045       0   337.9      .1       0
Bank Sta=249.3,337.9
XS Rating Curve= 0 ,0
Exp/Cntr=0.3,0.1

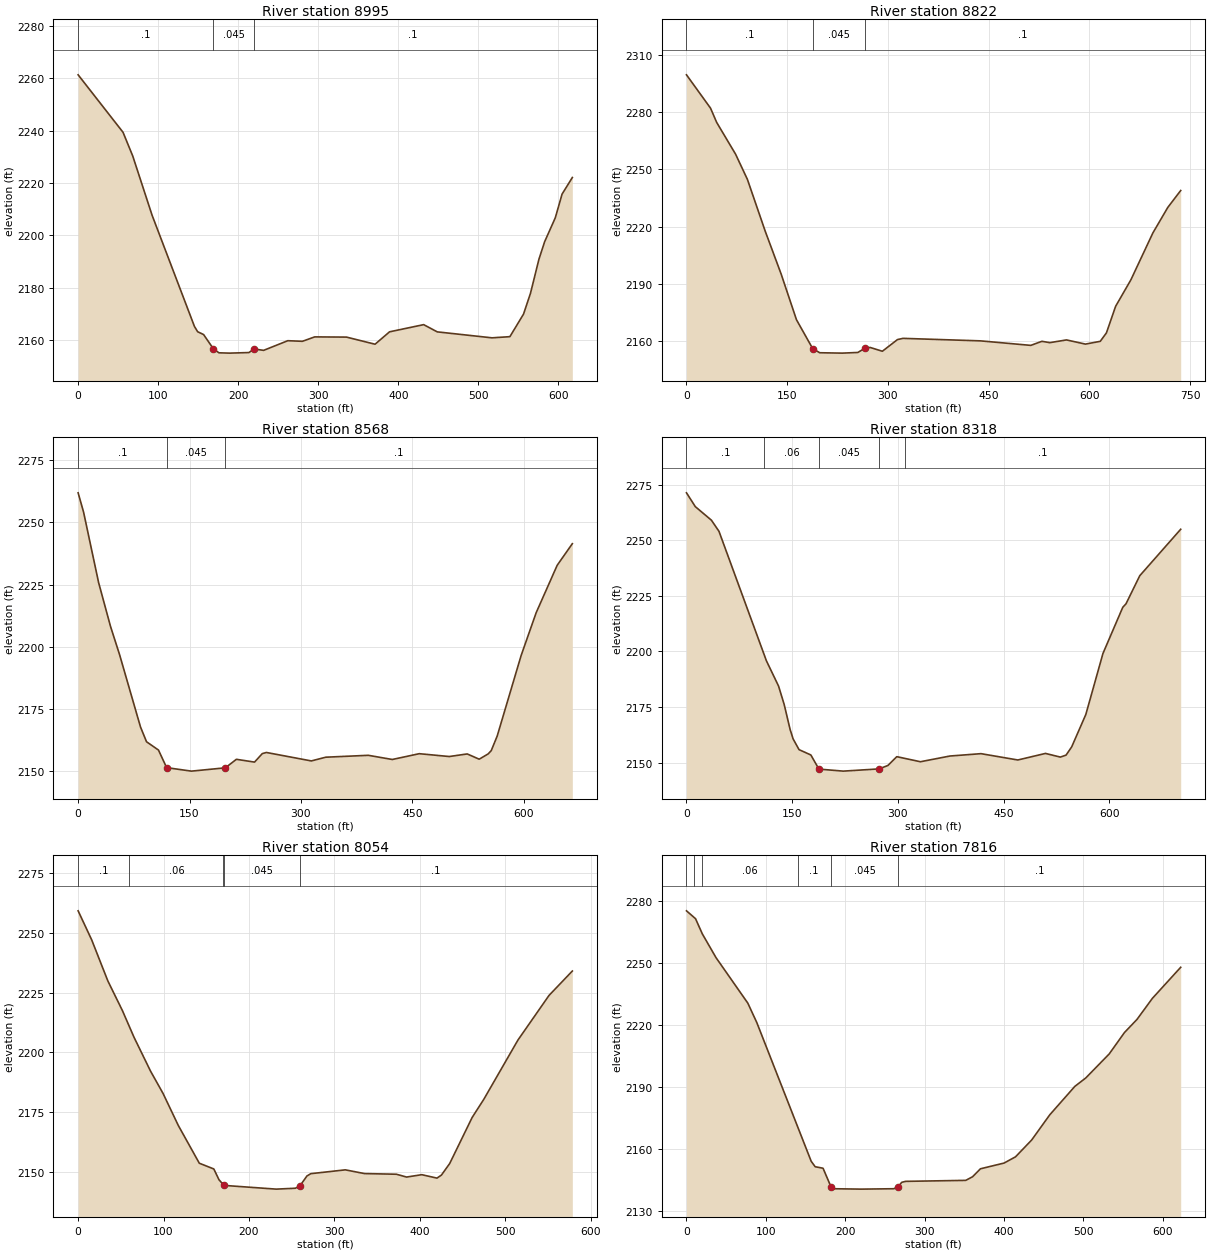
Type RM Length L Ch R = 1 ,8995    ,173.6,173.6,173.6
XS GIS Cut Line= 2
2377884.13892704720660.0976896552378347.44751409721068.010684776
#Sta/Elev= 30
       0 2261.38    56.1 2239.39    68.2 2230.34    92.4 2207.65   145.3 2165.12
   149.3 2163.09   156.7 2162.02  168.892156.587   175.9 2155.03   189.3 2154.91
   213.4 2155.13   219.6  2156.5   231.7 2155.97   261.9 2159.66   280.1 2159.43
   295.5 2161.12   335.2 2161.04   370.9 2158.32     389 2163.06   431.6 2165.81
   448.6 2163.04     517 2160.76   539.3 2161.21   556.3 2169.82     565 2177.78
   575.6 2190.85   582.7 2197.53     596 2206.67   604.5 2215.76   617.3 2222.09
#Mann= 3 ,-1,0
       0      .1       0  168.89    .045       0   219.6      .1       0
Bank Sta=168.89,219.6
XS Rating Curve= 0 ,0
Exp/Cntr(USF)=0,0
Exp/Cntr=0.3,0.1

Type RM Length L Ch R = 1 ,8822    ,254.1,254.1,254.1
XS GIS Cut Line= 2
2377716.82630303720805.2209209212378360.98148389721161.179595184
#Sta/Elev= 30
       0  2299.6    35.8 2282.13      45 2274.64    73.1 2258.03    90.7 2244.83
   117.2 2217.71   140.9 2195.28   163.8 2171.26   187.9 2156.17   198.4 2153.97
     232 2153.77   255.2 2154.12   265.52156.287   273.5 2156.75   291.7 2154.75
   314.2 2160.87   322.5 2161.51     438 2160.19   512.7 2157.83   529.3 2159.96
   541.1 2159.26   565.9 2160.69   594.1  2158.5   616.2 2159.95   625.4 2164.39
   639.1 2178.32   661.8 2192.17   694.6 2216.77   716.8 2230.13     736 2238.98
#Mann= 3 ,-1,0
       0      .1       0   187.9    .045       0   265.5      .1       0
Bank Sta=187.9,265.5
XS Rating Curve= 0 ,0
Exp/Cntr=0.3,0.1

Type RM Length L Ch R = 1 ,8568    ,249.8,249.8,249.8
XS GIS Cut Line= 2
2377692.93494437721133.6372409982378352.39428648721222.018389941
#Sta/Elev= 30
       0 2261.92     7.3 2254.22    27.6 2225.81    43.6 2208.21    55.7 2196.96
      84 2167.75    92.1 2161.82   108.2 2158.48  119.172151.407   152.6 2150.01
   198.2 2151.34   213.1 2154.76   237.5 2153.64     248 2157.06   253.5 2157.51
     314 2154.11   333.4 2155.61   390.7 2156.37     423 2154.69   459.3 2157.02
   499.7 2155.88   523.9 2156.92     540 2154.81   552.1 2156.94   556.2 2158.25
   564.2 2164.09   596.5 2196.54   616.7 2213.71     645 2232.78   665.4 2241.47
#Mann= 3 ,-1,0
       0      .1       0  119.17    .045       0   198.2      .1       0
Bank Sta=119.17,198.2
XS Rating Curve= 0 ,0
Exp/Cntr(USF)=0,0
Exp/Cntr=0.3,0.1

Type RM Length L Ch R = 1 ,8318    ,264.2,264.2,264.2
XS GIS Cut Line= 3
 2377704.2706645721465.8785379112378049.49905402721354.144296778
2378385.96518711721317.348279856
#Sta/Elev= 30
       0 2271.31    12.5 2265.11    35.4 2258.99    46.1 2254.01   113.4  2195.8
   130.7 2184.39   138.6 2176.19     147 2164.97   151.3 2160.68   159.7 2155.85
   176.5 2153.45   187.9  2147.1   222.5 2146.19   273.2 2147.19   285.8 2148.73
   298.4 2152.69     332 2150.41   373.8 2152.98   417.9 2154.04   470.2  2151.2
   509.4 2154.15   530.5  2152.5   538.6 2153.38   546.6 2157.09   566.7 2171.69
     591 2199.11   619.1 2219.84   623.7 2221.43   643.2 2234.04   701.3 2254.93
#Mann= 5 ,-1,0
       0      .1       0     110     .06       0   187.9    .045       0
   273.2     .06       0     310      .1       0
Bank Sta=187.9,273.2
XS Rating Curve= 0 ,0
Exp/Cntr=0.3,0.1

Type RM Length L Ch R = 1 ,8054    ,238.1,238.1,238.1
XS GIS Cut Line= 2
 2377850.0514605721729.1222387372378364.47507102721463.978791909
#Sta/Elev= 30
       0 2259.11    15.9 2246.97    34.8 2229.84    51.9 2217.42    65.4 2206.35
    84.7 2192.24    99.5 2182.81   117.3 2169.48   141.9 2153.71   158.9 2151.31
   164.9 2146.83   170.8 2144.45   231.9 2142.89   254.4 2143.26   259.9 2144.33
   267.9 2148.37   272.4 2149.34   312.9 2150.94   335.4 2149.38   372.7 2149.11
   384.6 2147.93   402.4 2148.92   420.2 2147.49   425.4 2148.75   435.1 2153.59
   461.4 2172.82   474.9 2180.32     515 2205.14   551.4 2223.78   578.7 2233.97
#Mann= 5 ,-1,0
       0      .1       0      60     .06       0     170      .1       0
   170.8    .045       0   259.9      .1       0
Bank Sta=170.8,259.9
XS Rating Curve= 0 ,0
Exp/Cntr(USF)=0,0
Exp/Cntr=0.3,0.1

Type RM Length L Ch R = 1 ,7816    ,256.2,256.2,256.2
XS GIS Cut Line= 3
2377989.40918726721962.4018700872378345.59541389721701.191623494
2378494.36514219721597.736523698
#Sta/Elev= 30
       0  2275.3    11.4  2271.5      20 2264.11    37.2 2252.65    77.3 2230.62
    88.7 2221.14   157.2 2154.05   162.2 2151.43   172.1 2150.71     182 2141.83
     187 2140.77   220.3 2140.59   261.4 2140.78  266.862141.811   271.3 2143.88
   276.2 2144.35     352 2144.83   360.6 2146.59   370.5 2150.43   400.3 2153.21
   414.7 2156.22     435 2164.34   457.9 2176.58   489.5 2190.33   503.3 2194.42
   532.8 2206.03     552 2216.38   567.8 2222.73   587.2 2232.93   622.9 2247.97
#Mann= 6 ,-1,0
       0     .08       0      10      .1       0      20     .06       0
     140      .1       0     182    .045       0  266.86      .1       0
Bank Sta=182,266.86
XS Rating Curve= 0 ,0
Exp/Cntr=0.3,0.1

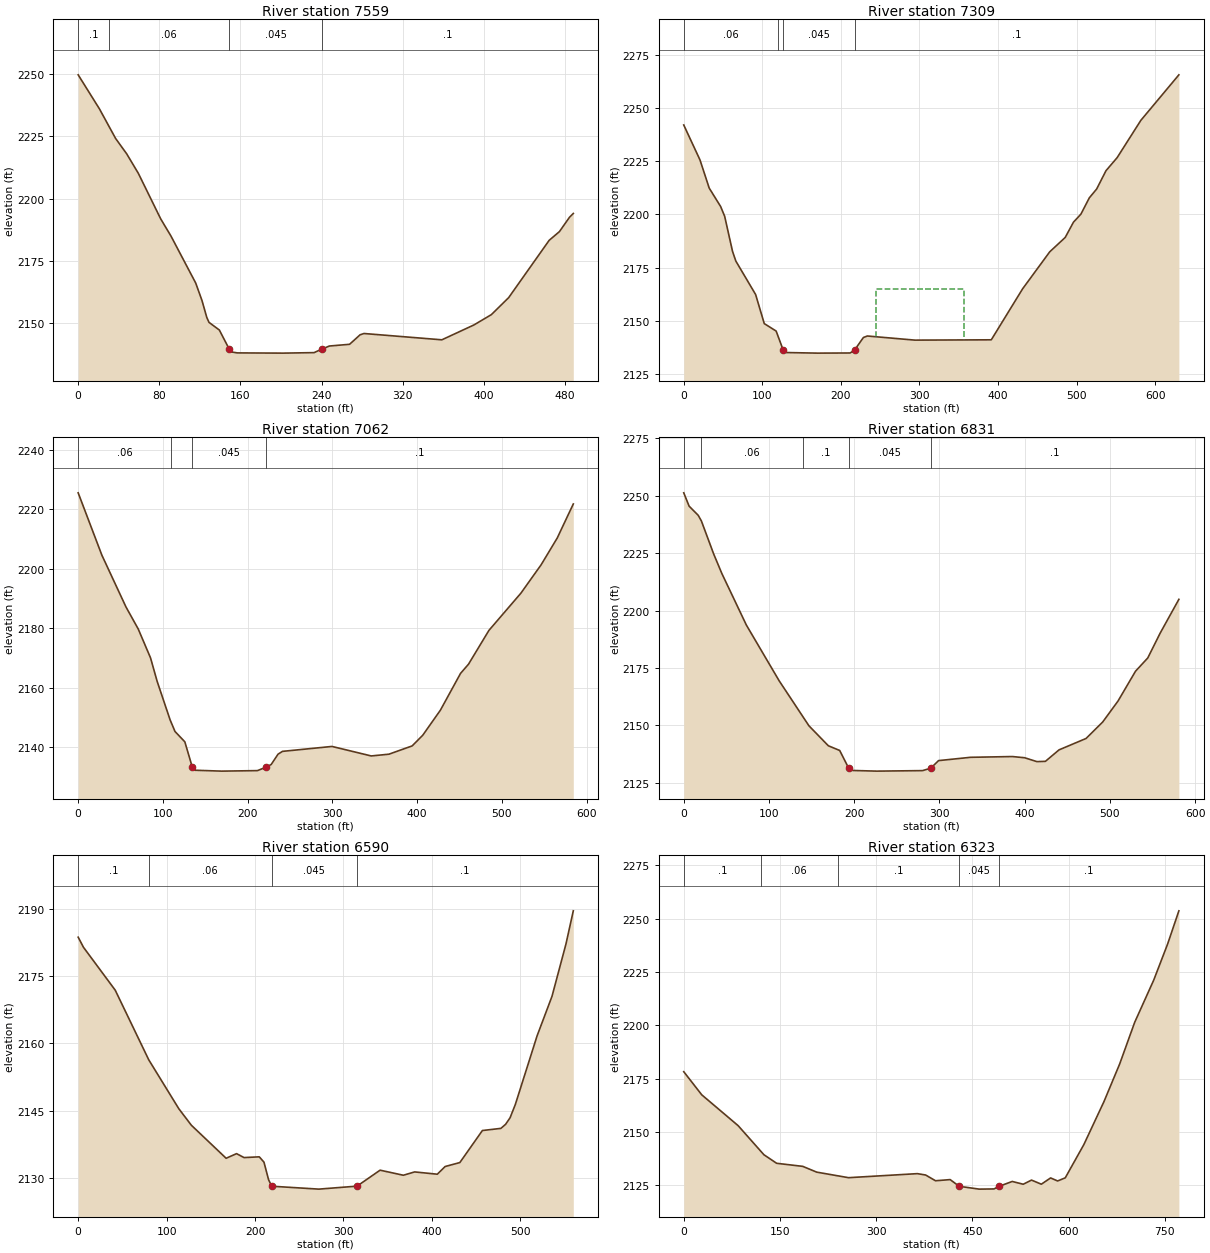
Type RM Length L Ch R = 1 ,7559    ,250.1,250.1,250.1
XS GIS Cut Line= 2
2378221.70552272722177.8265333692378518.57553584721790.309188005
#Sta/Elev= 30
       0 2249.65      21 2235.97    36.9 2224.13    47.9 2217.92    59.3 2210.15
    81.4 2191.84    91.5 2184.97   115.9 2166.11   122.1 2159.09   126.8 2152.34
     129 2150.34   139.2 2147.27   148.8 2139.72     152 2138.41     157 2138.09
   201.9    2138   232.6  2138.2   240.8 2139.72   247.7 2140.85   267.6 2141.54
     278 2145.36   281.8 2145.87   358.6 2143.34   390.2  2149.3   407.4 2153.44
   424.5 2160.28   464.4 2183.25   474.5 2186.74   484.4 2192.48   488.2 2194.03
#Mann= 4 ,-1,0
       0      .1       0      30     .06       0   148.8    .045       0
   240.8      .1       0
Bank Sta=148.8,240.8
XS Rating Curve= 0 ,0
Exp/Cntr(USF)=0,0
Exp/Cntr=0.3,0.1

Type RM Length L Ch R = 1 ,7309    ,247.8,247.8,247.8
XS GIS Cut Line= 2
2378424.39414219722322.406069765     2378808.722      721822.874
#Sta/Elev= 30
       0 2242.01    20.7 2225.56    32.4 2212.36      47 2203.66    52.1 2199.07
    62.1  2182.6    66.3 2178.05    91.5 2162.32   102.5 2148.65   117.6 2145.14
  126.482136.333   130.8 2135.04   170.2 2134.77   211.8 2134.84   217.5 2136.24
   228.7 2142.11   233.7 2142.82   294.3 2140.88   391.5 2141.03   431.4 2165.02
   465.9 2182.39   485.6 2189.15   496.1 2196.32   505.6 2200.12   516.3 2207.77
   525.6  2211.9   537.5 2220.52   551.7 2226.66   581.9  2244.2   630.3 2265.59
#Mann= 4 ,-1,0
       0     .06       0     120      .1       0  126.48    .045       0
   217.5      .1       0
#XS Ineff= 1 ,-1
   244.3  357.172164.808
Permanent Ineff=
       F
Bank Sta=126.48,217.5
XS Rating Curve= 0 ,0
Exp/Cntr=0.3,0.1

Type RM Length L Ch R = 1 ,7062    ,230.9,230.9,230.9
XS GIS Cut Line= 2
2378633.73629829722480.7407036342378949.86886951721989.205544514
#Sta/Elev= 30
       0 2225.56      28 2204.56    56.4 2187.16    70.9 2179.72    85.4 2170.01
    93.2 2162.12   108.5 2149.15   114.3 2145.22   125.9 2141.74   134.6 2133.32
   137.6 2132.18   169.3 2131.88   211.6 2132.05   221.4 2133.18   227.8 2134.11
   235.9 2137.58   241.1 2138.53   299.6 2140.19   345.9 2136.99   366.8 2137.58
   394.2 2140.37   406.7 2143.96   427.5 2152.38   451.3 2164.77   460.8 2167.91
   484.8 2179.25   522.6  2191.8   546.4 2201.33   565.4 2210.33   584.4 2221.81
#Mann= 4 ,-1,0
       0     .06       0     110      .1       0   134.6    .045       0
   221.4      .1       0
Bank Sta=134.6,221.4
XS Rating Curve= 0 ,0
Exp/Cntr(USF)=0,0
Exp/Cntr=0.3,0.1

Type RM Length L Ch R = 1 ,6831    ,240.3,240.3,240.3
XS GIS Cut Line= 2
2378786.75253192 722662.38596889 2379108.7770524722178.815773034
#Sta/Elev= 30
       0 2251.27     6.3 2245.46      17 2241.46    20.7 2239.01    35.1 2224.64
    44.7 2216.13    73.5 2193.64     112 2169.35   146.9 2149.77   169.7 2141.06
     183 2139.02   193.7 2131.17   198.5  2130.3   226.3 2130.02   280.2 2130.24
   289.8 2131.29     299  2134.6   336.5 2136.04   385.6 2136.37     400 2135.85
   414.4 2134.16   424.4 2134.29   440.4 2139.29   472.1 2144.25   491.6 2151.42
   509.6 2160.57   530.1 2173.54   544.5 2179.33   558.9 2190.05     581 2204.87
#Mann= 5 ,-1,0
       0      .1       0      20     .06       0     140      .1       0
   193.7    .045       0   289.8      .1       0
Bank Sta=193.7,289.8
XS Rating Curve= 0 ,0
Exp/Cntr=0.3,0.1

Type RM Length L Ch R = 1 ,6590    ,267,267,267
XS GIS Cut Line= 2
2378939.67104463722809.1106647062379302.71361029722382.841584805
#Sta/Elev= 30
       0 2183.72       6 2181.46    41.9 2171.89    79.8 2156.35   113.8 2145.43
     128 2141.74   167.3 2134.37   179.1  2135.4   187.6 2134.52   204.8 2134.69
   210.1  2133.5   215.3 2129.59   218.8 2128.13   272.2 2127.48   315.4 2128.15
   341.4 2131.71   367.7 2130.58   380.5 2131.32   406.1 2130.81     415 2132.53
   431.6 2133.41   457.1 2140.56     478 2141.04   483.3 2141.94   488.4 2143.41
   494.3 2146.35     519 2161.72   535.8 2170.51   551.6  2182.2   559.9  2189.6
#Mann= 4 ,-1,0
       0      .1       0      80     .06       0   218.8    .045       0
   315.4      .1       0
Bank Sta=218.8,315.4
XS Rating Curve= 0 ,0
Exp/Cntr(USF)=0,0
Exp/Cntr=0.3,0.1

Type RM Length L Ch R = 1 ,6323    ,312.1,312.1,312.1
XS GIS Cut Line= 2
     2379038.864      723130.9042379516.46250081722524.737898536
#Sta/Elev= 30
       0 2178.28      28 2167.47    84.8    2153   124.9  2139.4   144.8 2135.38
   185.5 2133.94   207.2 2131.24   256.8 2128.64   364.1 2130.53     377 2129.89
   392.4  2127.2   415.2 2127.74   429.4  2124.6   460.5 2123.28   483.5 2123.37
  491.912124.644     512 2126.87   529.1 2125.57     542 2127.51   557.3 2125.59
   571.8 2128.52   582.7  2127.1   594.6 2128.57   623.5 2144.09   654.9 2164.25
   679.5 2181.97   702.8  2201.4   732.5 2221.19   754.1 2238.05   771.7 2253.63
#Mann= 5 ,-1,0
       0      .1       0     120     .06       0     240      .1       0
   429.4    .045       0  491.91      .1       0
Bank Sta=429.4,491.91
XS Rating Curve= 0 ,0
Exp/Cntr=0.3,0.1

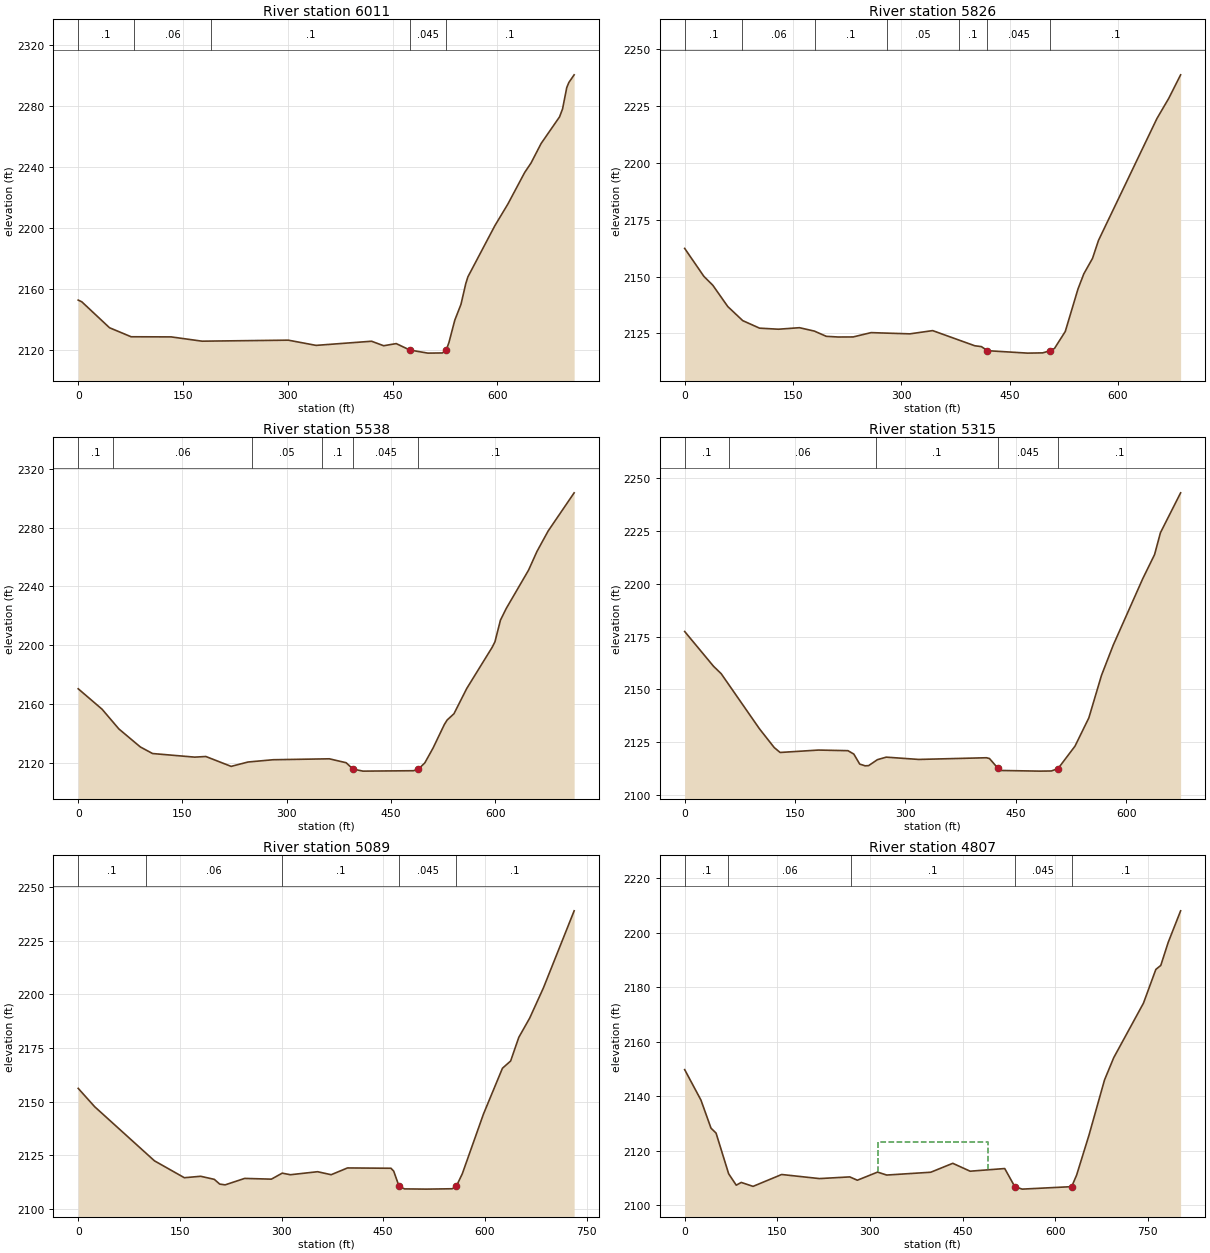
Type RM Length L Ch R = 1 ,6011    ,185.1,185.1,185.1
XS GIS Cut Line= 2
2379111.51652416723165.1920804782379755.11258313722866.055884056
#Sta/Elev= 30
       0 2152.83     5.1 2151.74    44.8 2134.75    75.7 2128.84   133.1 2128.75
   177.2 2125.95   300.7 2126.61   340.4  2123.2   419.8 2125.91   437.1 2122.97
   455.1 2124.37   474.5 2120.15   500.4 2118.13   521.2 2118.25  526.552120.095
   530.5 2125.03   538.9 2139.71   547.7 2149.99   554.6  2163.6   557.6 2168.01
   596.2 2201.51   614.8 2215.66   638.9 2236.36   647.9 2242.48   662.4 2255.32
   688.8 2272.77   693.1 2277.96   699.1 2291.91   702.1 2295.26   709.7 2300.29
#Mann= 5 ,-1,0
       0      .1       0      80     .06       0     190      .1       0
   474.5    .045       0  526.55      .1       0
Bank Sta=474.5,526.55
XS Rating Curve= 0 ,0
Exp/Cntr(USF)=0,0
Exp/Cntr=0.3,0.1

Type RM Length L Ch R = 1 ,5826    ,287.8,287.8,287.8
XS GIS Cut Line= 3
     2379110.449723250.0762715052379495.37755646723148.867514336
2379780.52812637723101.731456991
#Sta/Elev= 30
       0 2162.37    26.6 2150.07      39 2146.14    59.7 2136.77    80.4 2130.57
   103.7 2127.25   129.9 2126.78     159 2127.45   179.6 2125.96   196.2 2123.65
   212.7 2123.35   233.4 2123.38   258.2 2125.28     312 2124.74   343.5 2126.17
   401.9 2119.49     411 2119.12   419.3 2117.33     475 2116.25   495.9 2116.36
   506.2  2117.3   512.3 2118.32   527.2 2125.77   544.8 2144.47   552.9 2151.17
     565 2158.01   573.2 2165.87   654.2 2219.59   670.5 2228.43     687 2238.83
#Mann= 7 ,-1,0
       0      .1       0      80     .06       0     180      .1       0
     280     .05       0     380      .1       0   419.3    .045       0
   506.2      .1       0
Bank Sta=419.3,506.2
XS Rating Curve= 0 ,0
Exp/Cntr=0.3,0.1

Type RM Length L Ch R = 1 ,5538    ,223.3,223.3,223.3
XS GIS Cut Line= 2
2379134.17835722723475.6591934312379841.22754876723380.479494569
#Sta/Elev= 30
       0 2170.21    34.3 2156.31    58.5 2142.86    89.4 2130.58     107 2126.11
   167.5 2123.66   183.6 2124.09     220 2117.36   244.2 2120.33   280.5 2121.89
   361.2 2122.52   385.4 2119.85   395.3 2115.49   409.7 2114.13   482.3  2114.4
   489.1 2115.42   498.5 2119.68   510.6 2129.99   526.7  2145.9   530.7 2148.94
   540.5  2153.2   558.9 2170.42   595.3 2198.33   599.4 2202.11   607.4 2216.97
   615.8 2224.98   647.8 2250.99   659.9 2263.73     676 2277.67   713.4 2303.66
#Mann= 6 ,-1,0
       0      .1       0      50     .06       0     250     .05       0
     350      .1       0   395.3    .045       0   489.1      .1       0
Bank Sta=395.3,489.1
XS Rating Curve= 0 ,0
Exp/Cntr(USF)=0,0
Exp/Cntr=0.3,0.1

Type RM Length L Ch R = 1 ,5315    ,226.5,226.5,226.5
XS GIS Cut Line= 2
     2379122.683      723665.617 2379795.5306757723629.224397344
#Sta/Elev= 30
       0 2177.37    39.2 2160.95    49.6 2157.45   101.6 2131.42   121.7 2122.54
   129.7 2120.23   181.8 2121.37   221.8 2121.08   229.8 2119.48   237.8 2114.75
   245.1 2113.93   249.9 2114.02   261.9 2116.84   273.9 2118.02     318 2116.94
   410.1 2117.74   414.1 2117.37  425.672112.743   430.1 2111.72   482.2 2111.42
   498.2 2111.49   507.3 2112.64   530.3 2123.22   549.1 2136.57   566.3 2156.66
   582.3 2170.98   622.4 2202.36   638.4  2213.7   646.4 2224.05   673.8 2242.88
#Mann= 5 ,-1,0
       0      .1       0      60     .06       0     260      .1       0
  425.67    .045       0   507.3      .1       0
Bank Sta=425.67,507.3
XS Rating Curve= 0 ,0
Exp/Cntr=0.3,0.1

Type RM Length L Ch R = 1 ,5089    ,281.3,281.3,281.3
XS GIS Cut Line= 2
2379083.96291439723830.1634263692379813.67393899723884.551825718
#Sta/Elev= 30
       0 2156.16    24.3  2147.6   112.5 2122.37   156.6  2114.5   180.7 2115.17
   200.8 2113.73   208.8 2111.52   216.8 2111.17   245.6 2114.18     285 2113.83
     301 2116.63   313.1 2115.89   353.2  2117.3   373.2  2115.9   397.3 2119.06
   461.5 2118.91   465.5 2117.55   473.4 2110.46   481.5 2109.29   513.6 2109.18
   551.7 2109.35   557.8 2110.47   566.7 2116.36   597.9 2144.19   625.9 2165.54
     638 2168.93     650 2179.92   666.1 2188.93   686.4 2203.04   731.7 2238.94
#Mann= 5 ,-1,0
       0      .1       0     100     .06       0     300      .1       0
   473.4    .045       0   557.8      .1       0
Bank Sta=473.4,557.8
XS Rating Curve= 0 ,0
Exp/Cntr(USF)=0,0
Exp/Cntr=0.3,0.1

Type RM Length L Ch R = 1 ,4807    ,220.2,220.2,220.2
XS GIS Cut Line= 3
2379022.47805629724055.851310635 2379409.7794121      724136.674
2379816.19241766724164.431175122
#Sta/Elev= 30
       0 2149.71    26.3 2138.55    42.6 2128.23    50.8 2126.41    71.2 2111.47
    83.5 2107.28    91.6 2108.29   110.7 2106.84     157  2111.2   218.3  2109.7
   267.3 2110.32   279.6  2109.1   312.3 2112.08   327.1    2111   398.4 2112.03
   434.1 2115.31   462.2 2112.41   518.2 2113.39   534.4 2106.79   546.4 2105.83
   626.6 2106.74   634.6 2110.98   654.6 2125.63   679.8 2145.93   694.7  2154.1
   742.8  2174.1   762.9 2186.51   770.9 2187.98   782.9 2196.44     803 2208.02
#Mann= 5 ,-1,0
       0      .1       0      70     .06       0     270      .1       0
   534.4    .045       0   626.6      .1       0
#XS Ineff= 1 ,-1
  312.97  491.042123.116
Permanent Ineff=
       F
Bank Sta=534.4,626.6
XS Rating Curve= 0 ,0
Exp/Cntr=0.3,0.1

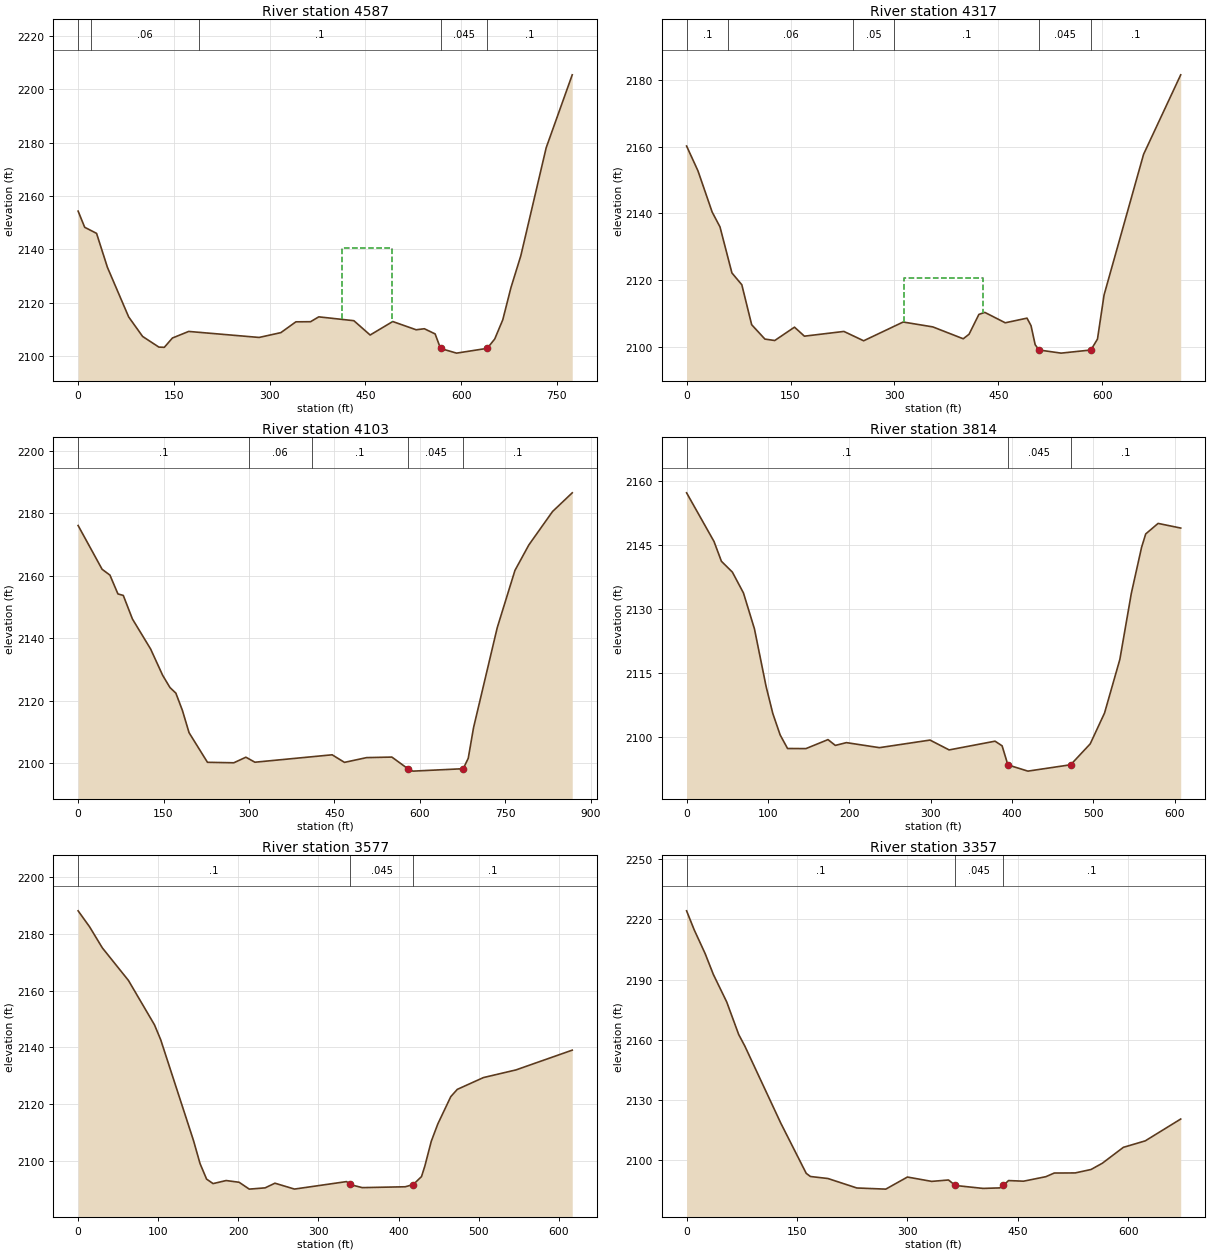
Type RM Length L Ch R = 1 ,4587    ,270.2,270.2,270.2
XS GIS Cut Line= 2
2378972.91993239724163.2923723842379702.63095699724421.637269294
#Sta/Elev= 30
       0 2154.35    10.3  2148.3    28.9 2146.02    45.9 2133.31    79.2 2114.74
     101 2107.44   126.5 2103.45     135 2103.36   147.7 2106.84   173.2 2109.31
   283.5 2107.06   317.6 2108.86   341.2 2112.91   364.1 2112.95     377 2114.77
     432 2113.33   457.5 2107.97   492.9 2113.02   529.6 2109.93   542.4 2110.32
   559.3 2108.38   567.8 2102.93   592.9 2101.19   640.9 2102.98   652.7 2106.49
   665.3 2113.69   678.1 2125.73   693.5 2137.61   733.3 2178.09   774.1 2205.37
#Mann= 5 ,-1,0
       0      .1       0      20     .06       0     190      .1       0
   567.8    .045       0   640.9      .1       0
#XS Ineff= 1 ,-1
  413.74  491.932140.494
Permanent Ineff=
       F
Bank Sta=567.8,640.9
XS Rating Curve= 0 ,0
Exp/Cntr(USF)=0,0
Exp/Cntr=0.3,0.1

Type RM Length L Ch R = 1 ,4317    ,213.4,213.4,213.4
XS GIS Cut Line= 2
2378937.09448445724297.6487004882379537.25036499724682.558515555
#Sta/Elev= 30
       0 2160.21    16.4 2152.79    36.9 2140.43    48.2 2135.98    65.4 2122.19
    79.7 2118.65    93.9 2106.68     113 2102.37   127.2 2101.94   155.7 2105.94
     170 2103.24     227 2104.66   255.5 2101.86   312.5 2107.48   355.3 2106.02
   399.2 2102.46   407.6 2103.82   421.8 2109.77   430.4 2110.36   459.8 2107.25
   491.2 2108.64     497  2106.4     503 2100.69   508.5  2099.1   540.4 2098.16
   583.4  2099.1   592.9 2102.37   602.4 2115.58   659.4 2157.72     713 2181.55
#Mann= 6 ,-1,0
       0      .1       0      60     .06       0     240     .05       0
     300      .1       0   508.5    .045       0   583.4      .1       0
#XS Ineff= 1 ,-1
  313.26  427.932120.631
Permanent Ineff=
       F
Bank Sta=508.5,583.4
XS Rating Curve= 0 ,0
Exp/Cntr=0.3,0.1

Type RM Length L Ch R = 1 ,4103    ,289.4,289.4,289.4
XS GIS Cut Line= 2
2378731.73529505724449.2692554942379482.09376756 724884.88004658
#Sta/Elev= 30
       0 2176.08    42.1 2162.09    55.9 2160.22    69.9 2154.21    79.3 2153.73
    95.4 2146.18   127.3  2136.6   148.5 2128.17   161.2  2124.3   171.6  2122.5
   183.1 2116.98   194.8 2109.85   227.1 2100.38   273.4 2100.23   294.6 2102.01
   310.4 2100.41     446 2102.78   467.7 2100.36   506.5 2101.88   550.9 2102.05
   578.7 2098.37   587.9 2097.56   676.2 2098.33     685 2101.67   694.3 2111.45
   735.9 2143.42     767 2161.72   791.4 2169.87     833 2180.55   867.6 2186.53
#Mann= 5 ,-1,0
       0      .1       0     300     .06       0     410      .1       0
   578.7    .045       0   676.2      .1       0
Bank Sta=578.7,676.2
XS Rating Curve= 0 ,0
Exp/Cntr(USF)=0,0
Exp/Cntr=0.3,0.1

Type RM Length L Ch R = 1 ,3814    ,236.7,236.7,236.7
XS GIS Cut Line= 3
2378710.32338952724783.0578330622379043.44437097724957.930185486
2379239.70360006725079.851588676
#Sta/Elev= 30
       0 2157.21    33.7 2145.79    42.8 2141.14    56.3 2138.59    69.9  2133.7
    83.4 2125.27    97.7 2111.77     106 2105.38     115 2100.37   124.1 2097.18
   146.7 2097.16   173.8 2099.27   182.8 2097.91   196.4 2098.56     237 2097.38
   299.2 2099.16   322.7 2096.85   379.1  2098.9   387.8 2097.81  394.882093.333
   419.5 2091.87   472.1 2093.37   496.1 2098.28   513.7 2105.52   532.5  2118.1
   546.6 2133.61   559.2 2144.41   564.3 2147.56   579.5 2150.03   607.3 2148.94
#Mann= 3 ,-1,0
       0      .1       0  394.88    .045       0   472.1      .1       0
Bank Sta=394.88,472.1
XS Rating Curve= 0 ,0
Exp/Cntr=0.3,0.1

Type RM Length L Ch R = 1 ,3577    ,220.4,220.4,220.4
XS GIS Cut Line= 2
2378618.42612974725260.0592828332379225.25965952725149.268098973
#Sta/Elev= 30
       0 2188.18    14.3 2182.55    30.2 2175.12    62.8 2163.63    95.3 2147.97
   103.1  2142.7   144.1 2107.08   152.2 2099.01   160.4 2093.51   168.5 2091.93
   184.8 2093.01     201  2092.4   213.7 2089.98   233.5 2090.43   245.7 2092.07
   270.1    2090   335.2 2092.64   339.3 2091.62   354.7 2090.51   408.4 2090.81
   418.42091.609   428.7  2094.4   432.8 2098.04   440.9 2106.86   449.1    2113
   465.3 2122.63   473.4 2125.18     506 2129.34   546.6 2132.04   616.9 2139.02
#Mann= 3 ,-1,0
       0      .1       0   339.3    .045       0   418.4      .1       0
Bank Sta=339.3,418.4
XS Rating Curve= 0 ,0
Exp/Cntr(USF)=0,0
Exp/Cntr=0.3,0.1

Type RM Length L Ch R = 1 ,3357    ,306.2,306.2,306.2
XS GIS Cut Line= 3
2378759.76992078725631.4840451712379010.99075122 725452.41803961
2379295.68328703725227.269085461
#Sta/Elev= 30
       0 2224.27    10.3 2214.83    25.1 2203.04    36.4 2192.52    54.5 2178.85
    70.8  2162.6    79.1 2156.86   128.1 2118.31   162.6 2093.32   168.3 2091.76
   192.1 2090.75   231.4 2086.03   270.7 2085.46   300.1 2091.49   333.1 2089.32
   355.9 2090.02   365.3 2087.28   402.8 2085.82   425.6 2086.07  430.572087.299
   437.5 2089.73   457.9 2089.42   488.2 2091.66   499.6 2093.48   528.1 2093.54
   549.7 2095.26     565 2098.38   593.6 2106.31   623.3 2109.53   671.5 2120.42
#Mann= 3 ,-1,0
       0      .1       0   365.3    .045       0  430.57      .1       0
Bank Sta=365.3,430.57
XS Rating Curve= 0 ,0
Exp/Cntr=0.3,0.1