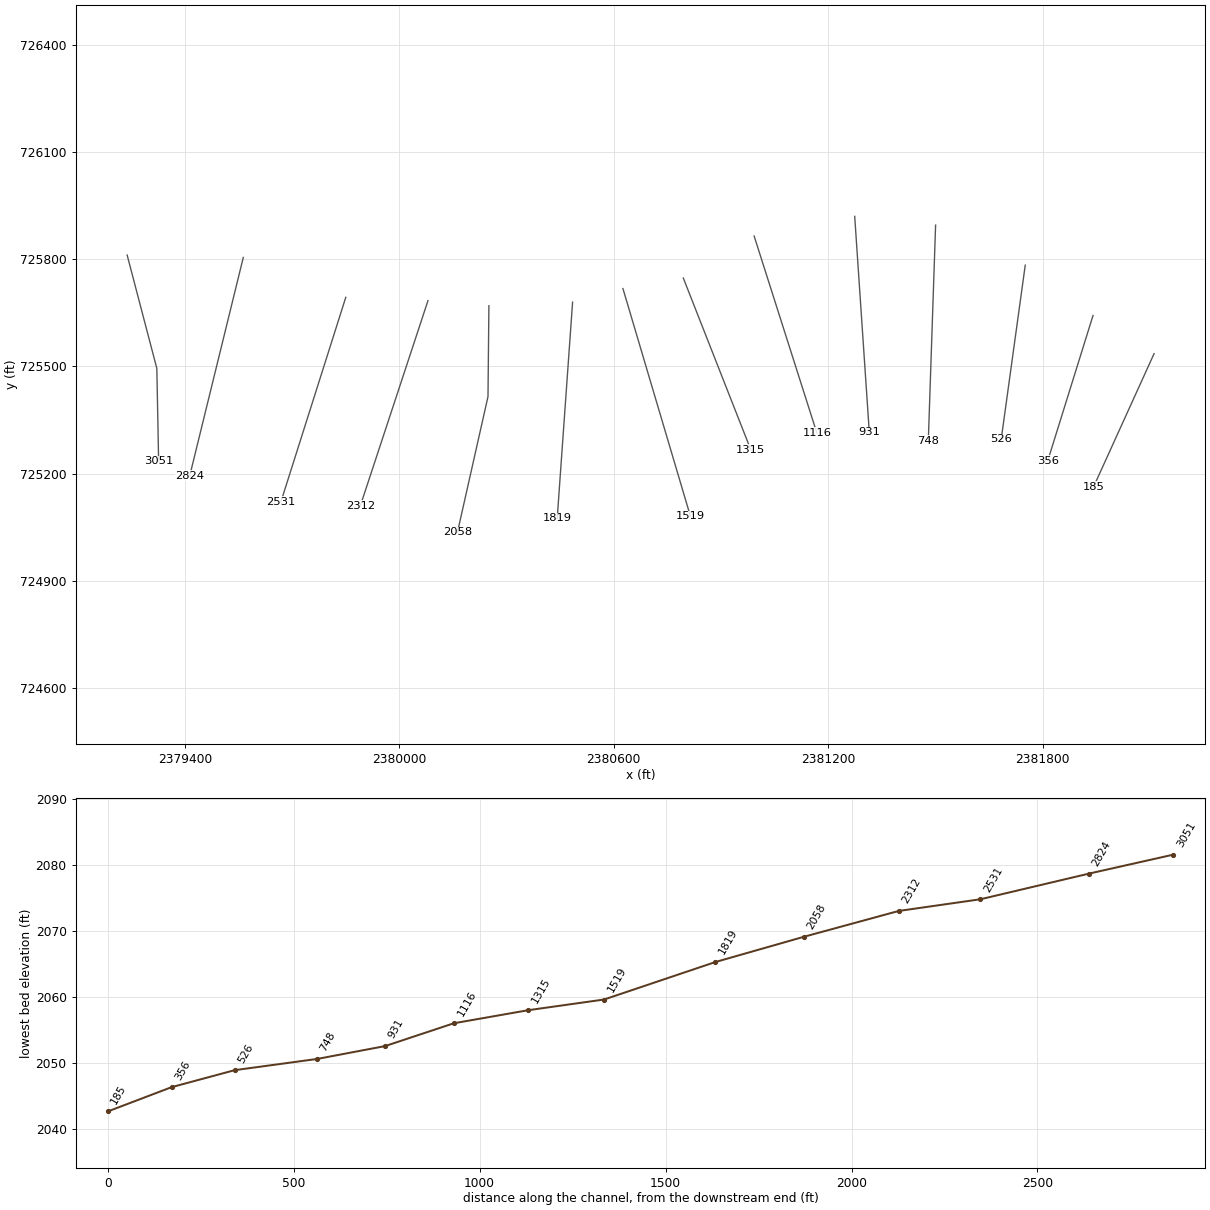
HEC-RAS study LAURELFK.prj: LAURELFK

--- LAURELFK.g01 (geometry) --- (continued)

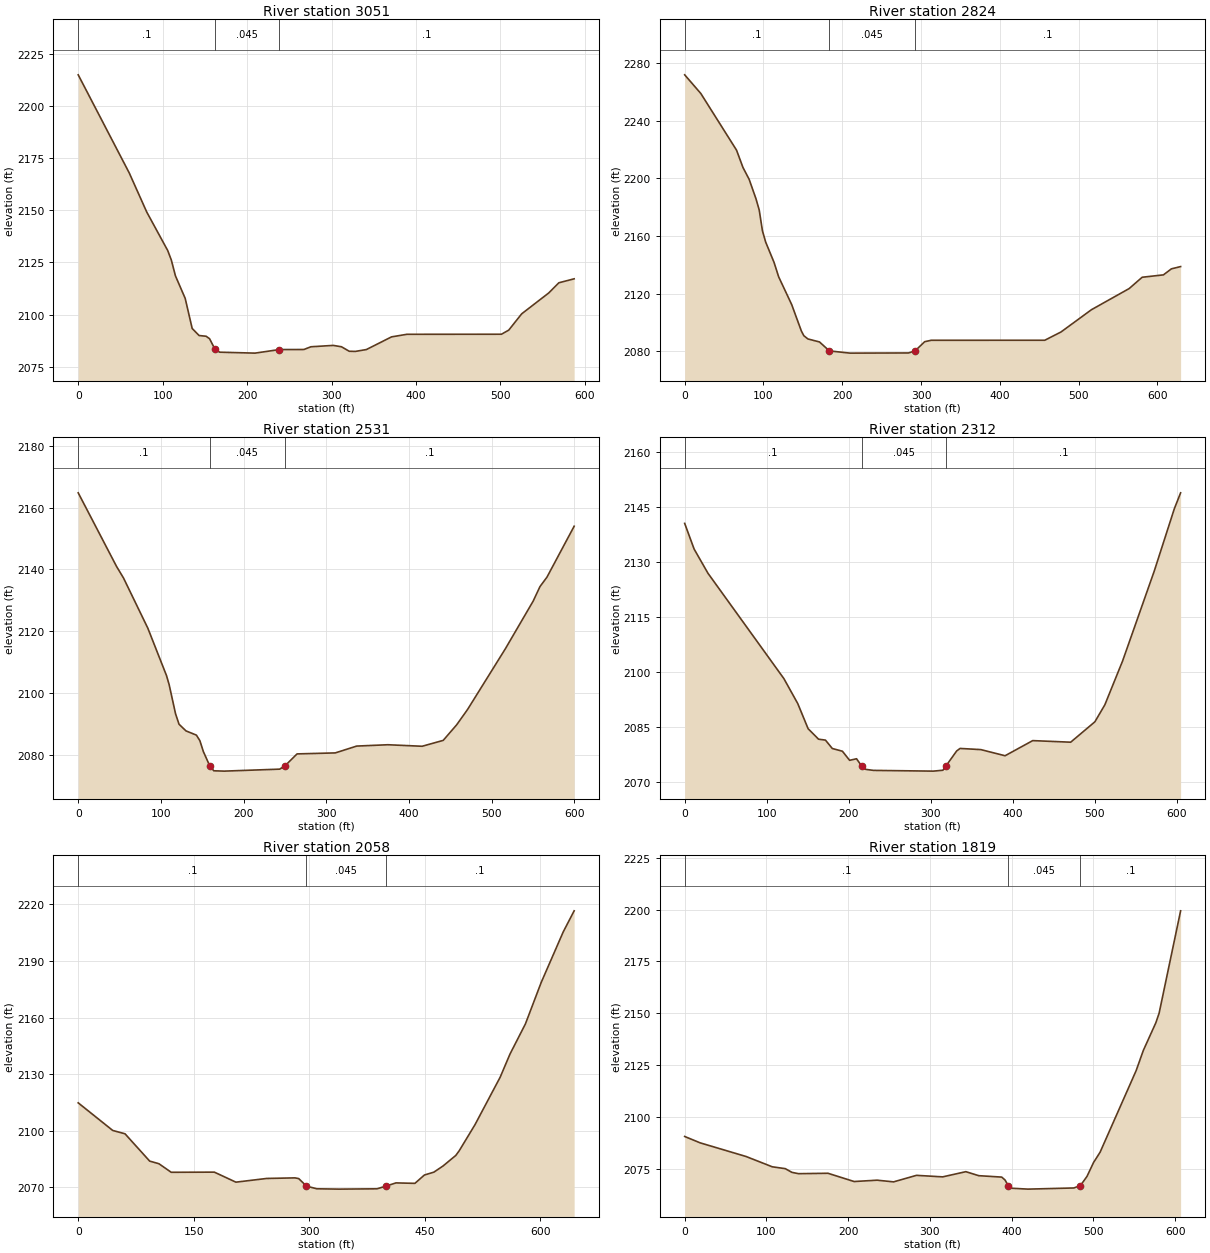
Type RM Length L Ch R = 1 ,3051    ,226.4,226.4,226.4
XS GIS Cut Line= 3
2379238.11241352725811.7415180572379321.20580142725494.475855185
2379326.24176432725235.123765695
#Sta/Elev= 30
       0 2214.84    60.5  2167.8    81.2  2149.1     106 2130.69   110.2 2126.25
   115.2 2118.51   126.7 2107.78     135 2093.33   143.2 2089.97   151.5 2089.62
   155.6 2088.43  162.122083.302   167.6 2081.99   209.4 2081.54   238.3 2083.25
   267.3 2083.28   275.6 2084.58     302 2085.24   311.8 2084.59     321 2082.43
   328.2 2082.36   341.3 2083.25   371.1 2089.32   389.3 2090.56   501.3 2090.59
   509.9 2092.55   525.3 2100.38   557.3 2110.36   569.3 2115.24   587.4 2117.13
#Mann= 3 ,-1,0
       0      .1       0  162.12    .045       0   238.3      .1       0
Bank Sta=162.12,238.3
XS Rating Curve= 0 ,0
Exp/Cntr(USF)=0,0
Exp/Cntr=0.3,0.1

Type RM Length L Ch R = 1 ,2824    ,292.8,292.8,292.8
XS GIS Cut Line= 2
2379563.19484943725805.0444140912379413.19808998725193.764013114
#Sta/Elev= 30
       0 2271.88    20.5 2258.91    65.8  2219.6      74 2207.54    81.8 2199.35
    90.5 2185.81    94.6 2178.01    98.7 2163.57   102.8 2155.75   113.4 2141.69
   119.3 2131.61   135.8 2112.39   148.1 2094.02   151.2 2090.78   156.4 2088.51
   171.1 2086.43  183.652080.212   209.9 2078.67     284 2078.79   292.3 2080.17
   304.6 2086.61   312.9 2087.59     457 2087.61   477.6 2093.35   516.2  2108.8
   564.1 2123.49   580.6 2131.35   607.6    2133   617.7 2137.18   629.4 2138.76
#Mann= 3 ,-1,0
       0      .1       0  183.65    .045       0   292.3      .1       0
Bank Sta=183.65,292.3
XS Rating Curve= 0 ,0
Exp/Cntr=0.3,0.1

Type RM Length L Ch R = 1 ,2531    ,219.5,219.5,219.5
XS GIS Cut Line= 2
 2379849.9819062725693.396389843 2379668.6872417725121.814600384
#Sta/Elev= 30
       0 2164.76    46.4 2140.93    54.8  2137.2    84.2 2120.98   106.7  2105.7
   109.9 2102.78   117.7  2093.3   121.9 2089.93   130.3 2087.78   142.9 2086.41
   147.1 2084.62   151.3  2081.1  158.952076.522   163.9 2074.88   176.5 2074.77
   243.6 2075.41   250.1 2076.51   264.6 2080.34   310.8 2080.66   336.7 2082.87
   374.4  2083.3   415.8 2082.81   441.3 2084.71   457.6 2089.76   470.8 2094.73
   516.4 2114.32     550 2129.72   558.3 2134.45   566.7 2137.48   599.6 2153.96
#Mann= 3 ,-1,0
       0      .1       0  158.95    .045       0   250.1      .1       0
Bank Sta=158.95,250.1
XS Rating Curve= 0 ,0
Exp/Cntr(USF)=0,0
Exp/Cntr=0.3,0.1

Type RM Length L Ch R = 1 ,2312    ,254,254,254
XS GIS Cut Line= 2
2380080.03296564725684.1292471532379890.69478558725109.944780703
#Sta/Elev= 30
       0 2140.48    11.5 2133.49    28.4 2126.89     121 2098.18   137.9 2091.38
   150.5 2084.55   163.2  2081.7   171.6 2081.45     180 2079.16   192.3 2078.42
   201.1 2075.94   209.5 2076.37  215.672074.421   220.8 2073.47   230.3  2073.2
   303.1    2073   314.8 2073.24  318.672074.447   331.6  2078.5   335.8 2079.18
   361.1 2078.86   390.6 2077.19   424.3 2081.31   470.6 2080.88   500.1 2086.44
   512.2 2091.05   533.8 2102.96   572.4 2127.45     597 2144.51   604.6  2148.8
#Mann= 3 ,-1,0
       0      .1       0  215.67    .045       0  318.67      .1       0
Bank Sta=215.67,318.67
XS Rating Curve= 0 ,0
Exp/Cntr=0.3,0.1

Type RM Length L Ch R = 1 ,2058    ,238.8,238.8,238.8
XS GIS Cut Line= 3
2380250.53975508725669.9628175752380248.02177363725415.646690988
2380162.41040428725035.431491832
#Sta/Elev= 30
       0 2114.81    44.8 2100.19    60.8 2098.41    92.8 2083.95   104.8 2082.56
   120.8 2078.02   176.8  2078.1   204.8 2072.79   244.7 2074.75   281.5 2075.06
   286.4 2074.68   296.4 2070.72   309.8 2069.28   338.9  2069.1   388.1 2069.27
   399.3 2070.65   412.7  2072.4   437.3 2072.16   449.6 2076.57   461.9 2078.09
   473.8 2081.35   490.4 2086.95   494.7 2089.34   515.2 2103.15     548 2128.38
   560.8 2140.67   580.8 2156.61   601.3 2178.58     630 2205.44   644.1 2216.53
#Mann= 3 ,-1,0
       0      .1       0   296.4    .045       0   399.3      .1       0
Bank Sta=296.4,399.3
XS Rating Curve= 0 ,0
Exp/Cntr(USF)=0,0
Exp/Cntr=0.3,0.1

Type RM Length L Ch R = 1 ,1819    ,299.7,299.7,299.7
XS GIS Cut Line= 2
2380484.77322501725679.9992379122380441.71574219725074.928295152
#Sta/Elev= 30
       0 2090.64    18.9 2087.57      75    2081   107.1 2076.03   123.1 2075.12
   131.2 2073.34   139.2 2072.71   175.3  2072.9   207.3 2068.92   235.4 2069.57
   255.5 2068.76   283.5  2071.9   315.6 2071.17   343.9 2073.67   359.7 2071.74
   387.8 2071.06   391.8 2069.68   395.8 2066.92     400 2065.69   419.9 2065.26
     476 2065.82     484 2066.94   492.1 2071.41   500.1 2078.09   508.1 2083.04
   552.2 2122.38     561 2132.12   576.3 2145.45   580.3 2150.07   606.6 2199.41
#Mann= 3 ,-1,0
       0      .1       0   395.8    .045       0     484      .1       0
Bank Sta=395.8,484
XS Rating Curve= 0 ,0
Exp/Cntr=0.3,0.1

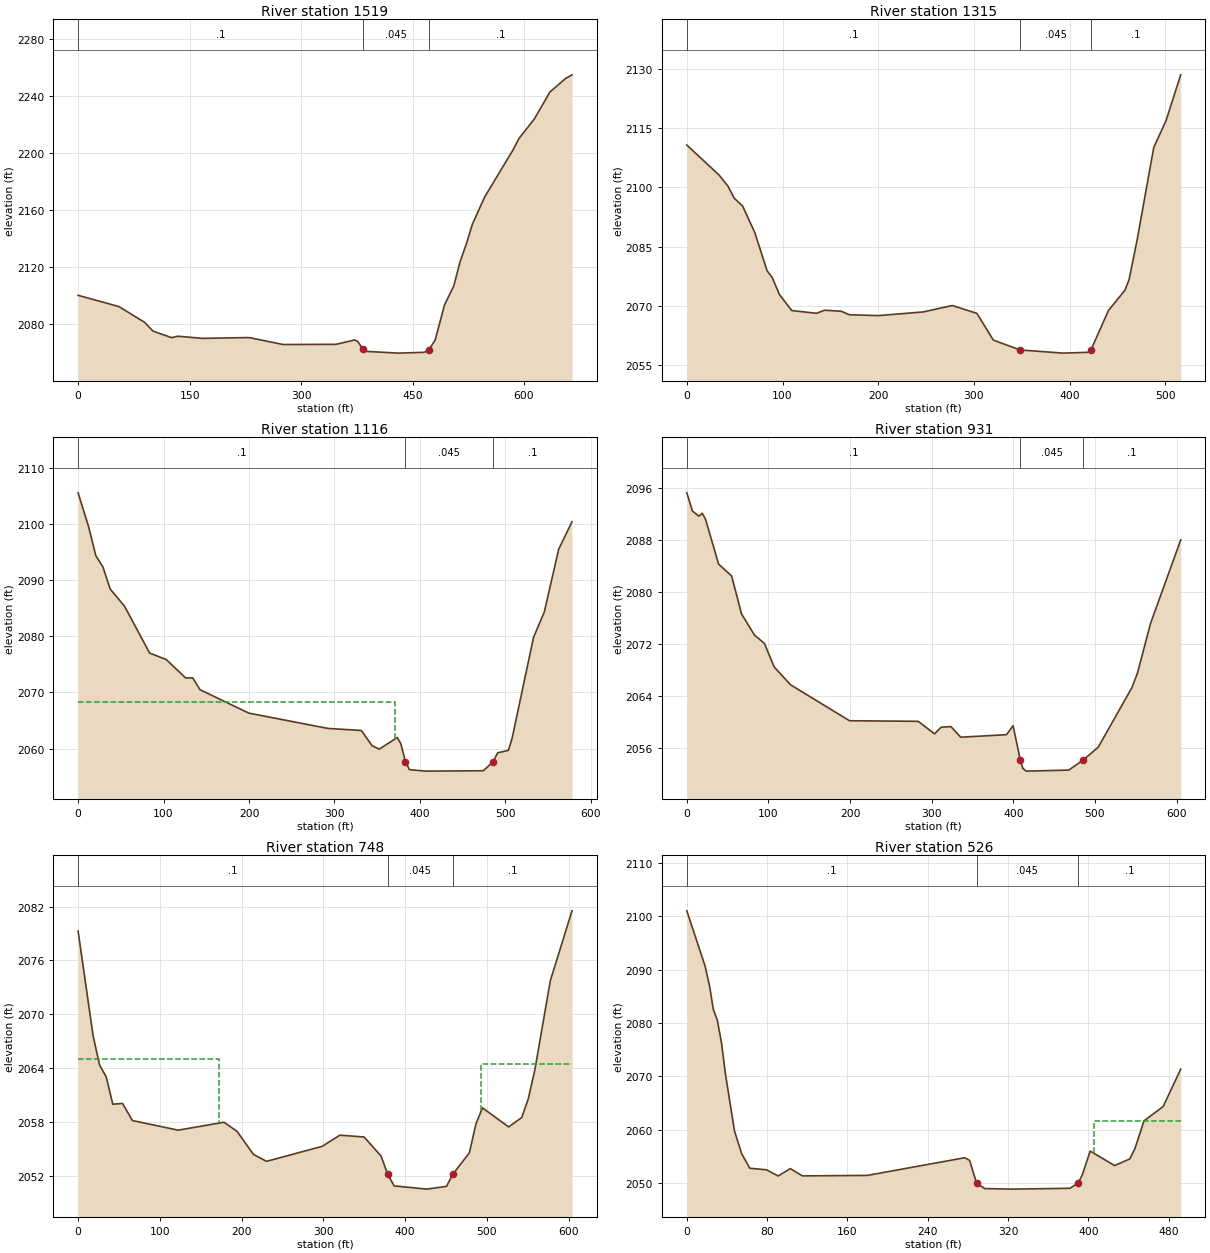
Type RM Length L Ch R = 1 ,1519    ,204.1,204.1,204.1
XS GIS Cut Line= 2
2380625.71899133725717.8044651512380814.56760018725080.755157957
#Sta/Elev= 30
       0 2100.08    54.9 2092.21    89.4 2081.17   100.8 2074.98   125.8 2070.42
   134.2 2071.42   167.5 2069.92   230.1 2070.48     276 2065.59   347.2 2065.75
     372  2068.8   376.1 2067.79   383.42062.276   388.6 2060.78   430.4 2059.57
   465.8 2060.15   472.1 2062.11   480.4 2068.72     493  2093.4   505.5 2106.71
   513.8 2123.46   522.2 2135.86   530.5 2149.95   547.2 2169.22   584.4 2201.33
   593.1 2209.96   613.8 2223.69   634.8 2242.59   655.7 2251.99   664.5 2254.63
#Mann= 3 ,-1,0
       0      .1       0   383.4    .045       0   472.1      .1       0
Bank Sta=383.4,472.1
XS Rating Curve= 0 ,0
Exp/Cntr(USF)=0,0
Exp/Cntr=0.3,0.1

Type RM Length L Ch R = 1 ,1315    ,199.8,199.8,199.8
XS GIS Cut Line= 2
2380794.68347463 725747.275790832380983.44892634725266.940486437
#Sta/Elev= 30
       0 2110.75    33.6 2103.16    42.9 2100.35    49.5 2097.27    58.3 2095.28
      71 2088.55    83.9 2078.83    89.2 2077.15    96.8  2072.8   109.7 2068.75
   135.4 2068.06   144.1 2068.84   161.3 2068.57   169.9 2067.69   200.2 2067.47
   247.2 2068.41   277.4 2070.03   303.1 2068.04   320.3 2061.25   348.3 2058.75
   393.4 2057.95   419.1 2058.16   422.4 2058.82   440.6 2068.77   457.8 2073.91
   462.1 2076.56   470.7 2086.87   487.9 2110.11   500.8 2116.97   516.1 2128.57
#Mann= 3 ,-1,0
       0      .1       0   348.3    .045       0   422.4      .1       0
Bank Sta=348.3,422.4
XS Rating Curve= 0 ,0
Exp/Cntr=0.3,0.1

Type RM Length L Ch R = 1 ,1116    ,184.9,184.9,184.9
XS GIS Cut Line= 2
2380992.85152226725864.9197956992381168.25411016725314.237252289
#Sta/Elev= 30
       0 2105.54    12.3 2099.49    20.7 2094.35    29.1 2092.32    37.5 2088.41
    54.3 2085.35    83.7    2077   103.2 2075.84   125.7 2072.58   134.1 2072.58
   142.7 2070.47   199.8  2066.3   292.2 2063.58   331.4 2063.21     344  2060.5
   352.4 2059.89   373.4 2061.95   377.5 2060.89  383.012057.672   387.7 2056.23
   406.8 2055.97   474.1 2056.04   485.4  2057.6   490.9 2059.23   503.5 2059.67
   507.7 2061.74   532.9 2079.79   545.5 2084.32   562.3 2095.48   577.9 2100.39
#Mann= 3 ,-1,0
       0      .1       0  383.01    .045       0   485.4      .1       0
#XS Ineff= 2 , 0
          371.06 2068.32
Permanent Ineff=
       F       F
Bank Sta=383.01,485.4
XS Rating Curve= 0 ,0
Exp/Cntr(USF)=0,0
Exp/Cntr=0.3,0.1

Type RM Length L Ch R = 1 ,931     ,182.7,182.7,182.7
XS GIS Cut Line= 2
2381274.31148889 725919.988050042381315.10278841725316.276817264
#Sta/Elev= 30
       0 2095.25     6.8 2092.46    14.8 2091.66    18.9 2092.11    22.9  2091.2
    38.9 2084.31    54.9 2082.48      67 2076.66      83 2073.39      95 2072.13
   107.1  2068.5   127.1 2065.77   199.3 2060.25   283.5 2060.16   303.5 2058.23
   311.5 2059.25   323.5 2059.35   335.6 2057.72   391.7 2058.11   399.7 2059.49
  408.612054.201   411.7 2052.93   415.8 2052.51   467.9 2052.67   485.1 2054.16
     504 2056.18   545.2 2065.31   552.1 2067.56   568.1 2075.18   605.1 2088.02
#Mann= 3 ,-1,0
       0      .1       0  408.61    .045       0   485.1      .1       0
Bank Sta=408.61,485.1
XS Rating Curve= 0 ,0
Exp/Cntr(USF)=0,0
Exp/Cntr=0.3,0.1

Type RM Length L Ch R = 1 ,748     ,221.7,221.7,221.7
XS GIS Cut Line= 2
2381500.70320119725895.5132703332381480.30755143725291.802037557
#Sta/Elev= 30
       0 2079.27    18.3 2067.64    26.3 2064.35    34.4 2063.05    42.4 2060.01
    54.4 2060.09    66.4 2058.19   122.4 2057.12   178.4    2058   194.4 2056.99
   214.5 2054.42   230.5 2053.65   298.5 2055.32   320.2 2056.56   349.8 2056.36
   370.6 2054.24   378.6 2052.22   386.6 2050.92   426.6 2050.56   450.6 2050.87
   458.6 2052.25   478.6  2054.6   486.6 2057.81   494.6  2059.6   526.6 2057.48
   542.6 2058.52   550.6  2060.6   558.7 2063.84   577.6 2073.75   604.1 2081.52
#Mann= 3 ,-1,0
       0      .1       0   378.6    .045       0   458.6      .1       0
#XS Ineff= 2 , 0
          172.53 2065.04  493.29         2064.43
Permanent Ineff=
       F       F
Bank Sta=378.6,458.6
XS Rating Curve= 0 ,0
Exp/Cntr(USF)=0,0
Exp/Cntr=0.3,0.1

Type RM Length L Ch R = 1 ,526     ,169.8,169.8,169.8
XS GIS Cut Line= 2
2381751.56969318725783.3371966752381684.26404899725295.881167508
#Sta/Elev= 30
       0 2101.03    18.3 2090.61    22.7 2086.89    26.4 2082.55    30.4 2080.52
    34.5 2076.34    38.5 2070.42    47.5 2059.75    54.6 2055.51    62.7 2052.78
    79.4 2052.48      91 2051.33   103.1 2052.71   115.2 2051.34   179.8 2051.43
   276.8 2054.74   281.7 2054.26   288.8 2049.94   296.9 2048.96   325.2 2048.86
   381.7 2049.02   389.8 2049.97   393.9 2051.47   401.9 2055.99   426.2 2053.28
   441.3 2054.51   446.4 2056.41   455.5 2061.65   474.6 2064.35   492.1 2071.35
#Mann= 3 ,-1,0
       0      .1       0   288.8    .045       0   389.8      .1       0
#XS Ineff= 2 , 0
                           405.2         2061.65
Permanent Ineff=
       F       F
Bank Sta=288.8,389.8
XS Rating Curve= 0 ,0
Exp/Cntr(USF)=0,0
Exp/Cntr=0.3,0.1

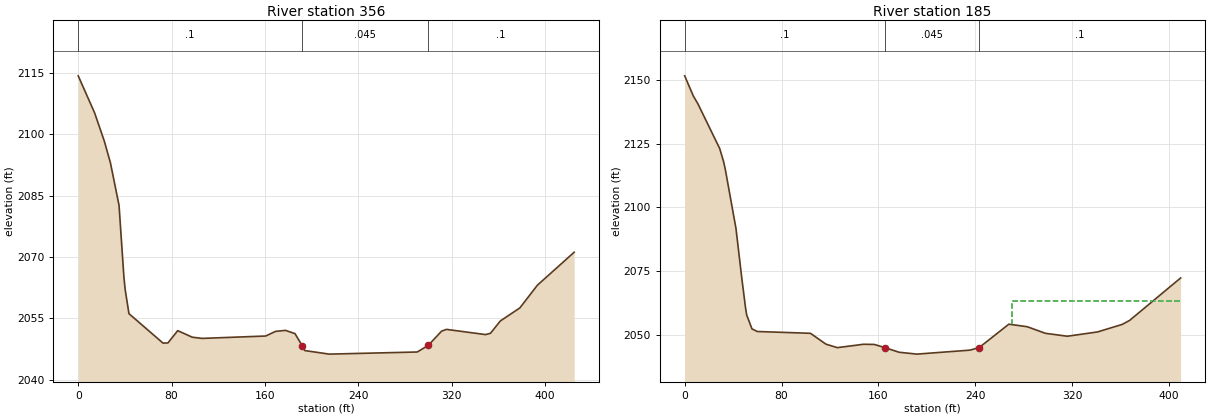
Type RM Length L Ch R = 1 ,356     ,171.5,171.5,171.5
XS GIS Cut Line= 2
2381941.24923591725642.6072133592381814.79620743725236.733783216
#Sta/Elev= 30
       0 2114.22    14.1 2105.15    22.4 2098.26    27.6    2093      35  2082.6
    39.2 2064.97    40.3 2061.95    43.5 2056.16    72.7 2048.97    76.9 2049.01
    85.3 2052.01    97.8 2050.41   106.2 2050.12   160.7  2050.7   169.1 2051.83
   177.7 2052.08   185.8 2051.29   191.9 2048.38   194.2 2047.15   215.2 2046.28
   290.6  2046.8  300.022048.405   311.5  2051.9   315.7 2052.32   349.2 2051.05
   353.4 2051.37   361.8 2054.37   378.6 2057.57   393.6 2063.11   425.1 2071.15
#Mann= 3 ,-1,0
       0      .1       0   191.9    .045       0  300.02      .1       0
Bank Sta=191.9,300.02
XS Rating Curve= 0 ,0
Exp/Cntr(USF)=0,0
Exp/Cntr=0.3,0.1

Type RM Length L Ch R = 1 ,185     ,,,
XS GIS Cut Line= 2
2382112.11741086725535.7702297042381942.64995704725162.733795668
#Sta/Elev= 30
       0 2151.51     7.2 2143.57      11 2140.49    28.9 2123.09    32.1 2118.03
    33.6 2114.81    42.4 2091.72    47.2 2072.27    50.2    2061    51.2 2057.96
    55.6 2052.47      60 2051.45   103.9 2050.75   116.7  2046.5   126.1 2045.14
   147.8 2046.46   156.6 2046.39   165.4 2045.15   177.1 2043.34   191.8  2042.6
   235.7 2044.16   243.32045.171   267.8 2054.32   282.9 2053.33     298 2050.75
   316.1  2049.6   341.1 2051.29   361.4 2054.22   367.5 2055.77   409.7  2072.4
#Mann= 3 ,-1,0
       0      .1       0   165.4    .045       0   243.3      .1       0
#XS Ineff= 2 , 0
                          270.21         2063.22
Permanent Ineff=
       F       F
Bank Sta=165.4,243.3
XS Rating Curve= 0 ,0
Exp/Cntr(USF)=0,0
Exp/Cntr=0.3,0.1
LCMann Table=0

Chan Stop Cuts=-1
Use User Specified Reach Order=0
Composite Channel Slope=5